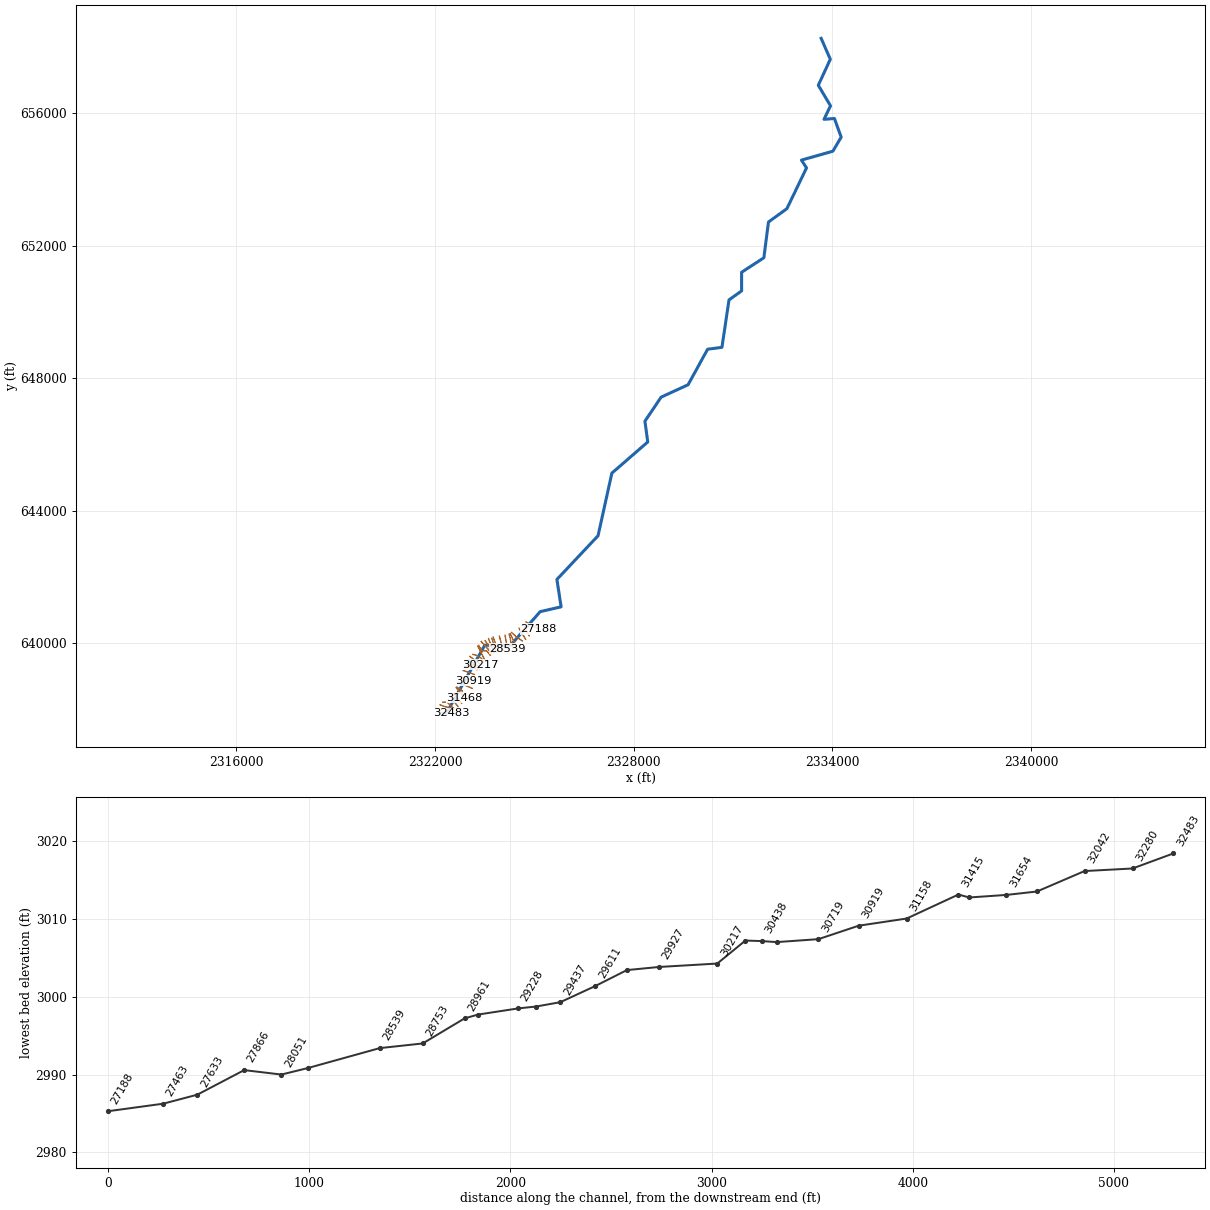
--- WFKGLADYFK.prj (project) ---

Proj Title=WFKGLADYFK
Current Plan=p01
Default Exp/Contr=0,0
English Units
Geom File=g01
Flow File=f01
Plan File=p01
Background Map Layer=Inundation Boundary (P100yr Value_0)
BEGIN DESCRIPTION:
----------MODEL BY WOOD PLC 2022----------
AFH study
Randolph County, WV
HEC-RAS Version: RAS 6.2
Vertical Datum: NAVD88
Projection: NAD 1983 StatePlane West Virginia S FIPS 4702 (US Feet)
Terrain: 1-meter LIDAR (FEMA Region III 3DEP collected 2016-2018)
Land Use: 2019 NLCD
Hydrologic Method:
WV SIR2010-5033 regression equations
Additional Model Notes:
None
END DESCRIPTION:
DSS Export Rating Curves= 0
DSS Export Rating Curve Sorted= 0
DSS Export Volume Flow Curves= 0
DXF OffsetX= 0
DXF OffsetY= 0
DXF ScaleX= 0
DXF ScaleY= 0

--- WFKGLADYFK.p01 (plan) ---

Plan Title=Floodplain
Program Version=6.20
Short Identifier=Floodplain
Geom File=g01
Flow File=f01
Subcritical Flow
K Sum by GR= 0
Std Step Tol= 0.01
Critical Tol= 0.01
Num of Std Step Trials= 20
Max Error Tol= 0.3
Flow Tol Ratio= 0.001
Split Flow NTrial= 30
Split Flow Tol= 0.02
Split Flow Ratio= 0.02
Log Output Level= 0
Friction Slope Method= 1
Unsteady Friction Slope Method= 2
Unsteady Bridges Friction Slope Method= 1
Parabolic Critical Depth
Global Vel Dist= 0 , 0 , 0
Global Log Level= 0
CheckData=False
Encroach Param=-1 ,0,0, 0
Mapping Interval=1HOUR
Computation Time Step Use Courant=        0
Computation Time Step Use Time Series=    0
Computation Time Step Count To Double=0
Computation Time Step Max Doubling=0
Computation Time Step Max Halving=0
Computation Time Step Residence Courant=0
Run HTab= 0
Run UNet= 0
Run Sediment= 0
Run PostProcess= 0
Run WQNet= 0
Run RASMapper=-1
UNET Theta= 0
UNET Theta Warmup= 0
UNET ZTol= 0
UNET ZSATol= 0
UNET MxIter= 0
UNET Max Iter WO Improvement= 0
UNET MaxInSteps= 0
UNET DtIC= 0
UNET DtMin= 0
UNET MaxCRTS= 0
UNET WFStab= 0
UNET SFStab= 0
UNET WFX= 1
UNET SFX= 1
UNET Gravity=32.174
UNET 1D Methodology=Finite Difference
UNET DSS MLevel= 1
UNET Pardiso=0
UNET DZMax Abort= 0
UNET Use Existing IB Tables= 0
UNET Froude Reduction=False
UNET Froude Limit= 0
UNET Froude Power= 0
UNET D1 Cores= 0
UNET WindReference=Eulerian
UNET WindDragFormulation=Hsu (1988)
UNET D2 Coriolis=0
UNET D2 Cores= 0
UNET D2 Theta= 1
UNET D2 Theta Warmup= 1
UNET D2 Z Tol= 0.01
UNET D2 Volume Tol= 0.01
UNET D2 Max Iterations= 20
UNET D2 Equation= 0
UNET D2 RampUpFraction=0.1
UNET D2 TimeSlices= 1
UNET D2 Turbulence Formulation=Non-Conservative (original)
UNET D2 Eddy Viscosity=0.3
UNET D2 Transverse Eddy Viscosity=0.1
UNET D2 Smagorinsky Mixing=0
UNET D2 BCVolumeCheck=0
UNET D2 Cores=0
UNET D2 SolverType=PARDISO (Direct)
UNET D2 Minimum Iterations= 2147483647
UNET D2 Maximum Iterations= 2147483647
UNET D2 Restart Number= 10
UNET D2 Relaxation Coeff=1.3
UNET D2 SOR Precondition Iterations= 10
UNET D2 ILUT Maximum Fill= 8
UNET D2 ILUT Tolerance=1E-08
UNET D1D2 MaxIter= 0
UNET D1D2 ZTol=0.01
UNET D1D2 QTol=0.1
UNET D1D2 MinQTol=1
Write IC File= 0
Write IC File at Fixed DateTime=0
Write IC File at Sim End=0
Echo Input=False
Echo Parameters=False
Echo Output=False
Write Detailed= 0
HDF Write Warmup=0
HDF Write Time Slices=0
HDF Flush=0
HDF Compression= 1
HDF Chunk Size= 1
HDF Spatial Parts= 1
HDF Use Max Rows=0
HDF Fixed Rows= 1
Calibration Method= 0
Calibration Iterations= 20
Calibration Max Change=0.05
Calibration Tolerance=0.2
Calibration Maximum=1.5
Calibration Minimum=0.5
Calibration Optimization Method= 1
WQ AD Non Conservative
WQ ULTIMATE=-1
WQ Max Comp Step=1HOUR
WQ Output Interval=15MIN
WQ Output Selected Increments= 0
WQ Output face flow=0
WQ Output face velocity=0
WQ Output face area=0
WQ Output face dispersion=0
WQ Output cell volume=0
WQ Output cell surface area=0
WQ Output cell continuity=0
WQ Output cumulative cell continuity=0
WQ Output face conc=0
WQ Output face dconc_dx=0
WQ Output face courant=0
WQ Output face peclet=0
WQ Output face adv mass=0
WQ Output face disp mass=0
WQ Output cell mass=0
WQ Output cell source sink temp=0
WQ Output nsm pathways=0
WQ Output nsm derived pathways=0
WQ Create Restart=0
WQ Fixed Restart=0
WQ System Summary=0
WQ Write To DSS=0
Sorting and Armoring Iterations= 10
XS Update Threshold= 0.02
Bed Roughness Predictor= 0
Hydraulics Update Threshold= 0.02
Energy Slope Method= 1
Volume Change Method= 1
Sediment Retention Method= 0
Sediment TS Multiplier= 1
Warm Up Method= 0
XS Weighting Method= 0
Number of US Weighted Cross Sections= 1
Number of DS Weighted Cross Sections= 1
Upstream XS Weight=0
Main XS Weight=1
Downstream XS Weight=0
Number of DS XS's Weighted with US Boundary= 1
Upstream Boundary Weight= 1
Weight of XSs Associated with US Boundary= 0
Number of US XS's Weighted with DS Boundary= 1
Downstream Boundary Weight= 0.5
Weight of XSs Associated with DS Boundary= 0.5
Percentile Method= 0
Sediment Output Level= 3
Mass or Volume Output= 0
Output Increment Type= 1
Profile and TS Output Increment= 1
Transport Output Increment 1
XS Output Flag= 0
XS Output Increment= 10
Read HDF5 Sediment Hotstart= 0
Sediment Hotstart Type= 0
Write Gradation File= 0
Read Gradation Hotstart= 0
Write HDF5 File= 1
Write Binary Output= 1
Write DSS Sediment File= 0
DSS Sediment Output Type= 1
SV Curve= 0
Specific Gage Flag= 0
Subcell Erosion Methods= 0
Subcell Deposition Methods= 0
Advection Scheme= 1
Matrix Solver= 0
Implicit Weighting Factor= 1
Maximum Outer Loop Convergence Iterations= 5
Convergence Maximum Absolute= 0.001
Convergence RMSE= 0.0001
Grain Fractions Max Abs Error= 0.001
Max Subgrid Regions= 1
Max Subgrid Length Scale= 3.402823E+38
Initial Layer Thickness= 3.402823E+38
Min Layer Thickness= 3.402823E+38
Max Layer Thickness= 3.402823E+38
Number of Layers= 5

--- WFKGLADYFK.f01 (steady flow) ---

Flow Title=Flow
Program Version=4.00
Number of Profiles=1
Profile Names=P100yr
River Rch & RM=WFKGLADYFK,Main,32483
     400
River Rch & RM=WFKGLADYFK,Main,29768
     505
River Rch & RM=WFKGLADYFK,Main,26955
     577
River Rch & RM=WFKGLADYFK,Main,25444
     693
River Rch & RM=WFKGLADYFK,Main,24463
     796
River Rch & RM=WFKGLADYFK,Main,20954
     899
River Rch & RM=WFKGLADYFK,Main,17583
    1080
River Rch & RM=WFKGLADYFK,Main,12927
    1200
River Rch & RM=WFKGLADYFK,Main,7959
    1340
Boundary for River Rch & Prof#=WFKGLADYFK,Main      ,1
Up Type=0
Dn Type=3
Dn Slope=0.002193

--- WFKGLADYFK.g01 (geometry) ---

Geom Title=Geometry
Program Version=6.20

River Reach=WFKGLADYFK      ,Main
Reach XY= 30
     2322345.157      637883.658     2323501.606      639933.368
      2324289.54       639942.57     2325176.995      640951.098
     2325807.735      641094.483     2325681.178      641922.811
     2326922.221      643242.052     2327340.574      645134.781
     2328423.154       646075.86     2328338.151       646703.65
     2328826.652      647429.602     2329641.703      647804.567
     2330230.746       648877.53     2330663.273      648934.866
     2330876.416      650367.698     2331257.323      650640.563
     2331256.349      651202.227     2331928.734      651640.713
     2332067.805      652720.797     2332623.817      653123.189
     2333216.404      654354.861     2333063.448      654591.101
     2334012.779      654860.174     2334262.701      655284.802
     2334059.313      655848.595     2333744.699      655823.596
     2333941.119      656231.393     2333572.469      656852.683
     2333934.833      657637.195     2333658.361      658269.856

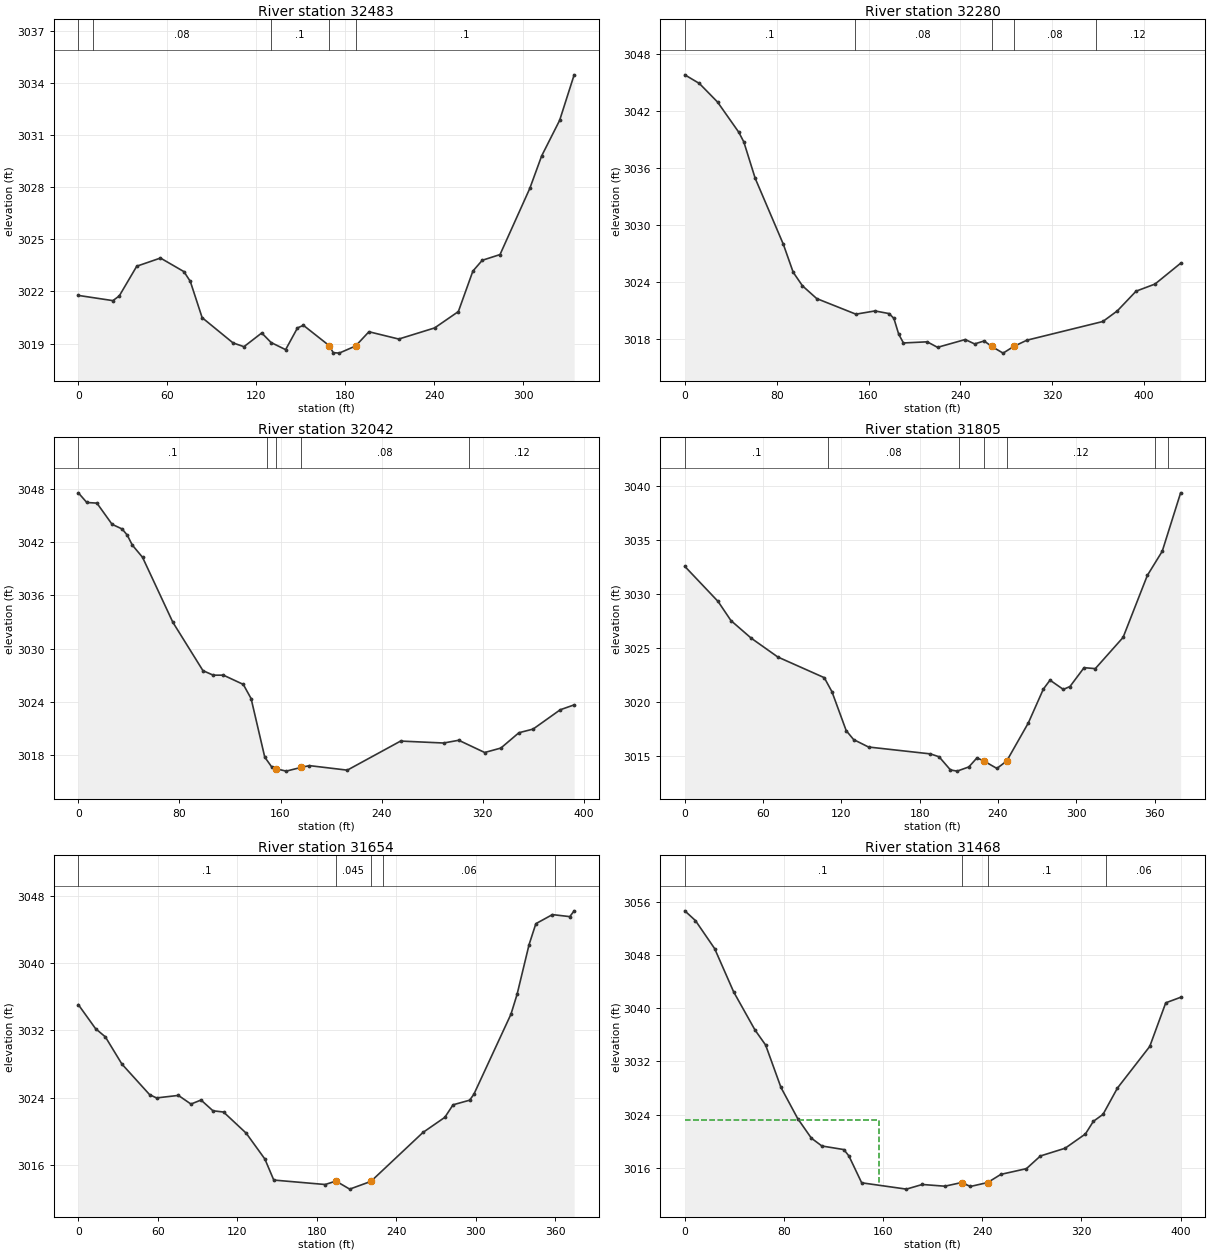
Type RM Length L Ch R = 1 ,32483   ,203.5,203.5,203.5
XS GIS Cut Line= 2
2322164.98311255637907.4729154982322497.91571845637876.606070358
#Sta/Elev= 30
       0 3021.77    23.3 3021.47    27.6 3021.74    39.4 3023.45    55.4 3023.92
    71.2 3023.14    75.5 3022.58    83.5 3020.49   104.3 3019.04   111.7 3018.82
   123.7 3019.61     130 3019.06   139.8 3018.65   147.8  3019.9   151.8 3020.05
   169.2 3018.88   171.9 3018.48   175.9 3018.45     187 3018.86     196 3019.68
   216.1 3019.26   240.3  3019.9   256.3 3020.84   266.1 3023.17   272.4 3023.79
   284.4 3024.12   304.5 3027.93   312.5  3029.8   324.6 3031.84   334.4 3034.46
#Mann= 5, -1 ,  0
       0     0.1       0      10    0.08       0     130     0.1       0
   169.2   0.045       0     187     0.1       0
Bank Sta=169.2,187
XS Rating Curve= 0 ,0
Exp/Cntr=0.3,0.1

Type RM Length L Ch R = 1 ,32280   ,238.3,238.3,238.3
XS GIS Cut Line= 3
2322156.39877793 638134.441487642322266.02036726638091.133727456
2322569.67110292638011.398635657
#Sta/Elev= 30
       0  3045.8    12.7 3044.89    28.5 3042.94      47 3039.76    51.4 3038.74
    61.3 3034.91    85.8 3027.97    94.4 3025.02   102.5 3023.59   114.9 3022.25
     149 3020.61   165.6 3020.95     178 3020.67   182.1 3020.16   186.3  3018.5
   190.4 3017.58   211.1  3017.7   220.1 3017.12   244.2 3017.94   252.4 3017.48
   260.7 3017.79   267.3 3017.21   277.2 3016.51   286.4 3017.21   297.9 3017.87
   364.1 3019.84   376.7 3020.96     393 3023.03   409.5 3023.78   431.8 3025.97
#Mann= 5, -1 ,  0
       0     0.1       0  147.87    0.08       0   267.3   0.045       0
   286.4    0.08       0  357.87    0.12       0
Bank Sta=267.3,286.4
XS Rating Curve= 0 ,0
Exp/Cntr(USF)=0,0
Exp/Cntr=0.3,0.1

Type RM Length L Ch R = 1 ,32042   ,236.5,236.5,236.5
XS GIS Cut Line= 3
2322233.42674372638212.1978213612322362.88646753638213.330025024
2322556.28487539638035.379019702
#Sta/Elev= 30
       0 3047.56     6.7 3046.47    14.7  3046.4    26.7 3044.01    34.7 3043.48
    38.7 3042.79    42.7 3041.67    50.8 3040.29    74.8 3032.96    98.6 3027.51
   106.7    3027   114.8    3027   130.5 3025.96   136.7 3024.36   147.5 3017.76
   153.1 3016.63   156.53016.442   164.5 3016.18   176.33016.602   182.9  3016.8
   212.8 3016.29     255 3019.57     289 3019.35     301 3019.66   321.5 3018.28
   334.3 3018.78   348.6 3020.51   359.8 3020.92   381.3  3023.1   392.3 3023.65
#Mann= 5, -1 ,  0
       0     0.1       0  149.46    0.08       0   156.5   0.045       0
   176.3    0.08       0  309.46    0.12       0
Bank Sta=156.5,176.3
XS Rating Curve= 0 ,0
Exp/Cntr=0.3,0.1

Type RM Length L Ch R = 1 ,31805   ,151.4,151.4,151.4
XS GIS Cut Line= 2
 2322458.4516226 638385.197699112322693.31999219638086.506403005
#Sta/Elev= 30
       0 3032.57    25.5 3029.31    35.4 3027.53    50.9  3025.9    71.3 3024.15
   106.9 3022.23   112.8 3020.92   123.7 3017.31   129.4 3016.48   140.8 3015.79
   188.3 3015.15   194.9 3014.88   203.6 3013.66   208.7 3013.55   217.7 3013.94
   223.9 3014.78   229.1  3014.5   239.2  3013.8  246.71 3014.49   263.3 3018.03
   274.8 3021.17   279.9    3022   290.1 3021.14   295.2 3021.41     306 3023.16
   314.6 3023.07   335.9 3025.97   354.5 3031.73   365.9 3033.97     380  3039.4
#Mann= 7, -1 ,  0
       0     0.1       0     110    0.08       0     210    0.12       0
   229.1   0.045       0  246.71    0.12       0     360     0.1       0
     370    0.06       0
Bank Sta=229.1,246.71
XS Rating Curve= 0 ,0
Exp/Cntr(USF)=0,0
Exp/Cntr=0.3,0.1

Type RM Length L Ch R = 1 ,31654   ,185.8,185.8,185.8
XS GIS Cut Line= 2
2322563.12421201638474.4970571772322802.67111839638187.040769516
#Sta/Elev= 30
       0 3035.08      13 3032.22    20.4 3031.24    32.9    3028    53.8 3024.36
      59 3023.97    75.5 3024.27      85 3023.24    92.6 3023.72   101.6 3022.44
   109.6 3022.29   126.7 3019.77   140.8 3016.69   147.5 3014.19   186.3 3013.66
   194.4 3014.07   204.8 3013.11   220.8 3014.03   260.1 3019.86   276.6 3021.66
   282.8 3023.15   295.3  3023.7   298.5  3024.4   326.5 3033.94   331.1 3036.29
   340.2 3042.24   345.3 3044.72   357.8  3045.8   370.9 3045.56   374.2 3046.25
#Mann= 5, -1 ,  0
       0     0.1       0   194.4   0.045       0   220.8     0.1       0
     230    0.06       0     360     0.1       0
Bank Sta=194.4,220.8
XS Rating Curve= 0 ,0
Exp/Cntr(USF)=0,0
Exp/Cntr=0.3,0.1

Type RM Length L Ch R = 1 ,31468   ,52.9,52.9,52.9
XS GIS Cut Line= 2
2322639.18574797638655.8540850962322891.70866938638345.673864173
#Sta/Elev= 30
       0 3054.65     8.6 3053.18    24.1 3048.96    39.4 3042.46    56.6 3036.73
    65.2 3034.46    77.6 3028.07    91.1 3023.39   102.1 3020.45   110.6 3019.27
   128.3 3018.73   132.4 3017.77   142.7 3013.73   178.8 3012.78   191.6 3013.48
   209.8 3013.22   223.3 3013.77   230.4 3013.18   244.3 3013.77     255    3015
   275.6 3015.86   286.9 3017.77   306.8 3018.93   323.2 3021.08   329.6 3022.98
   337.4 3024.03     349 3027.98   375.1 3034.25     388 3040.81     400 3041.64
#Mann= 4, -1 ,  0
       0     0.1       0   223.3   0.045       0   244.3     0.1       0
     340    0.06       0
#XS Ineff= 2 , 0
          156.92 3023.13
Permanent Ineff=
       F       F
Bank Sta=223.3,244.3
XS Rating Curve= 0 ,0
Exp/Cntr=0.3,0.1

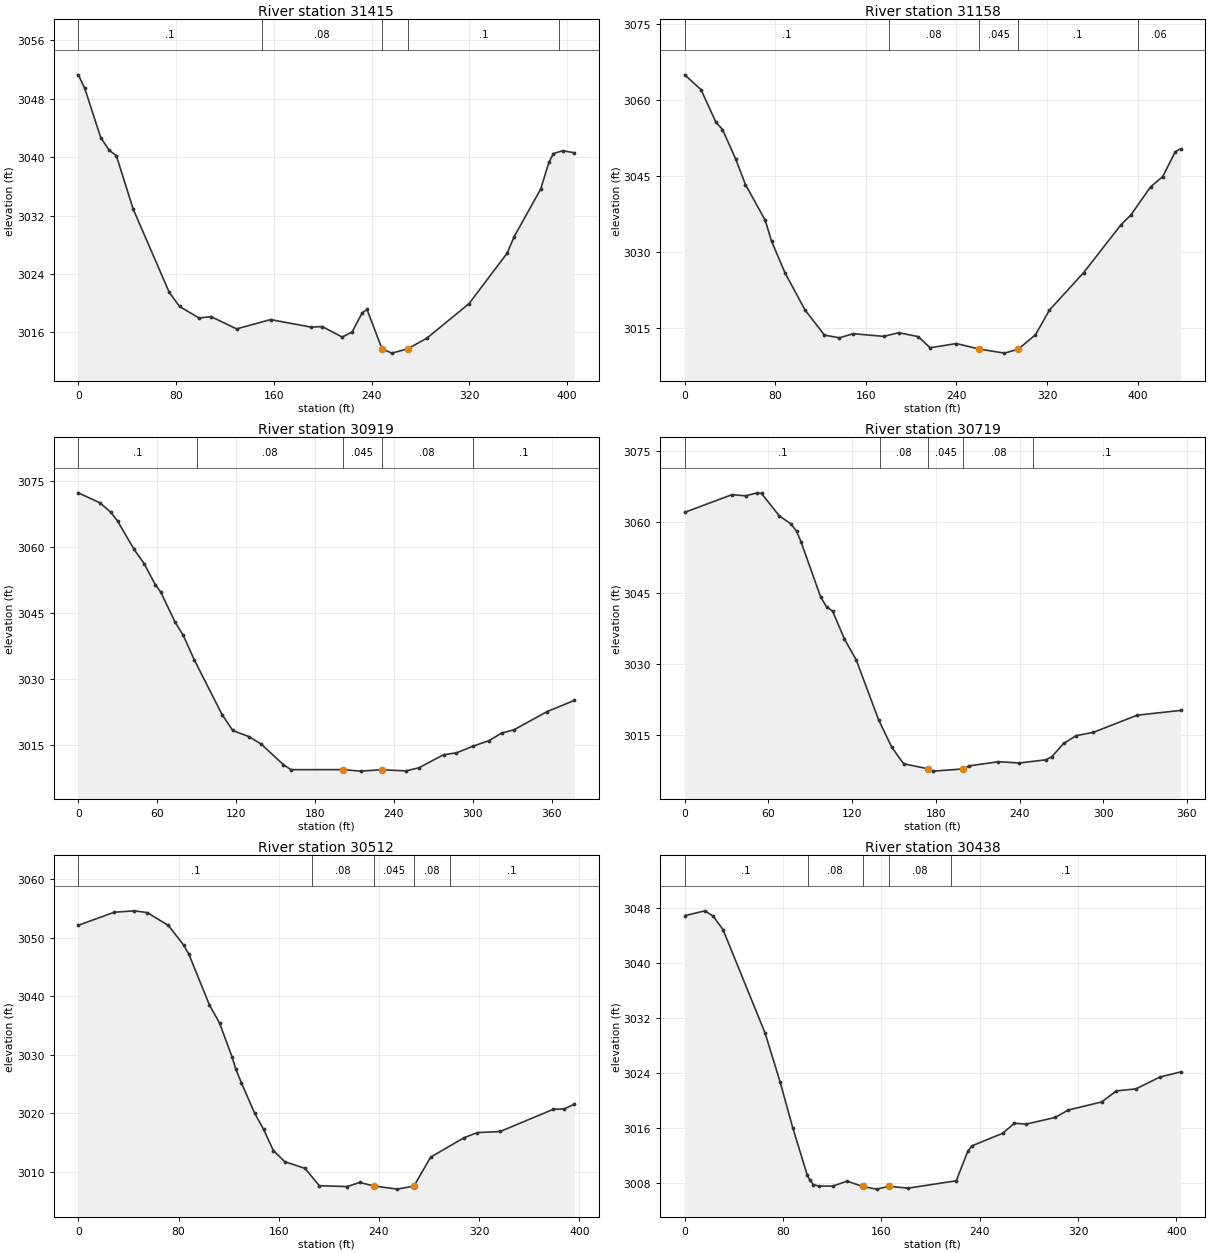
Type RM Length L Ch R = 1 ,31415   ,257.6,257.6,257.6
XS GIS Cut Line= 4
2322663.46374087638671.8005963572322819.19168158638562.025162746
 2322838.9767888638461.184938847 2322925.1377396638389.065031881
#Sta/Elev= 30
       0 3051.27     5.3  3049.4    18.4 3042.64    25.3 3040.94    31.1  3040.2
    44.9 3032.88    74.3 3021.51    82.8 3019.55    98.7 3017.98   108.7 3018.15
   129.5 3016.48   157.3 3017.75   190.5 3016.72   199.5  3016.8   215.9 3015.36
     224 3016.05   232.2 3018.65   236.2 3019.15   248.5 3013.74   256.6 3013.16
  269.36 3013.74   285.1  3015.2   319.7 3019.94   350.9 3026.86   356.6 3029.11
   378.3 3035.62     385 3039.28   388.7 3040.49   396.4 3040.88   405.7  3040.6
#Mann= 5, -1 ,  0
       0     0.1       0     150    0.08       0   248.5   0.045       0
  269.36     0.1       0  393.29    0.06       0
Bank Sta=248.5,269.36
XS Rating Curve= 0 ,0
Exp/Cntr(USF)=0,0
Exp/Cntr=0.3,0.1

Type RM Length L Ch R = 1 ,31158   ,238.3,238.3,238.3
XS GIS Cut Line= 2
2322719.05883358638807.8374421372323120.50640773638632.720393331
#Sta/Elev= 30
       0 3064.92    14.3 3062.01    27.4 3055.63    33.3 3054.14    44.9 3048.37
    53.6 3043.29      71 3036.28    76.7 3032.09    88.5  3025.9   106.2 3018.58
   123.4 3013.62   136.6 3013.09   148.7  3013.9   175.8 3013.37   188.9  3014.1
   206.3 3013.32   216.7 3011.13   239.9 3011.96   260.2 3010.87   282.4 3010.07
   294.6 3010.85   309.8  3013.7   322.1 3018.55   352.3 3025.93   385.2 3035.34
     394 3037.29   411.4 3042.82   422.2 3044.88   433.3 3049.76     438 3050.33
#Mann= 5, -1 ,  0
       0     0.1       0     180    0.08       0   260.2   0.045       0
   294.6     0.1       0     400    0.06       0
Bank Sta=260.2,294.6
XS Rating Curve= 0 ,0
Exp/Cntr(USF)=0,0
Exp/Cntr=0.3,0.1

Type RM Length L Ch R = 1 ,30919   ,200.1,200.1,200.1
XS GIS Cut Line= 2
2322804.91815009638983.8029635762323160.99554591638859.801898845
#Sta/Elev= 30
       0 3072.31    16.2 3070.08    24.6 3067.93    29.8 3065.93    42.3 3059.52
      50 3056.26    58.5  3051.5    62.7 3049.78    73.7  3042.9    79.7 3040.03
    88.2  3034.4   109.3    3022   117.4 3018.39   129.6    3017     139 3015.31
   155.9 3010.63   161.7 3009.48  201.01 3009.49   214.7 3009.15   230.8 3009.47
   249.1  3009.2   259.1 3009.92   277.9 3012.89   287.4 3013.28     300 3014.79
   312.5 3016.09   321.9 3017.79   331.3 3018.53   356.5 3022.66   377.1 3025.18
#Mann= 5, -1 ,  0
       0     0.1       0      90    0.08       0  201.01   0.045       0
   230.8    0.08       0     300     0.1       0
Bank Sta=201.01,230.8
XS Rating Curve= 0 ,0
Exp/Cntr=0.3,0.1

Type RM Length L Ch R = 1 ,30719   ,206.8,206.8,206.8
XS GIS Cut Line= 2
2322852.34217958639171.8098158062323187.26989069639052.579886284
#Sta/Elev= 30
       0 3062.07    33.8 3065.79    43.6 3065.55      52 3066.18      55 3066.04
    67.8  3061.3    76.2  3059.6    80.2 3058.02    83.3 3055.87    97.5 3044.12
   101.7  3042.1     106 3041.18   114.5 3035.29     123 3030.85     139 3018.22
   148.4 3012.46   156.9 3008.98   174.33007.915   178.2 3007.42   199.8 3007.89
   203.6 3008.52   224.9 3009.41   239.9 3009.14   258.8 3009.81   263.1 3010.44
   271.6 3013.27   280.6 3014.91   292.8  3015.6   324.4 3019.23   355.5 3020.24
#Mann= 5, -1 ,  0
       0     0.1       0     140    0.08       0   174.3   0.045       0
   199.8    0.08       0     250     0.1       0
Bank Sta=174.3,199.8
XS Rating Curve= 0 ,0
Exp/Cntr(USF)=0,0
Exp/Cntr=0.3,0.1

Type RM Length L Ch R = 1 ,30512   ,74.8,74.8,74.8
XS GIS Cut Line= 3
2322905.36315562639295.9522279242323020.24442335639317.205262454
2323271.25999335639195.431118657
#Sta/Elev= 30
       0 3052.13    28.7 3054.36    44.7  3054.6      55  3054.3    71.9  3052.1
    84.2 3048.71    88.3 3047.16   104.6 3038.54   112.7 3035.44   122.8 3029.59
   125.6  3027.6   130.1 3025.24   140.7 3020.04   147.9 3017.26   155.7 3013.63
   164.7 3011.74     181 3010.58   192.3 3007.63   214.6 3007.48   224.6 3008.18
     236 3007.58   254.5 3007.04   267.9 3007.56   281.2  3012.5   307.9 3015.83
   318.5  3016.7   336.8 3016.89   379.1 3020.68     388 3020.75   395.8 3021.55
#Mann= 5, -1 ,  0
       0     0.1       0  186.83    0.08       0     236   0.045       0
   267.9    0.08       0  296.83     0.1       0
Bank Sta=236,267.9
XS Rating Curve= 0 ,0
Exp/Cntr(USF)=0,0
Exp/Cntr=0.3,0.1

Type RM Length L Ch R = 1 ,30438   ,81.2,81.2,81.2
XS GIS Cut Line= 4
2323002.78201591639419.9270330392323120.88935897639336.321245061
2323142.08495286639332.185519422 2323342.3992056639205.196770074
#Sta/Elev= 30
       0 3046.84    16.4 3047.54    23.1 3046.76    31.1 3044.82    65.4 3029.78
    77.6  3022.7    87.8  3016.1    99.7 3009.18   101.7  3008.5   104.6 3007.83
   109.1 3007.61   120.6 3007.62   132.1 3008.33   144.7 3007.56   156.2 3007.17
   166.3 3007.58   181.6 3007.31   220.9 3008.38   230.3 3012.67   233.8 3013.46
   258.8 3015.28   268.2 3016.73   277.7  3016.6   301.4 3017.57     312 3018.64
   339.3 3019.82   351.2 3021.42   367.1 3021.71   386.6 3023.43   403.5 3024.17
#Mann= 5, -1 ,  0
       0     0.1       0     100    0.08       0   144.7   0.045       0
   166.3    0.08       0   216.3     0.1       0
Bank Sta=144.7,166.3
XS Rating Curve= 0 ,0
Exp/Cntr=0.3,0.1

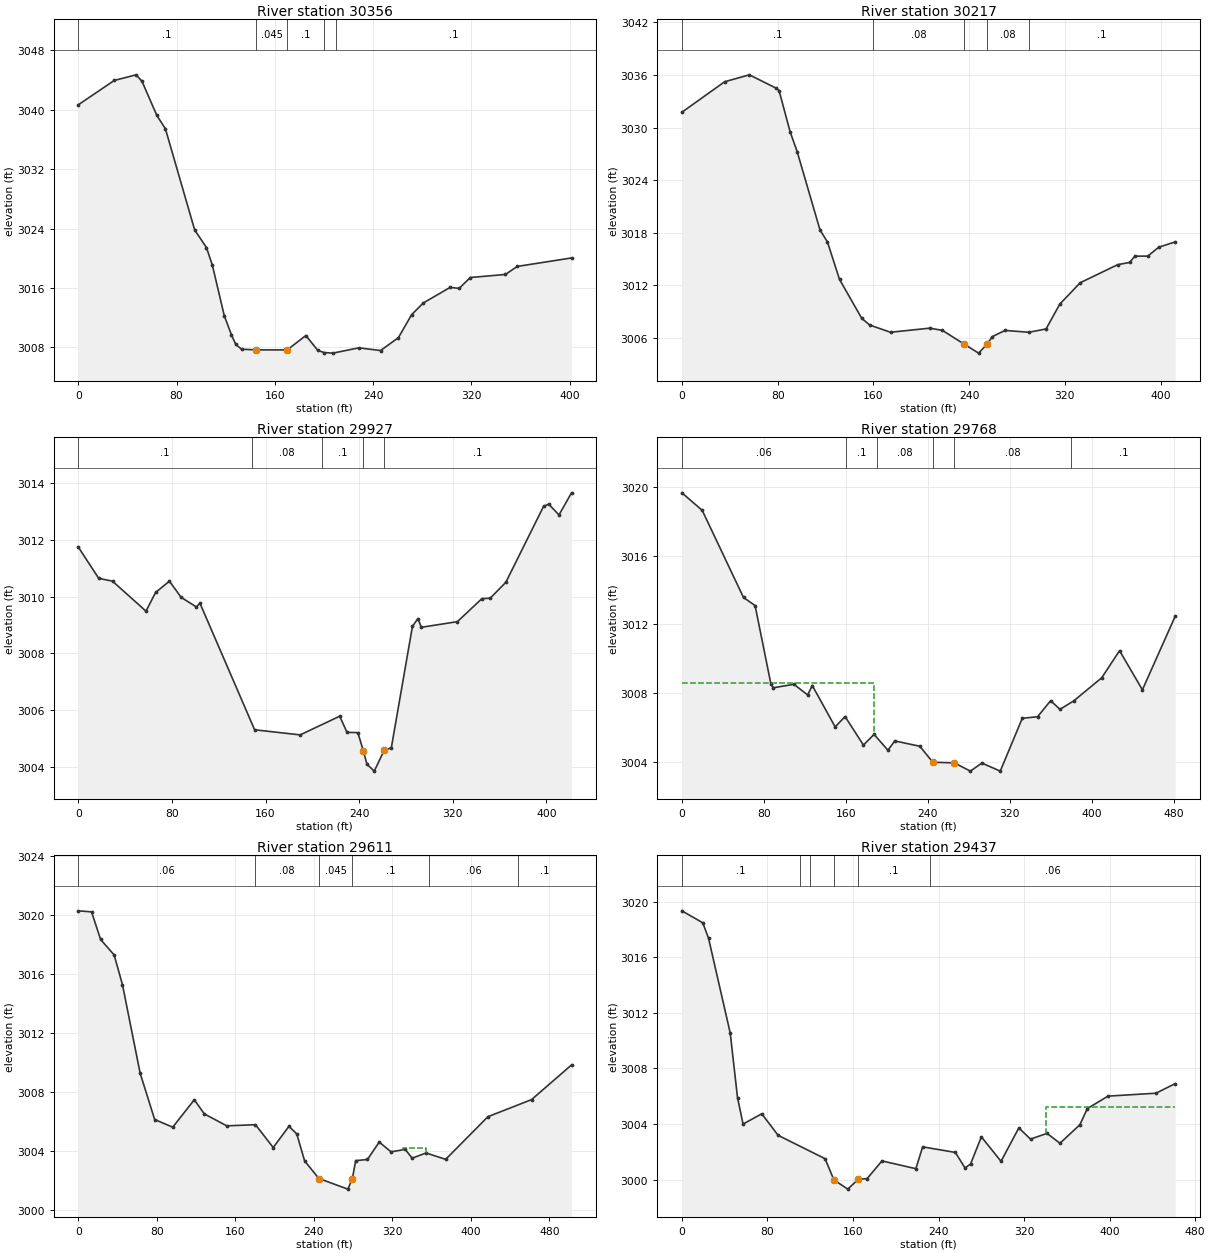
Type RM Length L Ch R = 1 ,30356   ,139.9,139.9,139.9
XS GIS Cut Line= 2
2323012.66808025639494.2086185792323349.24379394639275.337128462
#Sta/Elev= 30
       0 3040.63    29.3 3043.91    47.1 3044.67    51.9  3043.8      64 3039.21
      71  3037.4    94.8  3023.8   104.4 3021.44   109.2 3019.06   118.9 3012.26
   124.7 3009.72   128.2 3008.41     133 3007.76   144.9 3007.68  170.07 3007.67
   185.3 3009.61     195 3007.61     200 3007.32   207.3 3007.24   228.4 3007.95
   246.1 3007.59   260.6 3009.32   271.4 3012.42   280.9 3013.99   302.7 3016.08
   310.1 3015.95   319.1 3017.41   347.7 3017.82   357.3  3018.9   401.5 3020.04
#Mann= 5, -1 ,  0
       0     0.1       0   144.9   0.045       0  170.07     0.1       0
     200    0.08       0     210     0.1       0
Bank Sta=144.9,170.07
XS Rating Curve= 0 ,0
Exp/Cntr(USF)=0,0
Exp/Cntr=0.3,0.1

Type RM Length L Ch R = 1 ,30217   ,289.1,289.1,289.1
XS GIS Cut Line= 2
2323051.88676973639599.6462320462323378.26364751639347.938603055
#Sta/Elev= 30
       0 3031.76    35.7 3035.24    56.4 3036.03      79 3034.49    81.2 3034.23
    90.4 3029.54    96.3 3027.27   115.4 3018.33   121.6 3016.97   131.7 3012.69
   150.3 3008.24     157 3007.48   174.3 3006.66   207.1 3007.13   217.6 3006.88
   235.8 3005.31   247.9 3004.28     2553005.307   259.5 3006.17     270 3006.87
     290 3006.66   304.3 3007.04   315.7 3009.86   332.8 3012.31   364.1 3014.37
   374.2 3014.63   378.4 3015.34   389.3 3015.35   398.4 3016.36   412.2 3016.97
#Mann= 5, -1 ,  0
       0     0.1       0     160    0.08       0   235.8   0.045       0
     255    0.08       0     290     0.1       0
Bank Sta=235.8,255
XS Rating Curve= 0 ,0
Exp/Cntr(USF)=0,0
Exp/Cntr=0.3,0.1

Type RM Length L Ch R = 1 ,29927   ,159.9,159.9,159.9
XS GIS Cut Line= 4
2323143.62201579639657.543299461 2323239.3216678639636.231896611
2323406.63676246639536.0373922462323469.92032026639424.445467568
#Sta/Elev= 30
       0 3011.76    17.5 3010.65    29.3 3010.55    57.9 3009.49    66.1 3010.15
    77.9 3010.55    87.9 3009.98   100.9 3009.64     104 3009.77   150.7  3005.3
   189.6 3005.12   223.4 3005.78   229.6 3005.21   238.9  3005.2   243.6 3004.55
   246.7 3004.08   252.9 3003.84   261.3 3004.57   267.5 3004.67   285.5 3008.95
   290.2 3009.23   293.1 3008.92   323.9 3009.12   344.8 3009.93     352 3009.95
   365.3 3010.51   397.5 3013.19   401.9 3013.27   410.7 3012.89   421.4 3013.67
#Mann= 5, -1 ,  0
       0     0.1       0  148.04    0.08       0  208.04     0.1       0
   243.6   0.045       0   261.3     0.1       0
Bank Sta=243.6,261.3
XS Rating Curve= 0 ,0
Exp/Cntr=0.3,0.1

Type RM Length L Ch R = 1 ,29768   ,157.1,157.1,157.1
XS GIS Cut Line= 2
2323292.16180896639910.8629723752323507.85959055639480.551317646
#Sta/Elev= 30
       0 3019.66    19.8 3018.64    60.1 3013.56    71.4 3013.09    86.9  3008.5
    89.3  3008.3   109.3  3008.5   122.7 3007.88   127.2 3008.43   149.5 3006.02
   159.2 3006.62   177.1 3004.96   187.5 3005.58     201 3004.66   207.7  3005.2
   232.1 3004.89   244.8 3003.96   265.9 3003.92   281.4 3003.44   292.7 3003.91
   310.6 3003.44   332.1 3006.52     347 3006.61   359.8 3007.55   368.8 3007.04
   382.2 3007.53   409.6 3008.88     427 3010.46   449.3 3008.18   481.3 3012.47
#Mann= 6, -1 ,  0
       0    0.06       0     160     0.1       0     190    0.08       0
   244.8   0.045       0   265.9    0.08       0     380     0.1       0
#XS Ineff= 2 , 0
          187.39 3008.56
Permanent Ineff=
       F       F
Bank Sta=244.8,265.9
XS Rating Curve= 0 ,0
Exp/Cntr(USF)=0,0
Exp/Cntr=0.3,0.1

Type RM Length L Ch R = 1 ,29611   ,173.8,173.8,173.8
XS GIS Cut Line= 4
2323322.00645295639929.0333122792323415.39162207639763.663741968
2323563.25147317639763.6637419682323665.39150189639634.286372254
#Sta/Elev= 30
       0 3020.26    13.6 3020.19    22.8 3018.32    36.6 3017.27    45.1 3015.25
    63.1 3009.25    77.9 3006.11    96.3 3005.59   118.3 3007.45   128.5 3006.49
   151.4 3005.68   180.6 3005.76   198.7 3004.21   214.7 3005.65   222.7 3005.13
   230.7  3003.3   245.2 3002.11   274.7 3001.39  279.29 3002.09   282.7 3003.32
   294.7  3003.4   306.7 3004.58   318.7 3003.92   333.2 3004.08   340.2 3003.49
   354.4 3003.84   374.4 3003.41   417.4  3006.3   461.9 3007.46   502.6 3009.81
#Mann= 6, -1 ,  0
       0    0.06       0     180    0.08       0   245.2   0.045       0
  279.29     0.1       0  357.78    0.06       0  447.78     0.1       0
#XS Ineff= 1 ,-1
  330.66  354.353004.188
Permanent Ineff=
       F
Bank Sta=245.2,279.29
XS Rating Curve= 0 ,0
Exp/Cntr(USF)=0,0
Exp/Cntr=0.3,0.1

Type RM Length L Ch R = 1 ,29437   ,121,121,121
XS GIS Cut Line= 3
2323397.62658069640047.5093277152323527.61681346639905.910559587
2323695.40527659639695.379576779
#Sta/Elev= 30
       0 3019.33    19.5 3018.47    24.9 3017.36    45.2 3010.54      52  3005.9
    57.2 3003.99    74.7 3004.73      90 3003.18   133.9  3001.5   142.2 2999.97
   155.2 2999.31   164.8 3000.01   173.3 3000.07   187.1 3001.34   218.8 3000.78
   225.2 3002.35   255.8 3001.95   264.8 3000.83     270 3001.12   280.1 3003.07
   298.5 3001.31   315.1 3003.71   326.1 3002.91   341.5 3003.32   353.6 3002.61
   372.2 3003.94   379.2  3005.1   398.5    3006   443.4 3006.21   461.4  3006.9
#Mann= 6, -1 ,  0
       0     0.1       0     110    0.06       0     120     0.1       0
   142.2   0.045       0   164.8     0.1       0  232.22    0.06       0
#XS Ineff= 2 , 0
                          340.59         3005.24
Permanent Ineff=
       F       F
Bank Sta=142.2,164.8
XS Rating Curve= 0 ,0
Exp/Cntr=0.3,0.1

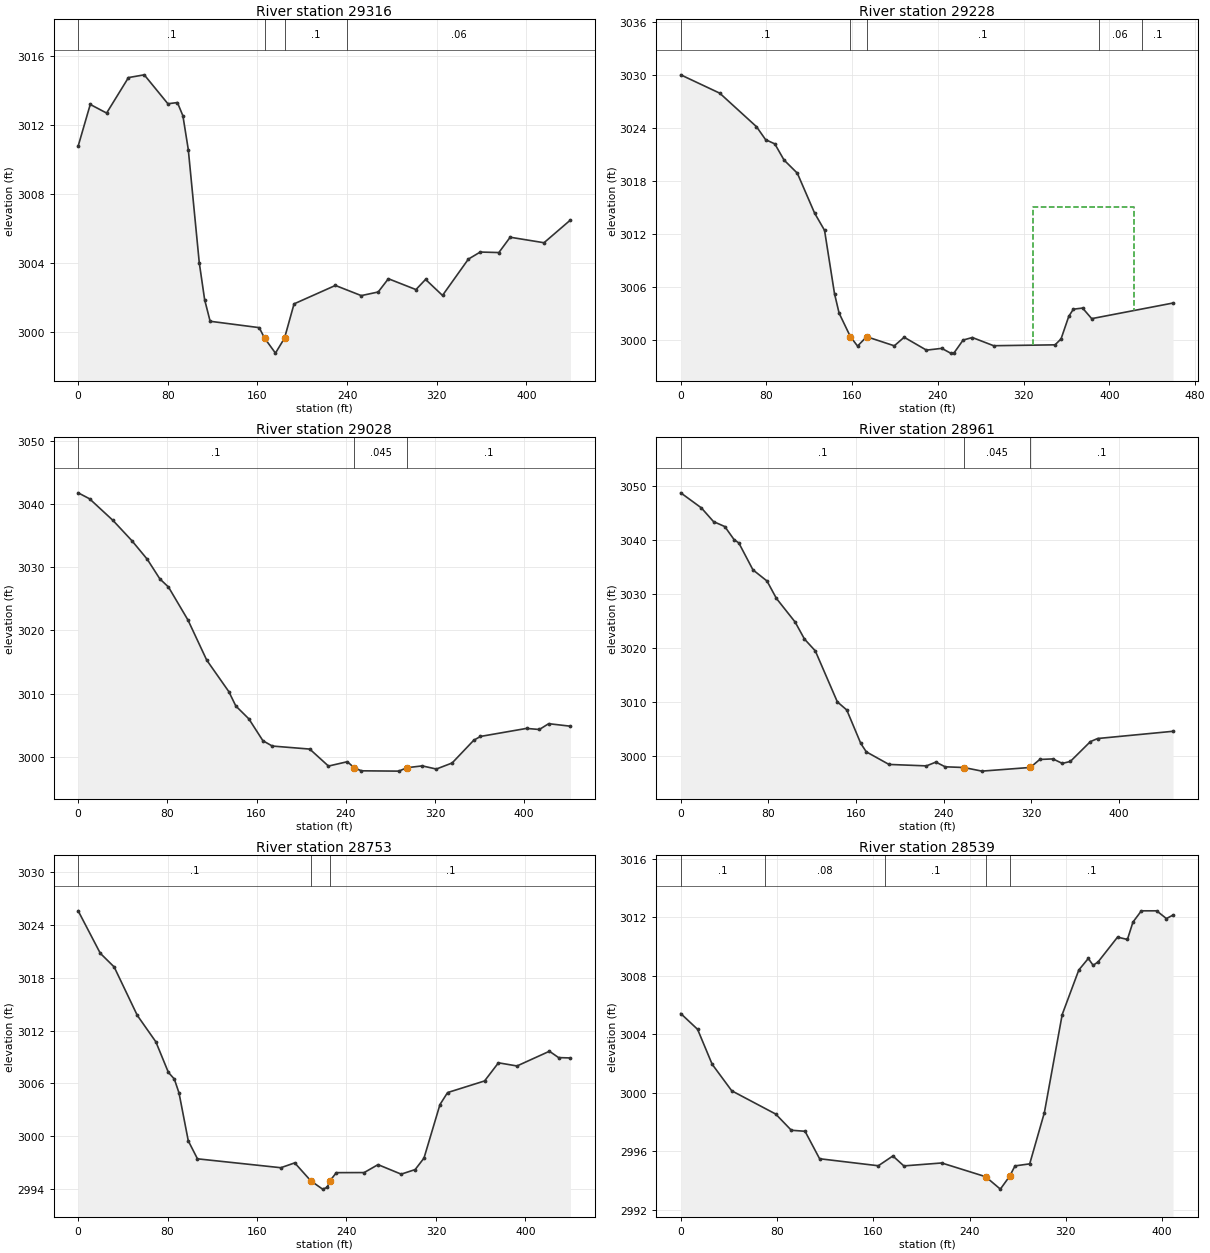
Type RM Length L Ch R = 1 ,29316   ,88.2,88.2,88.2
XS GIS Cut Line= 4
2323514.61336425640070.0838281322323651.77283139639871.640343759
2323634.26311219639805.4925156352323713.05684863639702.379724735
#Sta/Elev= 30
       0 3010.77    10.8 3013.19    25.4 3012.69    44.9 3014.75      59 3014.91
    80.1 3013.23    88.6  3013.3    93.5 3012.53    98.3 3010.57   108.1    3004
   112.9 3001.85   117.8  3000.6   161.6 3000.23   166.4 2999.62   176.1 2998.75
  184.19 2999.62   192.7 3001.61   229.6 3002.68   252.7 3002.09   267.8  3002.3
   276.9 3003.07   301.5 3002.44   310.1 3003.03   325.2  3002.1   348.3 3004.21
   358.9 3004.62   375.5 3004.59   385.6 3005.48   415.8 3005.16   439.4 3006.48
#Mann= 4, -1 ,  0
       0     0.1       0   166.4   0.045       0  184.19     0.1       0
     240    0.06       0
Bank Sta=166.4,184.19
XS Rating Curve= 0 ,0
Exp/Cntr(USF)=0,0
Exp/Cntr=0.3,0.1

Type RM Length L Ch R = 1 ,29228   ,199.1,199.1,199.1
XS GIS Cut Line= 2
2323616.69562366640135.1371552812323781.69057663639706.391146091
#Sta/Elev= 30
       0 3030.06    36.4 3027.98    70.7 3024.18    79.2 3022.71    87.8 3022.23
    96.4  3020.4   108.8 3018.91   124.9 3014.39   134.2 3012.43   143.5 3005.25
   147.8 3003.04   158.3 3000.38     165 2999.31   173.5 3000.37   199.3 2999.34
   208.5 3000.31   229.3 2998.85   243.6 2999.05   251.8 2998.51     255 2998.53
   263.5 2999.99   272.1 3000.28     292 2999.35   349.3 2999.45   354.9 3000.12
   362.1 3002.68   366.4 3003.49     375 3003.62   383.5 3002.42   459.4 3004.19
#Mann= 5, -1 ,  0
       0     0.1       0   158.3   0.045       0   173.5     0.1       0
     390    0.06       0     430     0.1       0
#XS Ineff= 1 ,-1
  328.78  422.59 3015.05
Permanent Ineff=
       F
Bank Sta=158.3,173.5
XS Rating Curve= 0 ,0
Exp/Cntr(USF)=0,0
Exp/Cntr=0.3,0.1

Type RM Length L Ch R = 1 ,29028   ,67.3,67.3,67.3
XS GIS Cut Line= 2
2323715.97513516640146.9320402182323851.18907795639726.698779193
#Sta/Elev= 30
       0 3041.77    10.2 3040.83    31.3 3037.39    48.1 3034.21      62 3031.25
    73.3 3028.14      81 3026.86    98.5 3021.63   115.3 3015.29   135.1 3010.31
   141.4 3008.03   153.1 3005.99   165.7 3002.53   174.1 3001.69   207.7 3001.21
   224.5 2998.52   241.4 2999.21  247.65 2998.24     254 2997.77   287.6 2997.72
  294.77 2998.26   308.6 2998.55   321.2 2998.05   335.4 2999.01   354.8 3002.61
   360.8 3003.21   402.1 3004.48   413.6 3004.31     422 3005.23   441.5 3004.83
#Mann= 3, -1 ,  0
       0     0.1       0  247.65   0.045       0  294.77     0.1       0
Bank Sta=247.65,294.77
XS Rating Curve= 0 ,0
Exp/Cntr(USF)=0,0
Exp/Cntr=0.3,0.1

Type RM Length L Ch R = 1 ,28961   ,208.5,208.5,208.5
XS GIS Cut Line= 3
2323755.19657086640178.7222841372323834.89523792639969.399190991
2323914.30561825 639758.66395425
#Sta/Elev= 30
       0 3048.71    18.8 3045.93    29.9 3043.39    40.2 3042.47    48.7 3040.05
      53 3039.44    65.9 3034.46    78.7  3032.4    87.3 3029.18   104.4  3024.8
   112.9 3021.66   122.8 3019.47   142.9 3010.04   151.5 3008.54   164.3 3002.35
   169.3  3000.8     190 2998.47   224.2  2998.2   232.8  2998.9   241.3 2998.03
   258.4  2997.9   274.8 2997.23     319 2997.91   327.6 2999.39   339.6 2999.49
   348.2 2998.66   355.5 2999.02   373.8 3002.69   380.4 3003.26   449.2  3004.6
#Mann= 3, -1 ,  0
       0     0.1       0   258.4   0.045       0     319     0.1       0
Bank Sta=258.4,319
XS Rating Curve= 0 ,0
Exp/Cntr=0.3,0.1

Type RM Length L Ch R = 1 ,28753   ,213.5,213.5,213.5
XS GIS Cut Line= 2
2323944.47292182640208.2914702772324058.37416355 639782.96558108
#Sta/Elev= 30
       0 3025.59    19.8 3020.77    32.2 3019.22    52.9 3013.72    69.5 3010.72
    80.7 3007.25      86  3006.5    90.2 3004.92    98.5 2999.48   106.7 2997.44
   181.3 2996.43   193.7 2996.98   208.1 2994.94   218.6    2994   222.7 2994.19
   225.4 2994.97   230.9 2995.87   255.8 2995.88   268.2 2996.78   288.9  2995.7
   301.4 2996.22   309.3 2997.52   323.6  3003.6   330.4 3004.96   363.5 3006.28
   375.9 3008.34   392.5 3007.98   421.5 3009.65   429.7 3008.93   440.3 3008.89
#Mann= 3, -1 ,  0
       0     0.1       0   208.1   0.045       0   225.4     0.1       0
Bank Sta=208.1,225.4
XS Rating Curve= 0 ,0
Exp/Cntr(USF)=0,0
Exp/Cntr=0.3,0.1

Type RM Length L Ch R = 1 ,28539   ,358.1,358.1,358.1
XS GIS Cut Line= 2
2324115.82131141640234.9554048132324185.19145223639831.741461339
#Sta/Elev= 30
       0 3005.42      14 3004.34    26.1 3001.95    42.4 3000.13    78.9 2998.54
    91.9 2997.43   103.3 2997.36   115.4 2995.48   164.2    2995   176.3 2995.67
   185.4 2994.99   216.9 2995.19   253.4 2994.25   265.6  2993.4  273.22 2994.27
   277.8 2994.99     290 2995.13   302.2 2998.64     317 3005.35   330.8  3008.4
   338.7 3009.19   342.7 3008.72   346.8 3008.95     363 3010.65   371.2 3010.49
   375.8 3011.68   382.8 3012.45   395.5 3012.45   403.6 3011.92   409.1 3012.16
#Mann= 5, -1 ,  0
       0     0.1       0      70    0.08       0     170     0.1       0
   253.4   0.045       0  273.22     0.1       0
Bank Sta=253.4,273.22
XS Rating Curve= 0 ,0
Exp/Cntr(USF)=0,0
Exp/Cntr=0.3,0.1

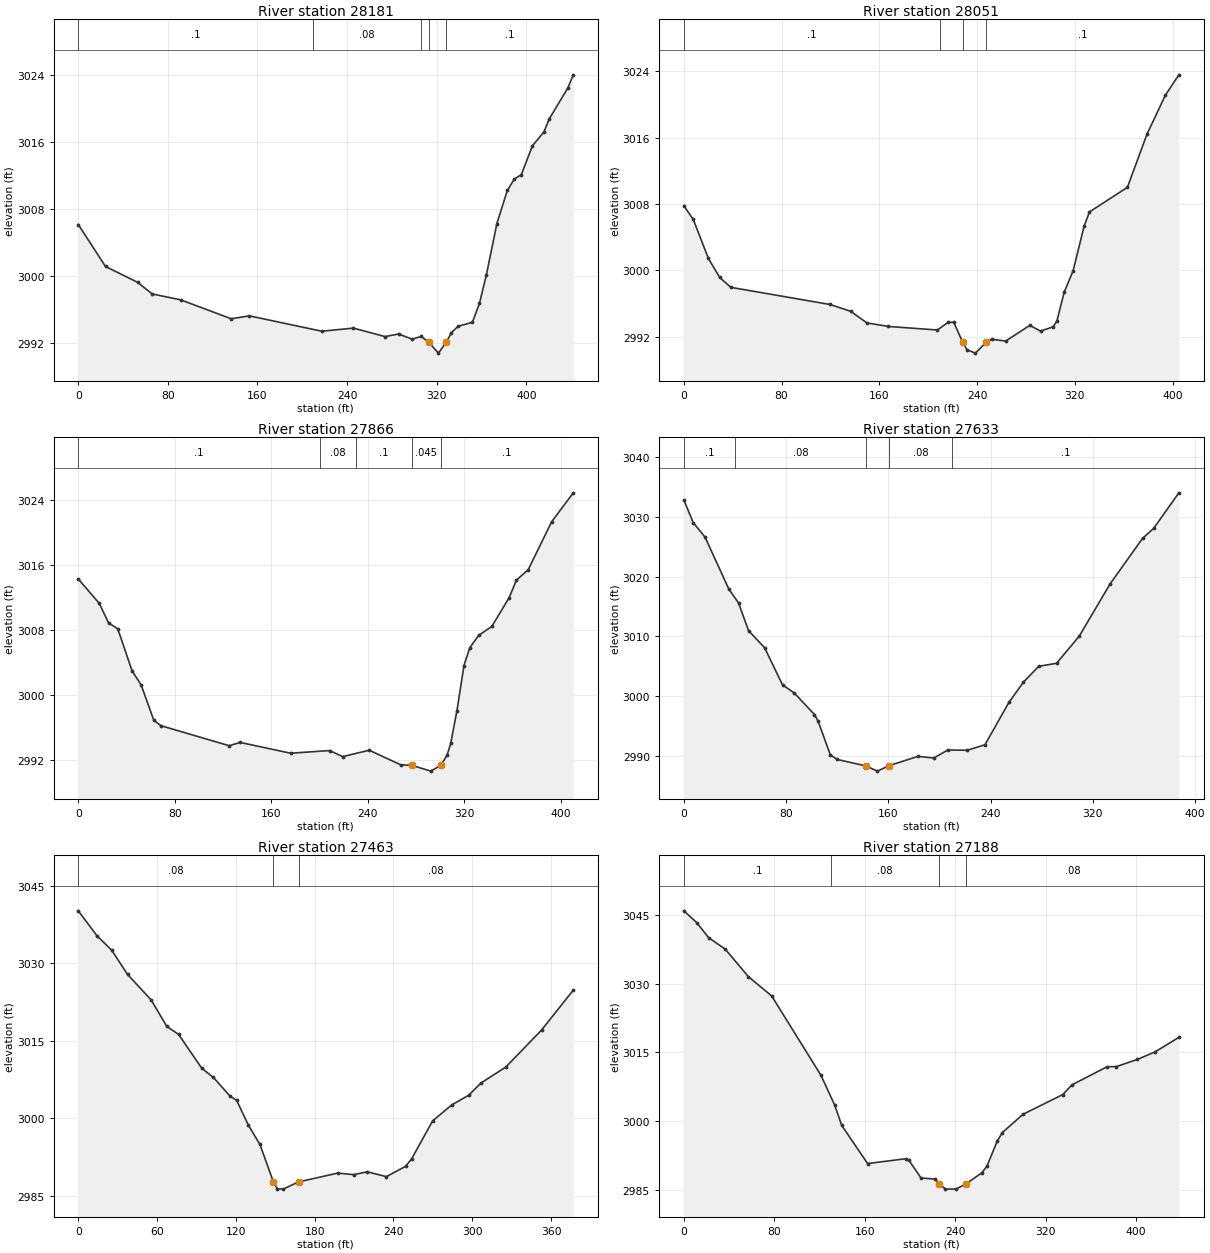
Type RM Length L Ch R = 1 ,28181   ,130.3,130.3,130.3
XS GIS Cut Line= 5
2324237.97844515640268.5273716532324274.30948739640143.730076777
2324298.66758666639969.5244252582324313.36911842639947.857515293
 2324351.0262274639844.524454944
#Sta/Elev= 30
       0 3006.15    24.3 3001.15    52.9 2999.27      66 2997.88    91.6 2997.17
   136.6 2994.92   152.7 2995.27   217.4 2993.44   245.6 2993.81   273.9  2992.8
     286 2993.11   298.1 2992.49   306.3 2992.82     313 2992.11   321.6 2990.83
  328.52 2992.13   333.2 2993.28   339.2 2994.03   351.9  2994.5   358.2 2996.75
   364.4 3000.16   373.8 3006.27   383.1 3010.21   389.4 3011.57   395.6 3012.09
   405.5 3015.52   415.8 3017.18   420.6 3018.75   437.1 3022.41     442 3023.98
#Mann= 5, -1 ,  0
       0     0.1       0  209.98    0.08       0  305.88     0.1       0
     313   0.045       0  328.52     0.1       0
Bank Sta=313,328.52
XS Rating Curve= 0 ,0
Exp/Cntr(USF)=0,0
Exp/Cntr=0.3,0.1

Type RM Length L Ch R = 1 ,28051   ,185.2,185.2,185.2
XS GIS Cut Line= 2
2324271.42233897640284.0915073582324447.49229324639919.305690496
#Sta/Elev= 30
       0  3007.8     7.7 3006.13    20.1 3001.43    29.3 2999.13    38.5 2997.94
   119.6 2995.87   136.5 2995.05   149.8 2993.65   167.4 2993.22   207.5 2992.79
   216.4 2993.73   220.9 2993.72  228.11 2991.34   231.8  2990.4   238.6    2990
   247.5 2991.33     252 2991.67   263.4 2991.46   283.1 2993.35   291.9 2992.66
   302.3 2993.18   305.3 2993.89   311.3 2997.37   318.6 2999.96   327.5 3005.29
   331.9 3007.04     363 3010.01     379 3016.42   394.1 3021.14   405.1 3023.59
#Mann= 4, -1 ,  0
       0     0.1       0     210    0.08       0  228.11   0.045       0
   247.5     0.1       0
Bank Sta=228.11,247.5
XS Rating Curve= 0 ,0
Exp/Cntr(USF)=0,0
Exp/Cntr=0.3,0.1

Type RM Length L Ch R = 1 ,27866   ,232.9,232.9,232.9
XS GIS Cut Line= 4
2324313.55065181640319.0953166472324498.85752147640151.807640987
2324558.06621869640119.6050105532324635.11660312640067.331116647
#Sta/Elev= 30
       0 3014.29    17.4 3011.28    25.1 3008.86    32.7 3008.15    44.6 3002.94
      52 3001.24    62.6 2996.85    68.5 2996.18     125 2993.71   134.2 2994.11
     176 2992.78   208.3 2993.11   219.1 2992.36   241.1 2993.15   267.3 2991.34
   276.3 2991.29   292.1 2990.57  300.66  2991.3   305.8 2992.62   308.6 2993.99
   313.8 2998.04   319.6  3003.6   324.4  3005.8   331.8 3007.33   342.7 3008.44
     357 3011.98   363.1 3014.15   372.8 3015.43   392.3 3021.37   410.2 3024.93
#Mann= 5, -1 ,  0
       0     0.1       0     200    0.08       0     230     0.1       0
   276.3   0.045       0  300.66     0.1       0
Bank Sta=276.3,300.66
XS Rating Curve= 0 ,0
Exp/Cntr=0.3,0.1

Type RM Length L Ch R = 1 ,27633   ,169.7,169.7,169.7
XS GIS Cut Line= 2
  2324538.229443640447.429708967 2324736.9459922640115.031117572
#Sta/Elev= 30
       0 3032.84     7.3 3029.06    16.6 3026.61    35.2 3017.91    42.8 3015.59
    50.6 3010.95    63.2 3008.08    77.2 3001.87    86.5 3000.48   102.2 2996.89
   105.1 2995.75   114.5 2990.19   119.7 2989.38   142.4 2988.28   151.5 2987.41
   160.6 2988.33   183.1 2989.88   195.6 2989.61   206.5 2990.95   221.8 2990.91
   235.6 2991.83   254.3 2998.91   265.6 3002.29   277.6 3004.97   291.6 3005.48
   309.3    3010   333.5 3018.78   358.9 3026.41   367.6 3028.09   387.3 3034.04
#Mann= 5, -1 ,  0
       0     0.1       0      40    0.08       0   142.4   0.045       0
   160.6    0.08       0     210     0.1       0
Bank Sta=142.4,160.6
XS Rating Curve= 0 ,0
Exp/Cntr(USF)=0,0
Exp/Cntr=0.3,0.1

Type RM Length L Ch R = 1 ,27463   ,274.8,274.8,274.8
XS GIS Cut Line= 3
2324670.98507239 640554.005555442324755.48320571640376.954695782
2324845.35897034640220.182115817
#Sta/Elev= 30
       0 3040.19    14.2 3035.36    25.5 3032.54    37.5 3027.86    55.5 3022.92
    67.4 3017.78    76.3 3016.26      94 3009.68   102.9 3007.89   115.5 3004.29
   120.6 3003.45   129.4  2998.7   138.3 2994.91   148.5 2987.68   151.6 2986.31
     156 2986.25   167.72987.649   197.6 2989.36   209.8 2989.06     220 2989.61
   234.6 2988.67   249.3 2990.69   253.9 2992.17   269.8 2999.48   284.4 3002.58
   297.4 3004.47   306.6 3006.82   325.5 3009.91   352.7 3017.07   376.9 3024.83
#Mann= 3, -1 ,  0
       0    0.08       0   148.5   0.045       0   167.7    0.08       0
Bank Sta=148.5,167.7
XS Rating Curve= 0 ,0
Exp/Cntr=0.3,0.1

Type RM Length L Ch R = 1 ,27188   ,233.4,233.4,233.4
XS GIS Cut Line= 2
2324746.30945346640641.0907350842325128.42807033640426.985362204
#Sta/Elev= 30
       0 3045.81    11.3 3043.27    21.9 3039.98    36.6 3037.48    57.2 3031.47
    77.7  3027.3   121.4    3010   133.5 3003.54   139.7 2999.14   162.6 2990.84
   196.2 2991.89   199.3 2991.51   209.9 2987.69   222.2 2987.47   226.22986.438
   231.4 2985.31   240.6 2985.28   249.7 2986.42   263.5  2988.8   268.1 2990.22
   277.2 2995.67   281.8 2997.59   300.2 3001.57   335.3 3005.85   343.5 3007.97
   374.5  3011.9   382.7 3011.93   401.4  3013.5   417.2 3015.16     438 3018.29
#Mann= 4, -1 ,  0
       0     0.1       0     130    0.08       0   226.2   0.045       0
   249.7    0.08       0
Bank Sta=226.2,249.7
XS Rating Curve= 0 ,0
Exp/Cntr(USF)=0,0
Exp/Cntr=0.3,0.1