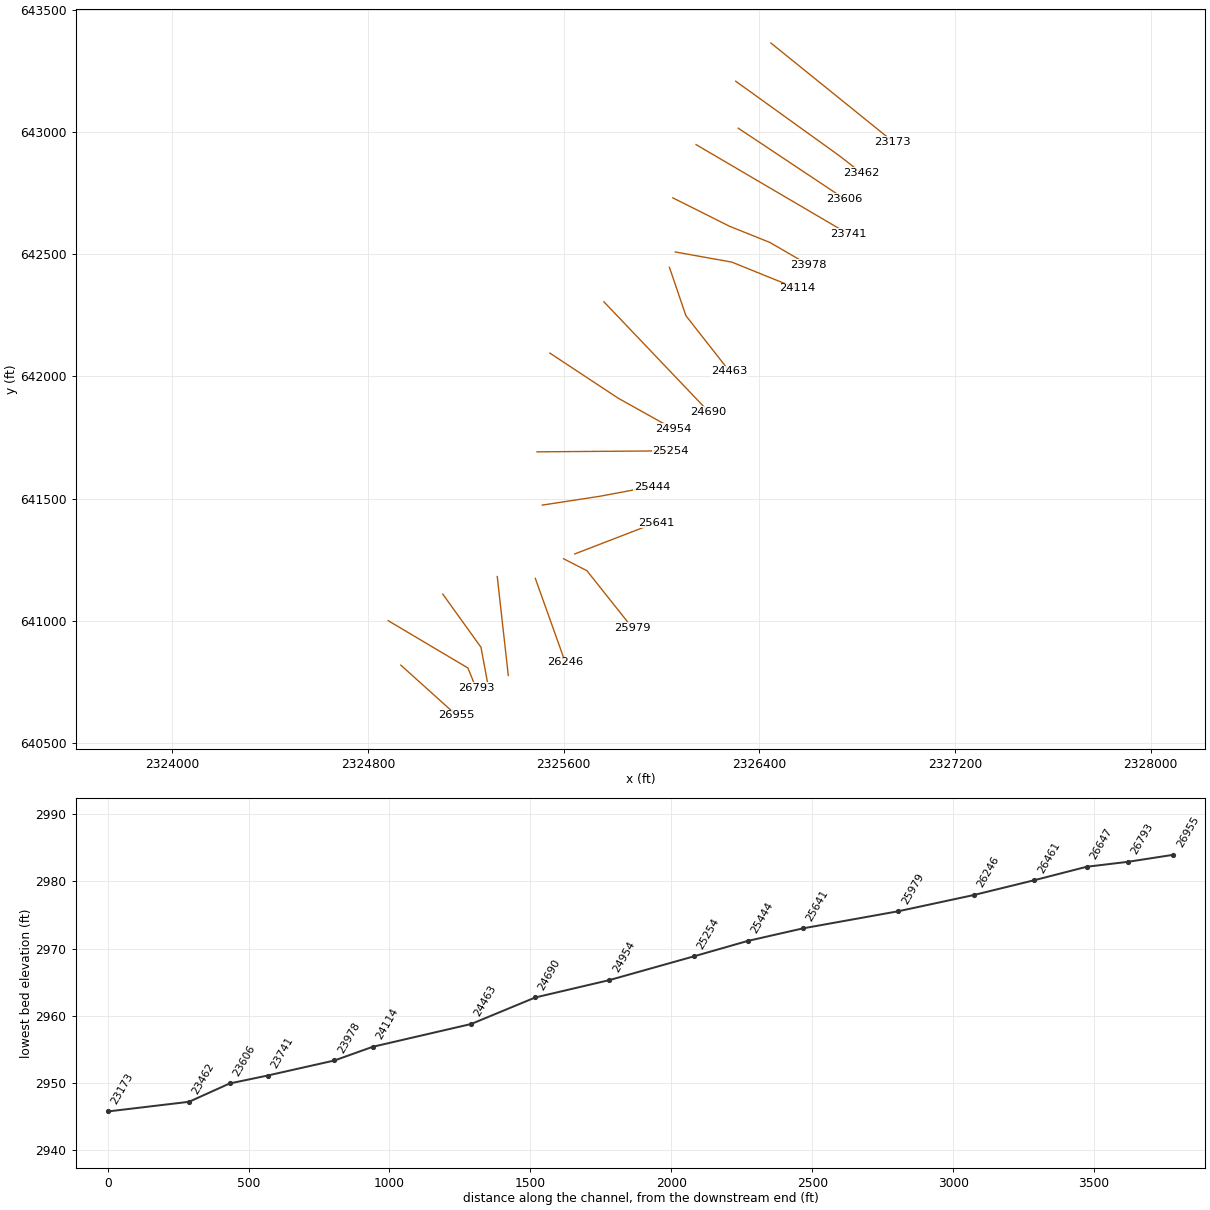
HEC-RAS study WFKGLADYFK.prj: WFKGLADYFK

--- WFKGLADYFK.g01 (geometry) --- (continued)

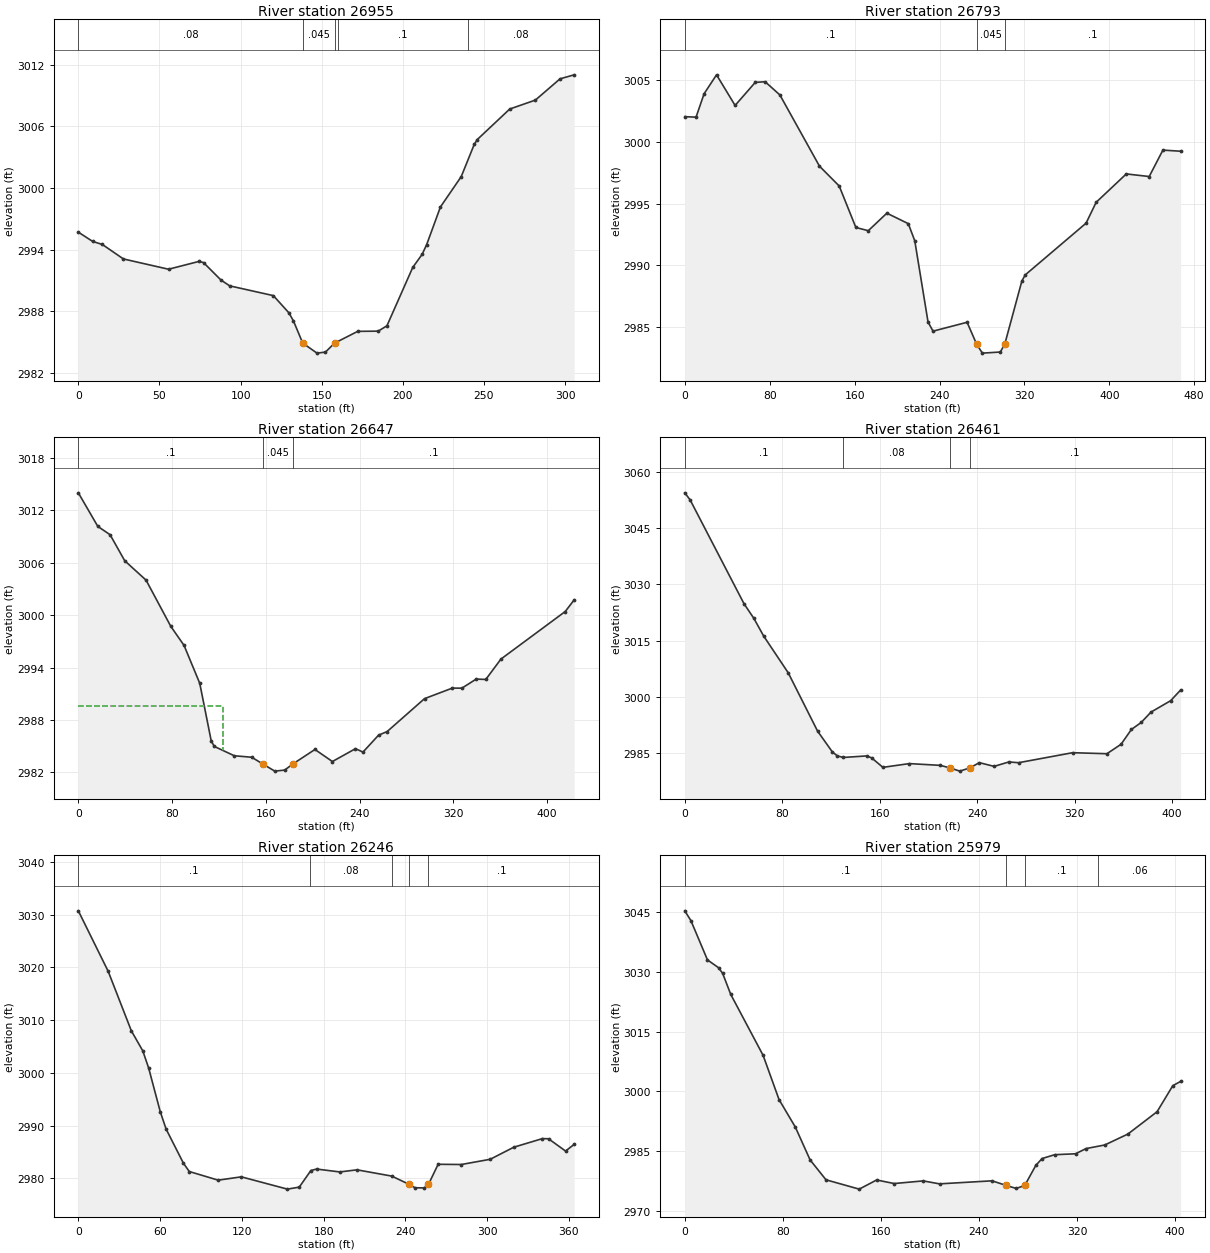
Type RM Length L Ch R = 1 ,26955   ,162.2,162.2,162.2
XS GIS Cut Line= 2
2324934.83295166640819.0898101842325161.93956968640614.632715629
#Sta/Elev= 30
       0 2995.71     8.8 2994.81    14.8 2994.51    27.8  2993.1    55.6  2992.1
    74.6 2992.87    77.2 2992.74    87.9 2991.05    93.3 2990.48   120.2 2989.53
   129.8 2987.85   132.6 2987.06   138.3 2984.91   147.1 2983.93   152.3 2984.03
   157.9  2984.9   172.2 2986.05   184.8 2986.07   190.2 2986.59   206.1 2992.27
   211.9 2993.55   214.7  2994.5   223.2 2998.17     236 3001.12     244 3004.25
   245.9 3004.73   265.9  3007.7   281.7 3008.57   296.9 3010.64   305.6 3011.03
#Mann= 5, -1 ,  0
       0    0.08       0   138.3   0.045       0   157.9    0.08       0
     160     0.1       0     240    0.08       0
Bank Sta=138.3,157.9
XS Rating Curve= 0 ,0
Exp/Cntr=0.3,0.1

Type RM Length L Ch R = 1 ,26793   ,145.6,145.6,145.6
XS GIS Cut Line= 3
 2324883.0985819641001.0290226422325208.97391163640807.449349161
2325242.04782569640725.737326183
#Sta/Elev= 30
       0 3002.04    10.6    3002    18.2  3003.9    29.9 3005.43    47.4 3002.95
    66.4 3004.82    75.7 3004.87    89.6  3003.8   126.9 2998.03   145.5 2996.42
   161.2 2993.06   172.9  2992.8   190.4 2994.22   210.6 2993.37   216.7 2991.98
   229.2  2985.4   233.9 2984.66     266 2985.38     275  2983.6   280.4 2982.88
   297.3 2982.97   301.5 2983.61   317.6 2988.72   320.8 2989.22   378.1 2993.41
   387.6  2995.1     416  2997.4   437.6 2997.19   450.5 2999.33   467.2 2999.24
#Mann= 3, -1 ,  0
       0     0.1       0     275   0.045       0   301.5     0.1       0
Bank Sta=275,301.5
XS Rating Curve= 0 ,0
Exp/Cntr(USF)=0,0
Exp/Cntr=0.3,0.1

Type RM Length L Ch R = 1 ,26647   ,185.9,185.9,185.9
XS GIS Cut Line= 3
2325106.48045046641109.3044154722325262.47583143640892.079658673
 2325290.8804902 640739.01391966
#Sta/Elev= 30
       0 3014.02    16.6 3010.18    27.1 3009.22    39.6 3006.24    57.8 3004.02
    78.9 2998.73    90.2 2996.55   103.6 2992.21   113.4 2985.61     116 2984.98
   133.1 2983.91   147.9 2983.74   157.7 2982.95   167.6 2982.15   176.1 2982.27
  182.86 2982.95   201.9 2984.63   216.8 2983.25   236.5 2984.72   242.9 2984.33
   256.2 2986.27   263.5 2986.68   295.4 2990.45   319.2 2991.66   327.3 2991.65
   339.5 2992.69   347.7 2992.65   360.6 2994.98   415.5 3000.43   423.1 3001.76
#Mann= 3, -1 ,  0
       0     0.1       0   157.7   0.045       0  182.86     0.1       0
#XS Ineff= 2 , 0
           123.8 2989.59
Permanent Ineff=
       F       F
Bank Sta=157.7,182.86
XS Rating Curve= 0 ,0
Exp/Cntr(USF)=0,0
Exp/Cntr=0.3,0.1

Type RM Length L Ch R = 1 ,26461   ,214.6,214.6,214.6
XS GIS Cut Line= 2
2325328.90314266641181.5095253432325373.97809432640776.978144771
#Sta/Elev= 30
       0 3054.48     4.4 3052.58    48.6 3024.86    56.7 3020.95    64.7 3016.25
    84.9 3006.41     109 2990.83   121.1 2985.29   125.1 2984.25     130  2983.8
   149.2 2984.21   153.3 2983.71   162.6 2981.16   184.3 2982.16   209.7 2981.69
   217.7 2981.01   225.7 2980.15   233.92980.999   241.8 2982.41   253.9 2981.42
     266  2982.6     274  2982.4   318.3 2985.07   346.5  2984.8   358.1 2987.32
   366.6 2991.28   374.6 2993.14   382.7 2995.92   398.8 2998.96     407 3001.81
#Mann= 4, -1 ,  0
       0     0.1       0     130    0.08       0   217.7   0.045       0
   233.9     0.1       0
Bank Sta=217.7,233.9
XS Rating Curve= 0 ,0
Exp/Cntr=0.3,0.1

Type RM Length L Ch R = 1 ,26246   ,267.7,267.7,267.7
XS GIS Cut Line= 2
 2325484.4102893641173.8088980782325606.78418784640831.161982176
#Sta/Elev= 30
       0 3030.73    21.9 3019.26    38.9 3007.97    47.3 3004.17    51.6 3000.91
    60.1 2992.64    64.4 2989.34    77.1 2982.87    81.4 2981.29   102.6 2979.65
   119.6 2980.28   153.4 2977.95   162.1 2978.33   170.6 2981.47   174.8 2981.76
   191.8 2981.21   204.5 2981.61     230 2980.42   242.8 2978.84     247 2978.21
   253.8 2978.18   256.9 2978.85     264 2982.66     281 2982.62   302.2 2983.61
   319.5  2985.9   340.5 2987.53     345  2987.5   357.5 2985.17   363.8 2986.44
#Mann= 5, -1 ,  0
       0     0.1       0     170    0.08       0     230     0.1       0
   242.8   0.045       0   256.9     0.1       0
Bank Sta=242.8,256.9
XS Rating Curve= 0 ,0
Exp/Cntr(USF)=0,0
Exp/Cntr=0.3,0.1

Type RM Length L Ch R = 1 ,25979   ,337.7,337.7,337.7
XS GIS Cut Line= 3
2325599.70897549641254.2882674972325695.35500078641205.309080085
2325880.16680461640972.703918177
#Sta/Elev= 30
       0 3045.21       5 3042.75    18.5 3032.92    27.5 3030.98    30.9 3029.54
    37.5 3024.28    63.9 3009.02    76.9 2997.95    90.2 2991.06   102.2 2982.87
   115.2 2977.87   142.3 2975.54   156.5 2977.83   170.8 2976.94   194.5  2977.6
   207.8 2976.86   250.7 2977.62   261.9 2976.49   270.4 2975.71  277.36 2976.47
   286.4  2981.5   291.5  2983.2   301.8 2984.16   318.8 2984.39   327.3 2985.69
   342.6 2986.59   361.5 2989.33   385.3 2994.92   398.1 3001.43   404.5 3002.51
#Mann= 4, -1 ,  0
       0     0.1       0   261.9   0.045       0  277.36     0.1       0
  337.46    0.06       0
Bank Sta=261.9,277.36
XS Rating Curve= 0 ,0
Exp/Cntr=0.3,0.1

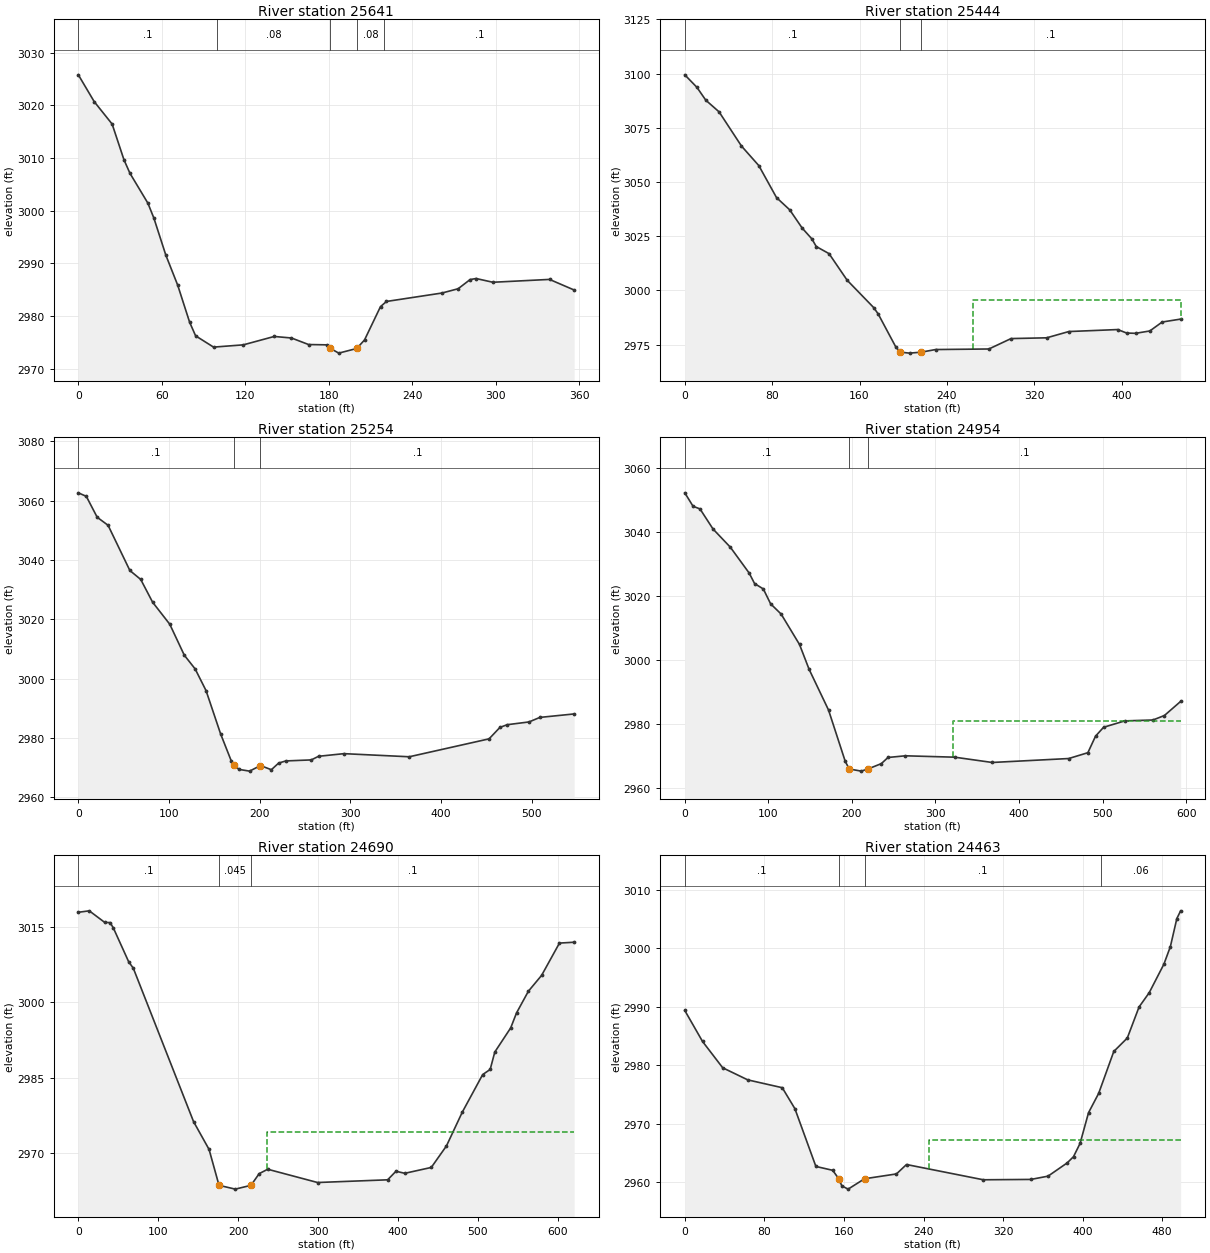
Type RM Length L Ch R = 1 ,25641   ,197.3,197.3,197.3
XS GIS Cut Line= 2
2325645.53592238641273.747581883 2325977.9850134641402.240175346
#Sta/Elev= 30
       0 3025.78    11.4  3020.7    24.3 3016.44    32.8 3009.67    37.1 3007.11
      50 3001.44    54.3 2998.61    62.9 2991.58    71.4 2985.91      80 2978.86
    84.3 2976.28    97.2 2974.14   118.6 2974.57   140.8 2976.16   153.2 2975.87
   165.5 2974.63   178.7 2974.57     181 2973.92   187.2    2973   200.1 2973.88
   205.7 2975.49   217.2 2981.82   221.5  2982.8   261.4  2984.4     273 2985.21
   281.6 2986.95   285.9 2987.15     298 2986.44   338.7 2986.98   356.4 2984.97
#Mann= 5, -1 ,  0
       0     0.1       0     100    0.08       0     181   0.045       0
   200.1    0.08       0     220     0.1       0
Bank Sta=181,200.1
XS Rating Curve= 0 ,0
Exp/Cntr(USF)=0,0
Exp/Cntr=0.3,0.1

Type RM Length L Ch R = 1 ,25444   ,190.1,190.1,190.1
XS GIS Cut Line= 3
2325513.15844683641473.6196212682325745.18521473641509.216519805
2325960.77659278641549.476485756
#Sta/Elev= 30
       0 3099.43    11.1 3093.66    19.2 3087.76    31.4 3082.35    51.9  3066.6
    67.8 3057.57      84 3042.83    96.1 3037.18   107.5 3028.77   116.4 3023.78
   120.4 3020.26   132.1 3016.99   148.7 3004.73     173 2992.11   177.1 2989.19
   193.3 2973.91   197.3 2971.58   205.8 2971.12   216.3 2971.55   229.7 2972.77
   278.5 2973.03   298.8 2977.83   331.4 2978.18   351.7 2981.07   396.5 2981.99
   404.6 2980.39   412.8 2980.25   425.9 2981.34   437.2 2985.46   454.1 2986.81
#Mann= 3, -1 ,  0
       0     0.1       0   197.3   0.045       0   216.3     0.1       0
#XS Ineff= 2 , 0
                          264.27          2995.7
Permanent Ineff=
       F       F
Bank Sta=197.3,216.3
XS Rating Curve= 0 ,0
Exp/Cntr=0.3,0.1

Type RM Length L Ch R = 1 ,25254   ,299.9,299.9,299.9
XS GIS Cut Line= 2
2325491.36800052641691.4371839972326037.97141398641695.516313949
#Sta/Elev= 30
       0 3062.66     8.8 3061.47    20.8 3054.42    32.8 3051.71    56.8 3036.48
    68.8 3033.45    81.9 3025.78   100.8 3018.36   116.8 3007.93   128.8 3003.28
   140.8 2995.98   156.8 2981.43   168.8 2972.12   171.52970.894   177.2 2969.42
   188.8 2968.84   200.8 2970.72   212.8 2969.31   220.8 2971.55   228.8 2972.28
   256.8 2972.62   264.8 2973.84   292.8 2974.73   364.8 2973.68   452.8 2979.72
   464.8 2983.59   472.8 2984.49   496.8 2985.42   508.8 2986.95   546.6 2988.12
#Mann= 3, -1 ,  0
       0     0.1       0   171.5   0.045       0   200.8     0.1       0
Bank Sta=171.5,200.8
XS Rating Curve= 0 ,0
Exp/Cntr(USF)=0,0
Exp/Cntr=0.3,0.1

Type RM Length L Ch R = 1 ,24954   ,263.5,263.5,263.5
XS GIS Cut Line= 3
2325543.94187792642095.2082219172325823.48774535641910.584554167
2326049.13629851641784.614802949
#Sta/Elev= 30
       0 3052.12     9.9 3047.92    18.2  3047.1    33.8 3040.83    54.5 3035.16
      77 3027.11    83.5 3023.82      94 3022.13   102.7  3017.5   115.3  3014.3
   137.3 3004.81   148.8 2997.05     172 2984.38     192 2968.37   196.8 2965.98
   211.2 2965.31   219.5 2966.01   235.2 2967.65   243.2 2969.57   263.9 2970.09
     323 2969.66   367.9 2968.01   459.5 2969.24   482.4 2971.06   491.6 2976.23
   501.2 2978.99   526.6 2980.98   560.3 2981.26     574 2982.66   593.4 2987.05
#Mann= 3, -1 ,  0
       0     0.1       0   196.8   0.045       0   219.5     0.1       0
#XS Ineff= 2 , 0
                           321.2         2980.85
Permanent Ineff=
       F       F
Bank Sta=196.8,219.5
XS Rating Curve= 0 ,0
Exp/Cntr=0.3,0.1

Type RM Length L Ch R = 1 ,24690   ,227.3,227.3,227.3
XS GIS Cut Line= 2
2325764.76164155642305.0734603322326192.64197778641855.716504905
#Sta/Elev= 30
       0    3018    13.7 3018.29      33 3015.98    39.8 3015.94      44 3014.81
      63 3008.12    68.8 3006.83   144.2  2976.2   163.6 2970.65  176.06 2963.48
   196.4 2962.72  216.07 2963.48   226.3 2965.81     237 2966.69   299.4 2964.04
   387.1 2964.58   397.5 2966.29   408.6 2965.88   441.7 2967.05   460.7 2971.35
   480.5 2978.09     506 2985.59   515.4 2986.62   521.2  2990.1   541.1 2994.92
   548.4 2997.91   563.2 3002.23   579.8 3005.41   602.1 3011.85   620.5 3012.02
#Mann= 3, -1 ,  0
       0     0.1       0  176.06   0.045       0  216.07     0.1       0
#XS Ineff= 2 , 0
                          236.63          2974.1
Permanent Ineff=
       F       F
Bank Sta=176.06,216.07
XS Rating Curve= 0 ,0
Exp/Cntr(USF)=0,0
Exp/Cntr=0.3,0.1

Type RM Length L Ch R = 1 ,24463   ,349.5,349.5,349.5
XS GIS Cut Line= 3
2326032.63485829642445.9931888732326099.87409526642248.233952134
2326278.52345719642020.314438904
#Sta/Elev= 30
       0 2989.34    17.8 2984.05    38.1 2979.54    63.3 2977.47      98 2976.13
   110.7 2972.54   131.8 2962.66   148.7    2962   154.8 2960.55   157.9 2959.33
   164.2 2958.78   180.72960.552   212.8 2961.38   222.9 2962.99   300.1 2960.38
     348 2960.44   365.2    2961   384.4 2963.26   390.8 2964.33   397.4  2966.6
   405.9 2971.85   416.1 2975.16   431.3 2982.33   444.9 2984.63   456.7 2989.94
   466.9 2992.38   481.7 2997.27   488.2 3000.27   494.7 3005.07   498.5 3006.39
#Mann= 4, -1 ,  0
       0     0.1       0   154.8   0.045       0   180.7     0.1       0
  418.88    0.06       0
#XS Ineff= 2 , 0
                           245.9         2967.19
Permanent Ineff=
       F       F
Bank Sta=154.8,180.7
XS Rating Curve= 0 ,0
Exp/Cntr=0.3,0.1

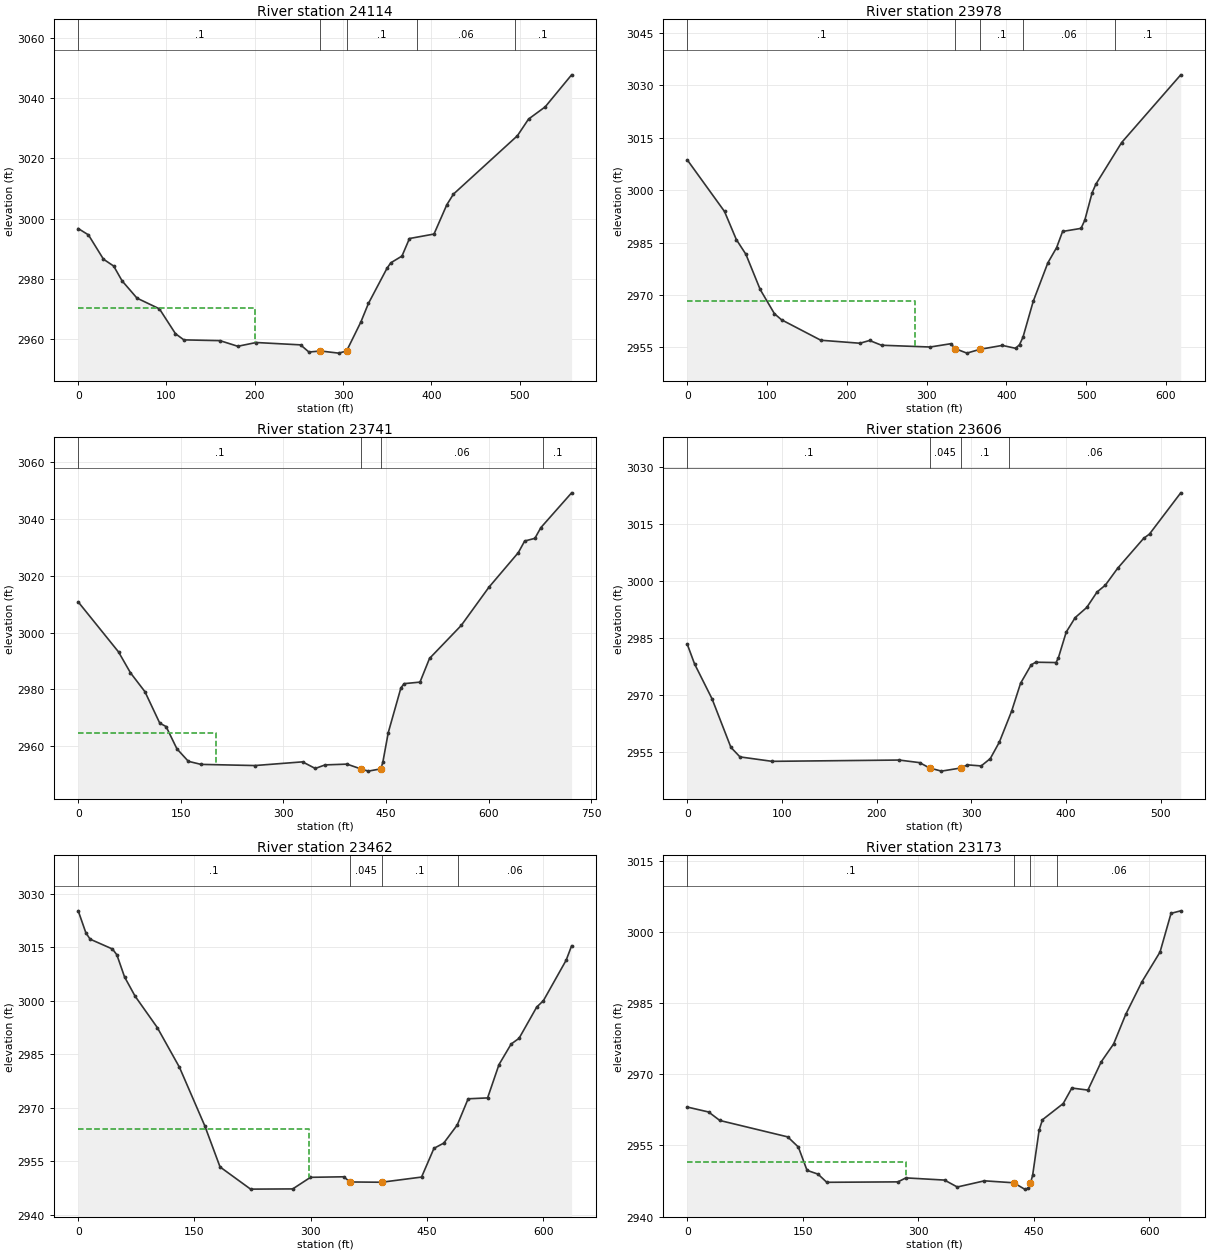
Type RM Length L Ch R = 1 ,24114   ,135.4,135.4,135.4
XS GIS Cut Line= 3
2326056.94017558642508.6867509592326287.59366016642467.337635507
2326553.61512848642359.493238345
#Sta/Elev= 30
       0 2996.69    11.6 2994.58    28.6 2986.53    40.2 2984.25    49.7 2979.35
    66.6 2973.62      92 2970.07   110.2 2961.83   119.7 2959.78   160.6 2959.53
   180.8 2957.66   201.6 2958.91   251.9 2958.13   261.4 2955.75   274.5  2956.1
     295 2955.39  304.03 2956.08   320.3 2965.75   328.8 2971.85   349.9 2983.55
   354.2 2985.34   366.8 2987.56   375.3 2993.38   403.1 2994.86   417.6 3004.56
   425.1 3008.09   497.6 3027.45   510.2 3032.97   529.1 3037.03     559 3047.64
#Mann= 5, -1 ,  0
       0     0.1       0   274.5   0.045       0  304.03     0.1       0
  384.33    0.06       0  494.33     0.1       0
#XS Ineff= 2 , 0
          200.45 2970.45
Permanent Ineff=
       F       F
Bank Sta=274.5,304.03
XS Rating Curve= 0 ,0
Exp/Cntr(USF)=0,0
Exp/Cntr=0.3,0.1

Type RM Length L Ch R = 1 ,23978   ,237.6,237.6,237.6
XS GIS Cut Line= 4
2326046.55011883642729.993440585  2326279.451836642613.329259902
2326442.83968051642547.8891587912326600.27215219642456.471638635
#Sta/Elev= 30
       0 3008.64    46.6  2993.9    61.4 2985.87    73.4 2981.65    91.3 2971.58
   109.2 2964.63   118.1  2962.9   167.3 2957.05   216.4 2956.19   228.4 2956.98
   243.4 2955.62   304.4 2955.11   330.2 2956.05     3362954.624   350.4 2953.36
   366.52954.434   394.8 2955.57   411.5 2954.74   416.4 2955.78   420.7  2957.9
   433.6 2968.21   451.9  2979.2   462.9 2983.57   470.4 2988.19   493.5 2989.07
   498.2  2991.4   507.4 2999.25     512 3001.68   544.4 3013.64   618.5 3033.02
#Mann= 5, -1 ,  0
       0     0.1       0     336   0.045       0   366.5     0.1       0
  420.49    0.06       0  536.49     0.1       0
#XS Ineff= 2 , 0
          284.91 2968.27
Permanent Ineff=
       F       F
Bank Sta=336,366.5
XS Rating Curve= 0 ,0
Exp/Cntr=0.3,0.1

Type RM Length L Ch R = 1 ,23741   ,134.5,134.5,134.5
XS GIS Cut Line= 2
 2326141.3665589642947.8725781722326763.30797739642582.765267724
#Sta/Elev= 30
       0 3010.81    58.9 2993.18    76.4  2985.8    97.5 2979.15   119.2 2968.05
   128.5 2966.83   144.3 2958.98     161 2954.58   179.5  2953.5   258.3 2953.09
   327.9 2954.39   346.5 2952.06   360.9 2953.32   392.9 2953.59   413.2  2951.9
   424.1 2951.12   442.4 2951.93   445.3 2954.29   453.2 2964.71   471.7 2980.49
   476.4 2981.98   499.6 2982.52   513.5 2990.87   559.9 3002.52   600.2 3015.95
   643.3  3028.2   652.6 3032.29   667.5 3033.23   676.2    3037   721.2 3049.29
#Mann= 4, -1 ,  0
       0     0.1       0   413.2   0.045       0   442.4    0.06       0
     680     0.1       0
#XS Ineff= 2 , 0
          200.79 2964.57
Permanent Ineff=
       F       F
Bank Sta=413.2,442.4
XS Rating Curve= 0 ,0
Exp/Cntr(USF)=0,0
Exp/Cntr=0.3,0.1

Type RM Length L Ch R = 1 ,23606   ,143.9,143.9,143.9
XS GIS Cut Line= 2
2326313.85823897643015.0027418892326747.71017049642726.092374934
#Sta/Elev= 30
       0 2983.33     7.6 2978.21    26.1 2968.99      46 2956.21    55.6 2953.69
    89.5 2952.52   223.8 2952.86   245.3 2952.18   255.9 2950.77   268.4 2949.94
  288.93 2950.77   295.9 2951.59   310.4 2951.31     320 2953.24   329.6  2957.6
   342.5 2965.72     352  2973.1   363.2 2977.95     368 2978.65   389.5 2978.56
     392 2979.86   400.2 2986.58   409.7 2990.41   421.9 2993.08   432.8 2997.16
   441.5 2998.95   454.5  3003.4   481.9 3011.27   488.2 3012.44   521.2  3023.3
#Mann= 4, -1 ,  0
       0     0.1       0   255.9   0.045       0  288.93     0.1       0
     340    0.06       0
Bank Sta=255.9,288.93
XS Rating Curve= 0 ,0
Exp/Cntr(USF)=0,0
Exp/Cntr=0.3,0.1

Type RM Length L Ch R = 1 ,23462   ,288.8,288.8,288.8
XS GIS Cut Line= 3
2326303.66620241643206.9847959652326728.39314676642901.183686299
2326817.75720566642831.566812889
#Sta/Elev= 30
       0 3025.26     9.9 3019.08    15.4 3017.31    44.2 3014.55    49.9 3012.91
    59.8 3006.72    73.3 3001.36     102 2992.54   130.6  2981.4   163.3 2964.98
     183 2953.44   222.4 2947.22   276.8 2947.28   299.7 2950.53   342.7 2950.68
   350.6 2949.23   391.4 2949.15     443  2950.6     459 2958.66   471.6 2960.12
   489.1 2965.22   503.1 2972.55   528.2  2972.8   542.9 2982.14   558.6 2987.91
   568.8 2989.51   591.6 2998.28   600.2 3000.06   629.6 3011.43   636.6 3015.45
#Mann= 4, -1 ,  0
       0     0.1       0   350.6   0.045       0   391.4     0.1       0
     490    0.06       0
#XS Ineff= 2 , 0
          297.57 2963.99
Permanent Ineff=
       T       F
Bank Sta=350.6,391.4
XS Rating Curve= 0 ,0
Exp/Cntr=0.3,0.1

Type RM Length L Ch R = 1 ,23173   ,211.4,211.4,211.4
XS GIS Cut Line= 2
2326447.38612577 643363.141178372326945.94645314642960.264146151
#Sta/Elev= 30
       0 2963.09    27.6 2962.05    42.2 2960.26   130.4  2956.8   144.2 2954.66
   155.5 2949.74   169.8 2948.94   181.1 2947.22   273.6 2947.31   283.9 2948.15
   334.1 2947.69   350.7 2946.23   385.9 2947.53     4242947.117   438.1 2945.78
   442.8 2945.92   445.7    2947   448.6 2948.72     457 2958.19   461.3 2960.41
   488.3 2963.83   499.5  2967.1   520.4 2966.67   537.7 2972.64   553.8  2976.4
   569.5 2982.63   590.7 2989.55   614.1 2995.79   628.4 3003.95     641 3004.48
#Mann= 4, -1 ,  0
       0     0.1       0     424   0.045       0   445.7     0.1       0
     480    0.06       0
#XS Ineff= 2 , 0
          283.92 2951.54
Permanent Ineff=
       T       F
Bank Sta=424,445.7
XS Rating Curve= 0 ,0
Exp/Cntr(USF)=0,0
Exp/Cntr=0.3,0.1