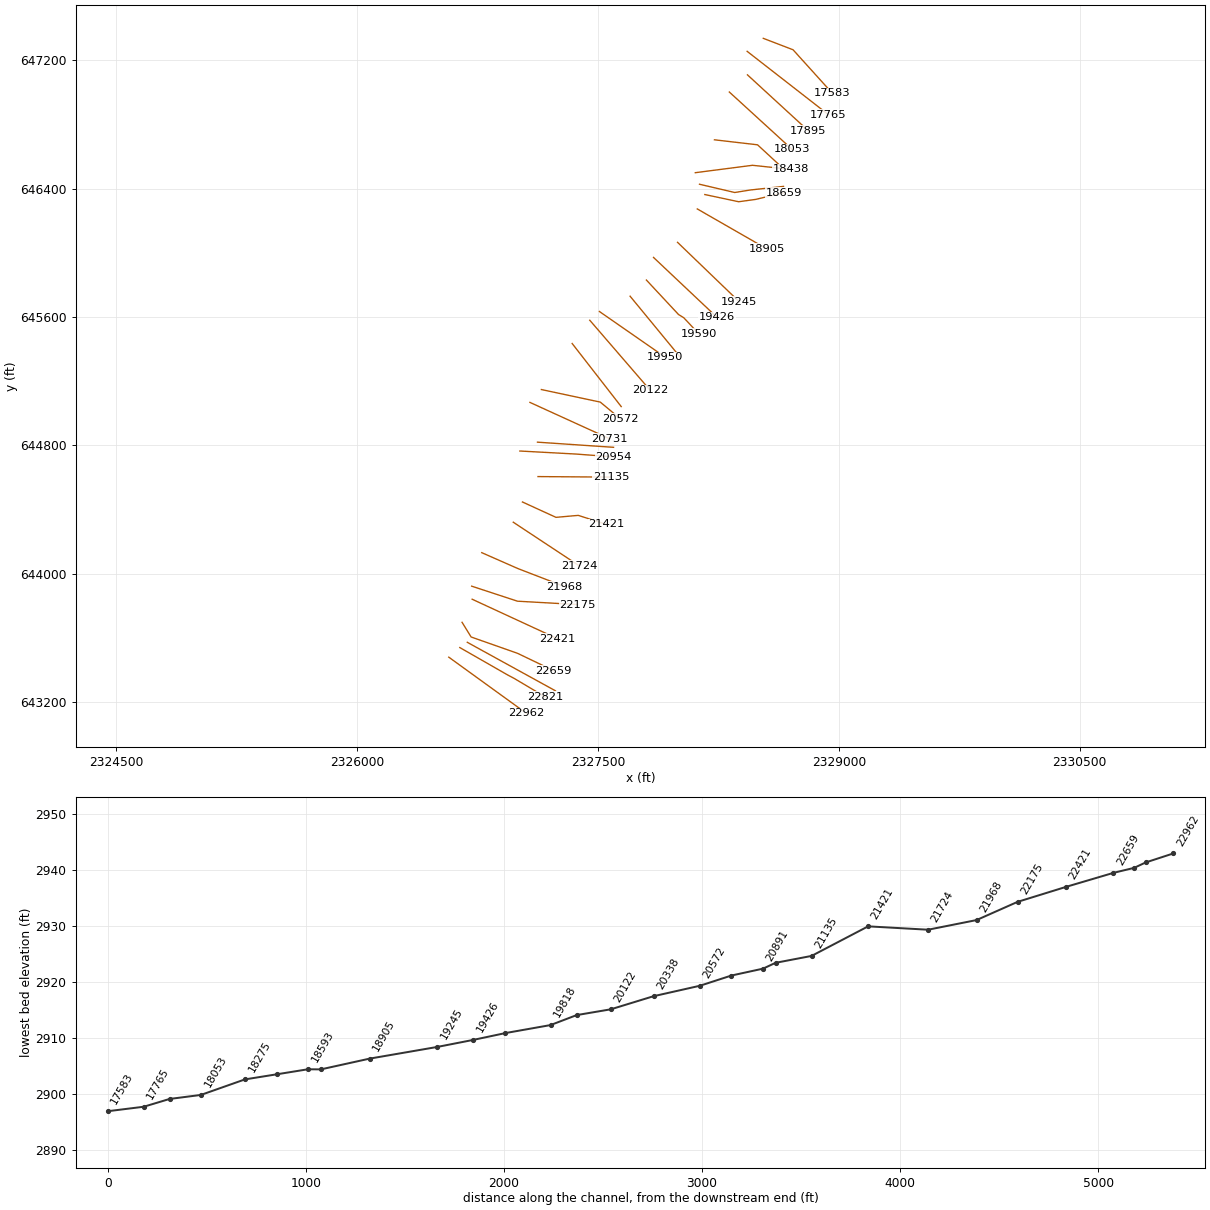
HEC-RAS study WFKGLADYFK.prj: WFKGLADYFK

--- WFKGLADYFK.g01 (geometry) --- (continued)

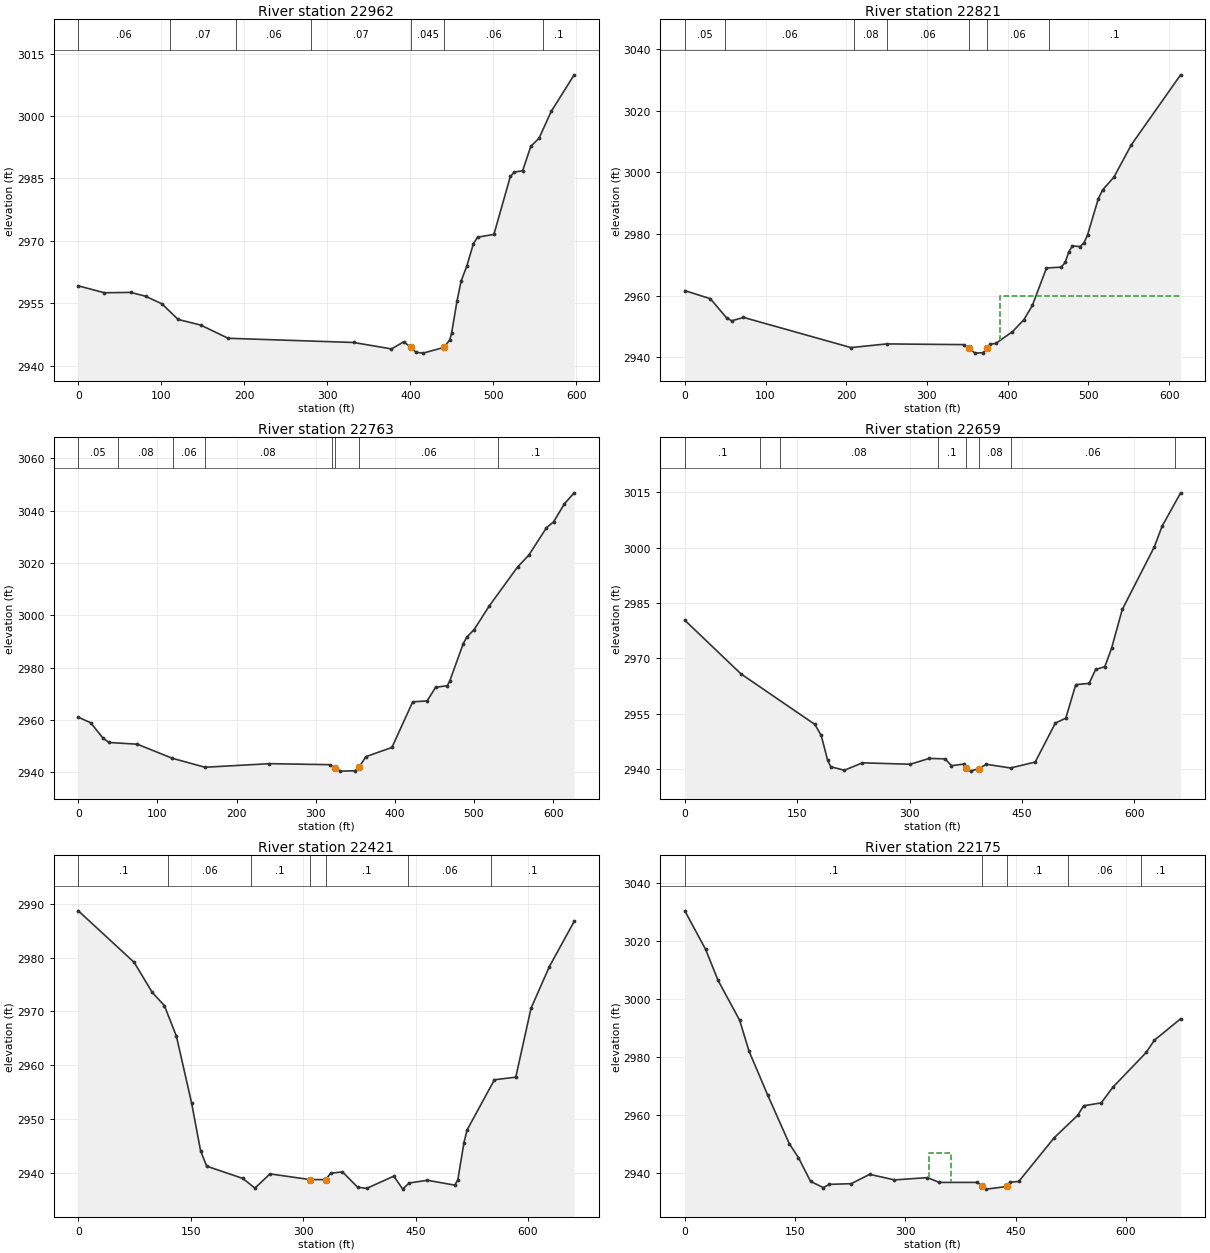
Type RM Length L Ch R = 1 ,22962   ,140.6,140.6,140.6
XS GIS Cut Line= 2
2326570.59768825643479.6758354432327054.50263585643129.346099794
#Sta/Elev= 30
       0 2959.16    31.5  2957.5    63.1 2957.59      81 2956.67   100.7 2954.84
   120.2 2951.09   147.5 2949.73   180.5 2946.56   331.7 2945.55   377.3    2944
   392.1 2945.72   400.8 2944.36   406.8 2943.19   415.4 2942.99   440.8 2944.38
   447.6 2946.22   449.8 2947.86   456.3 2955.57   461.2 2960.32   468.1 2963.95
     476 2969.29     481 2970.86   500.7 2971.53   520.5 2985.45   525.4 2986.52
   535.3 2986.83   545.2 2992.72     555 2994.63   569.8 3001.11   597.4 3009.89
#Mann= 7, -1 ,  0
       0    0.06       0     110    0.07       0     190    0.06       0
     280    0.07       0   400.8   0.045       0   440.8    0.06       0
     560     0.1       0
Bank Sta=400.8,440.8
XS Rating Curve= 0 ,0
Exp/Cntr=0.3,0.1

Type RM Length L Ch R = 1 ,22821   ,57.8,57.8,57.8
XS GIS Cut Line= 4
2326639.30461838643539.5833406532326939.56893727 643367.50203509
2326979.03360084 643346.68414854 2327171.1700418643232.327859976
#Sta/Elev= 30
       0 2961.65    31.7 2959.02    51.7 2952.83    58.1 2951.85    72.7 2952.96
   205.9 2943.17     250 2944.36   345.3 2944.13   351.5 2943.01   359.6 2941.37
   369.4 2941.53   374.9 2942.93   378.4 2944.26   385.4 2944.52     406 2948.34
     420 2952.17   430.6 2956.84   448.1 2968.99   466.5 2969.27   471.2 2970.78
   475.8 2974.23   480.2 2976.16   489.8 2975.94   494.8 2977.26   499.1 2979.83
   512.3 2991.46   517.7 2994.34   531.7 2998.48   553.1 3008.91   614.3 3031.66
#Mann= 7, -1 ,  0
       0    0.05       0      50    0.06       0     210    0.08       0
     250    0.06       0   351.5   0.045       0   374.9    0.06       0
   450.7     0.1       0
#XS Ineff= 2 , 0
                             390            2960
Permanent Ineff=
       F       F
Bank Sta=351.5,374.9
XS Rating Curve= 0 ,0
Exp/Cntr(USF)=0,0
Exp/Cntr=0.3,0.1

Type RM Length L Ch R = 1 ,22763   ,104.3,104.3,104.3
XS GIS Cut Line= 2
2326686.00101319643572.2646593832327234.92096959643270.106885219
#Sta/Elev= 30
       0 2961.03    15.7 2958.88    31.3 2952.97      39 2951.36    74.6  2950.7
   118.7 2945.33     160 2941.89   241.5 2943.26   317.5 2942.88   324.9 2941.59
   331.2 2940.41   349.5 2940.54   354.8 2941.89   363.3 2945.93   396.3 2949.47
   422.6 2966.91   440.8 2967.23   451.5 2972.46   466.2 2973.06   469.2 2974.72
   486.5 2989.19     491 2991.66   500.2 2994.53   519.2 3003.51     555 3018.41
   569.3 3022.97   591.5 3033.41   600.6 3035.71   614.3  3042.6   626.6 3046.79
#Mann= 8, -1 ,  0
       0    0.05       0      50    0.08       0     120    0.06       0
     160    0.08       0     320    0.06       0   324.9   0.045       0
   354.8    0.06       0     530     0.1       0
Bank Sta=324.9,354.8
XS Rating Curve= 0 ,0
Exp/Cntr(USF)=0,0
Exp/Cntr=0.3,0.1

Type RM Length L Ch R = 1 ,22659   ,238.2,238.2,238.2
XS GIS Cut Line= 4
 2326653.3522392643696.9090288762326709.77244554643605.469384116
2326999.65557467643503.329355395 2327222.4181135643396.325515782
#Sta/Elev= 30
       0 2980.36    74.9 2965.85   173.6 2952.17   182.1 2949.19   190.6 2942.52
   194.8  2940.7     213 2939.76   237.2 2941.77   300.9 2941.38   326.3 2942.96
   347.5 2942.84     356 2940.99   372.9 2941.44  375.52 2940.26   381.4 2939.52
   392.5 2940.21   402.6 2941.37   434.8 2940.37   467.8 2941.98   494.7 2952.54
   508.6 2953.84   521.9 2962.93   539.7 2963.26   548.5 2967.03   560.7 2967.78
   569.7 2972.76     584 2983.27   626.6 3000.13   637.2 3005.81   661.9 3014.83
#Mann= 8, -1 ,  0
       0     0.1       0     100    0.05       0  127.45    0.08       0
  337.45     0.1       0  375.52   0.045       0   392.5    0.08       0
   434.8    0.06       0   654.8     0.1       0
Bank Sta=375.52,392.5
XS Rating Curve= 0 ,0
Exp/Cntr(USF)=0,0
Exp/Cntr=0.3,0.1

Type RM Length L Ch R = 1 ,22421   ,245.9,245.9,245.9
XS GIS Cut Line= 2
2326716.24858564643840.6460075122327247.63338668643594.809186954
#Sta/Elev= 30
       0 2988.66    74.5  2979.1    98.7 2973.51   114.8 2971.08   130.9 2965.38
     151 2953.07   163.1 2944.15   171.2 2941.29   219.5 2939.01   235.6 2937.22
   255.7 2939.86   308.6 2938.81  330.03 2938.79   336.5 2939.97   352.4 2940.23
   372.5  2937.4   384.6 2937.16   420.9 2939.44   432.8 2937.03   441.3 2938.17
   465.7 2938.67   502.3 2937.77   506.3 2938.76   514.5 2945.68   518.7 2948.02
   555.1 2957.32   583.6  2957.8   603.9 2970.56   628.3 2978.28   661.5 2986.69
#Mann= 7, -1 ,  0
       0     0.1       0     120    0.06       0     230     0.1       0
   308.6   0.045       0  330.03     0.1       0     440    0.06       0
     550     0.1       0
Bank Sta=308.6,330.03
XS Rating Curve= 0 ,0
Exp/Cntr=0.3,0.1

Type RM Length L Ch R = 1 ,22175   ,207.1,207.1,207.1
XS GIS Cut Line= 3
2326713.26228309643922.069411998 2326998.7361136643828.398311363
2327371.93367327643807.582511222
#Sta/Elev= 30
       0 3030.46    28.3 3017.14    45.2 3006.46    74.6 2992.66    87.3 2982.02
   112.5 2966.96     142 2950.08   154.6  2945.2     171 2937.01   188.3 2934.88
   196.7 2935.99   226.2 2936.22   251.4 2939.45   285.1 2937.53   329.9 2938.31
     346 2936.66     398 2936.66   404.6 2935.32   410.1 2934.34   438.1 2935.25
   442.1 2936.72   454.1 2936.98   502.2 2952.07   534.3 2959.85   542.3 2963.14
   566.3 2964.13   582.3 2969.61   627.4 2981.54   638.4 2985.75   674.2 2993.18
#Mann= 5, -1 ,  0
       0     0.1       0   404.6   0.045       0   438.1     0.1       0
  520.45    0.06       0  620.45     0.1       0
#XS Ineff= 1 ,-1
  331.49  362.25 2946.79
Permanent Ineff=
       F
Bank Sta=404.6,438.1
XS Rating Curve= 0 ,0
Exp/Cntr(USF)=0,0
Exp/Cntr=0.3,0.1

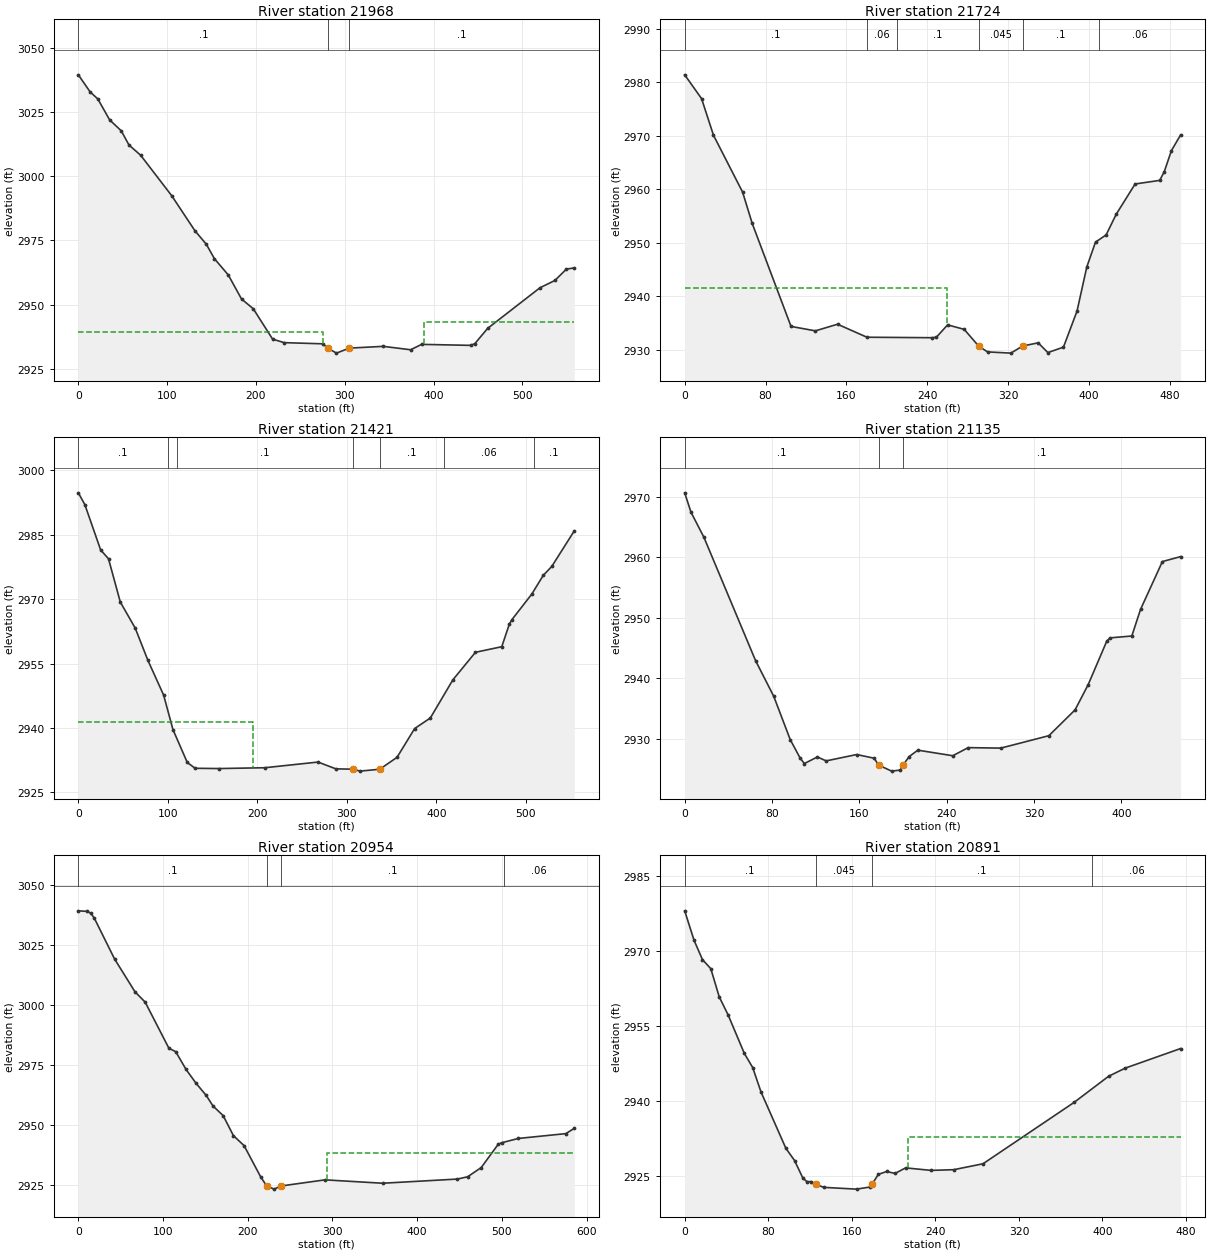
Type RM Length L Ch R = 1 ,21968   ,244.3,244.3,244.3
XS GIS Cut Line= 3
2326776.00255483644130.8872613062327000.30437097644032.141962903
2327292.53013309643919.267165312
#Sta/Elev= 30
       0 3039.47    13.3 3032.81      22 3030.05    35.2 3021.94    48.3 3017.67
      57 3012.14    70.1 3008.17   105.1  2992.4   131.3 2978.73   144.1 2973.48
   153.2 2967.87   168.8 2961.53   183.7 2952.17   196.9 2948.38   218.7 2936.54
   231.8 2935.17     275 2934.72   281.3 2932.95   290.6 2931.09     305 2933.04
   343.2 2933.73   374.1  2932.4   386.4  2934.5     442 2934.11   446.5 2934.83
   460.7 2940.71   519.7 2956.55   536.5 2959.39   549.4  2963.8   558.3 2964.28
#Mann= 3, -1 ,  0
       0     0.1       0   281.3   0.045       0     305     0.1       0
#XS Ineff= 2 , 0
          274.89 2939.39  389.37         2943.07
Permanent Ineff=
       F       F
Bank Sta=281.3,305
XS Rating Curve= 0 ,0
Exp/Cntr=0.3,0.1

Type RM Length L Ch R = 1 ,21724   ,302.8,302.8,302.8
XS GIS Cut Line= 2
2326972.40543048644320.5751276982327381.72660905644050.043522925
#Sta/Elev= 30
       0 2981.36    16.7 2976.92    28.5 2970.07    57.3 2959.45    66.8  2953.6
   105.2 2934.36   129.3 2933.53   151.2 2934.77   180.3 2932.34   244.8 2932.25
     249 2932.34   260.1 2934.65   276.5 2933.81     291 2930.65   299.6  2929.6
   322.7 2929.37   334.3  2930.7   349.7 2931.29   359.3 2929.47   374.7 2930.49
   388.1 2937.21   397.8 2945.47   406.4 2950.11   416.9 2951.45   426.9 2955.32
   445.6 2960.97   469.9 2961.64   474.4 2963.25   481.5  2967.2   490.6 2970.14
#Mann= 6, -1 ,  0
       0     0.1       0     180    0.06       0     210     0.1       0
     291   0.045       0   334.3     0.1       0     410    0.06       0
#XS Ineff= 2 , 0
          259.75 2941.55
Permanent Ineff=
       T       F
Bank Sta=291,334.3
XS Rating Curve= 0 ,0
Exp/Cntr(USF)=0,0
Exp/Cntr=0.3,0.1

Type RM Length L Ch R = 1 ,21421   ,285.6,285.6,285.6
XS GIS Cut Line= 4
2327029.53394121 644446.658879642327238.50932816644350.974544643
2327377.08729985 644363.25112101  2327553.289426644306.603259684
#Sta/Elev= 30
       0 2994.77     7.3 2992.01    24.9 2981.48    33.7 2979.41    46.9 2969.33
    63.5 2963.29    77.7 2955.77    95.3 2947.66   105.7 2939.64   121.7 2931.98
   130.5 2930.63   157.3 2930.57   208.3 2930.76   267.7 2932.08   287.7  2930.5
   307.2 2930.42   314.6 2929.97   336.7 2930.41     356 2933.18   375.7 2939.89
   393.2 2942.34   418.4 2951.23   443.6 2957.64     473 2958.94   481.4 2964.16
   484.3 2965.23   506.6 2971.21   519.3 2975.54   528.9 2977.64     554 2985.91
#Mann= 7, -1 ,  0
       0     0.1       0     100    0.06       0     110     0.1       0
   307.2   0.045       0   336.7     0.1       0  408.96    0.06       0
  508.96     0.1       0
#XS Ineff= 2 , 0
          195.36 2941.51
Permanent Ineff=
       F       F
Bank Sta=307.2,336.7
XS Rating Curve= 0 ,0
Exp/Cntr=0.3,0.1

Type RM Length L Ch R = 1 ,21135   ,181.8,181.8,181.8
XS GIS Cut Line= 2
2327126.58408558644604.9908465712327580.89718389644601.686751311
#Sta/Elev= 30
       0 2970.64     5.8 2967.43    17.6 2963.31    64.9 2942.95    81.6 2937.04
    96.7 2929.89   105.6  2926.9   109.6 2925.94   121.6 2927.03   129.6 2926.38
   157.6 2927.43   173.6 2926.82   177.6 2925.69   189.6 2924.69   197.6 2924.87
     200 2925.68   205.6 2927.09   213.6 2928.15   245.6 2927.23   259.7 2928.57
   289.6 2928.49   333.6 2930.54   357.6  2934.8   369.6 2938.96   386.6 2946.13
   389.6 2946.69   409.6    2947   417.6  2951.4   437.6 2959.29   454.3 2960.11
#Mann= 3, -1 ,  0
       0     0.1       0   177.6   0.045       0     200     0.1       0
Bank Sta=177.6,200
XS Rating Curve= 0 ,0
Exp/Cntr(USF)=0,0
Exp/Cntr=0.3,0.1

Type RM Length L Ch R = 1 ,20954   ,63.1,63.1,63.1
XS GIS Cut Line= 3
2327013.38887438644764.299589375 2327355.2810439644745.863485664
2327597.76859858644728.135028673
#Sta/Elev= 30
       0 3039.22    10.8 3038.98    14.8 3038.19    18.8 3036.21    42.8 3019.17
    66.9 3005.54    78.9 3001.24   106.9 2982.07     115 2980.62   127.2 2973.23
     139 2967.48     151 2962.42     159 2958.04     171 2954.02   183.1 2945.71
   195.7 2941.54   215.1 2928.67   222.3 2924.79   231.1 2923.46   239.1 2924.76
   291.2 2927.32   359.3 2925.91   447.6 2927.65   459.6  2928.6   475.6 2932.42
   495.7 2942.11   499.7 2942.75   519.5 2944.54   575.6 2946.55   585.5 2948.76
#Mann= 4, -1 ,  0
       0     0.1       0   222.3   0.045       0   239.1     0.1       0
  502.39    0.06       0
#XS Ineff= 2 , 0
                          293.05         2938.54
Permanent Ineff=
       F       F
Bank Sta=222.3,239.1
XS Rating Curve= 0 ,0
Exp/Cntr=0.3,0.1

Type RM Length L Ch R = 1 ,20891   ,159.7,159.7,159.7
XS GIS Cut Line= 2
2327123.19637131644819.4765826322327596.93155215644787.375430748
#Sta/Elev= 30
       0 2977.96       9 2972.07      17 2968.23      25 2966.42    33.1 2960.78
    41.6 2957.18    57.1 2949.51    65.1 2946.69    73.1  2941.8    96.9 2930.56
   105.2 2928.13   113.2  2924.6   117.2  2923.9   121.3 2923.92   125.3 2923.38
   133.3 2922.77   164.5 2922.42   177.4 2922.84   179.2 2923.35   185.4 2925.36
   193.4 2925.94   201.4 2925.55   211.5 2926.66   235.9 2926.16   257.6  2926.3
   285.6 2927.48   372.7 2939.71   405.9 2944.95   421.9 2946.58   474.8 2950.48
#Mann= 4, -1 ,  0
       0     0.1       0   125.3   0.045       0   179.2     0.1       0
     390    0.06       0
#XS Ineff= 2 , 0
                          213.68         2932.89
Permanent Ineff=
       F       F
Bank Sta=125.3,179.2
XS Rating Curve= 0 ,0
Exp/Cntr(USF)=0,0
Exp/Cntr=0.3,0.1

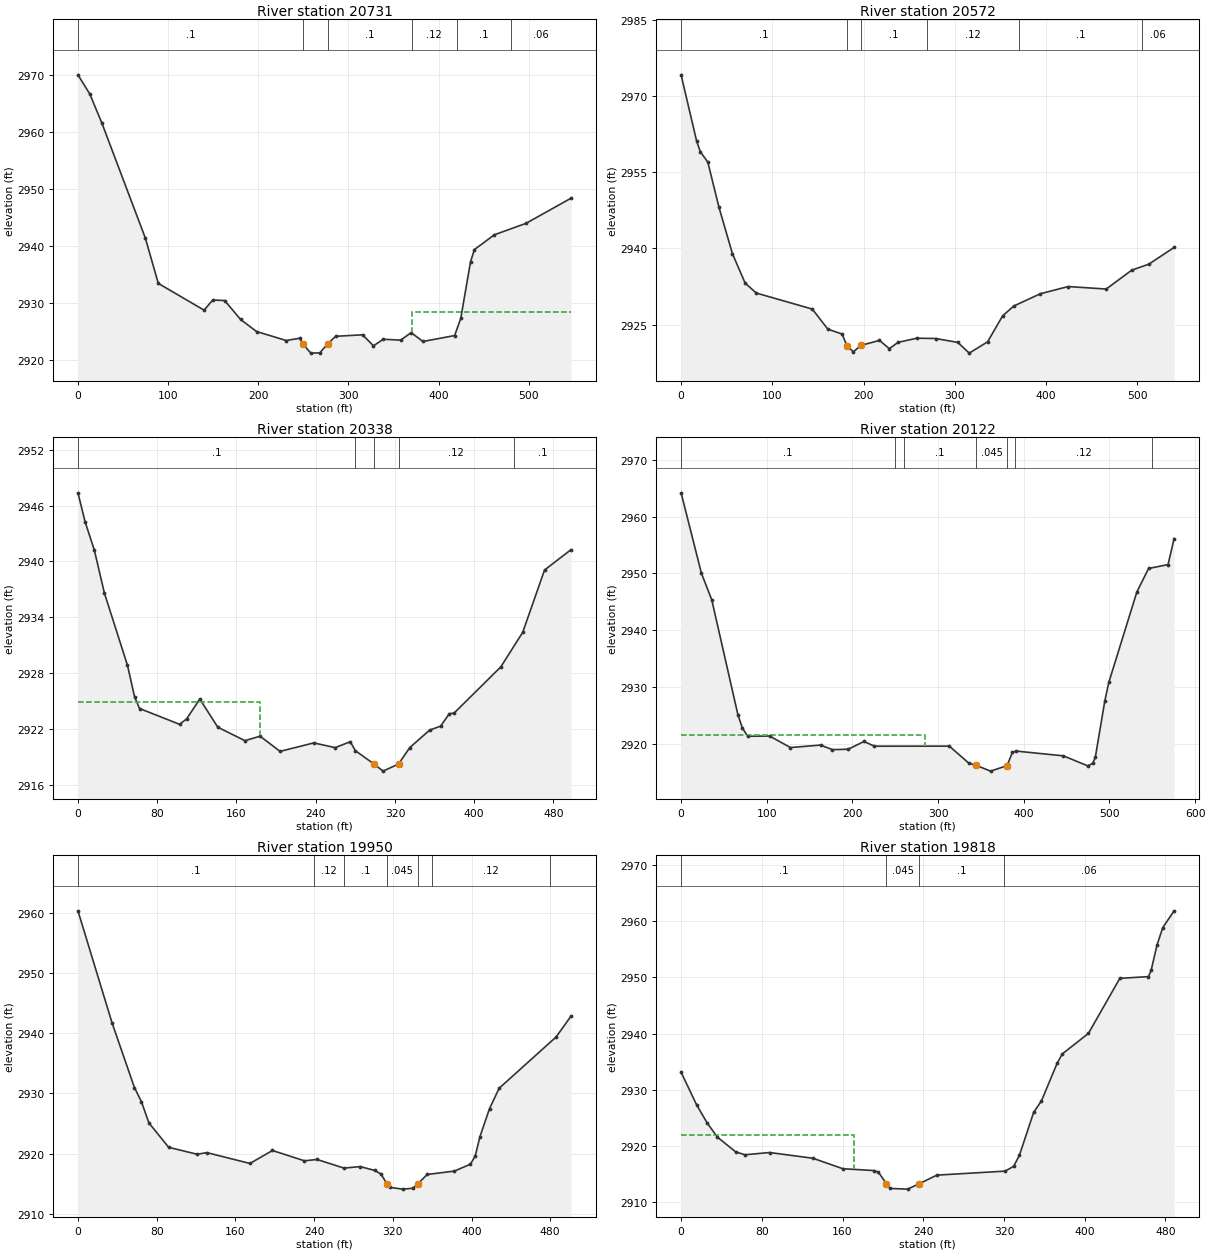
Type RM Length L Ch R = 1 ,20731   ,158.5,158.5,158.5
XS GIS Cut Line= 2
 2327076.1335139 645067.246662472327573.51256602644840.317469939
#Sta/Elev= 30
       0 2969.97    13.2 2966.59    26.4 2961.57    74.8 2941.33    89.1 2933.41
   139.9 2928.72   149.5  2930.5   162.7 2930.41   180.3  2927.1     198 2924.98
     231  2923.4   245.9  2923.8   249.62922.771   258.2 2921.19   268.2 2921.24
     277 2922.82   285.8 2924.14   315.6  2924.4   327.7 2922.47   338.6 2923.62
   357.9 2923.47   369.4 2924.78   382.6 2923.23   417.7 2924.27   424.5 2927.28
   435.3 2937.18   439.7 2939.35   461.7 2941.93   496.9 2943.94   546.7 2948.34
#Mann= 6, -1 ,  0
       0     0.1       0   249.6   0.045       0     277     0.1       0
     370    0.12       0     420     0.1       0     480    0.06       0
#XS Ineff= 2 , 0
                          370.04         2928.48
Permanent Ineff=
       F       F
Bank Sta=249.6,277
XS Rating Curve= 0 ,0
Exp/Cntr(USF)=0,0
Exp/Cntr=0.3,0.1

Type RM Length L Ch R = 1 ,20572   ,234.5,234.5,234.5
XS GIS Cut Line= 3
 2327147.5638875645147.3472123522327514.27015697645069.137992675
2327641.44932843 644963.41525378
#Sta/Elev= 30
       0 2974.21      17 2961.18    21.1 2959.06    29.3    2957    41.5 2948.12
    56.3 2938.95    70.2 2933.17    82.4 2931.21   143.8 2928.05   160.8  2924.1
   176.5 2923.13  181.61 2920.87   188.8 2919.61   196.9 2920.88   217.4 2921.88
   228.2 2920.25   237.8 2921.49   258.3 2922.31   278.9 2922.25   303.3 2921.48
   315.8 2919.37   335.9  2921.6   352.4 2926.72   364.6 2928.65   393.7 2931.07
   424.2 2932.49   465.9    2932   493.8 2935.71   512.7 2936.91   540.3  2940.2
#Mann= 6, -1 ,  0
       0     0.1       0  181.61   0.045       0   196.9     0.1       0
     270    0.12       0     370     0.1       0  504.95    0.06       0
Bank Sta=181.61,196.9
XS Rating Curve= 0 ,0
Exp/Cntr=0.3,0.1

Type RM Length L Ch R = 1 ,20338   ,216,216,216
XS GIS Cut Line= 2
 2327339.1495749645434.2622793172327644.59689888645041.266359284
#Sta/Elev= 30
       0 2947.37     7.2 2944.27    16.6  2941.2    26.7 2936.61      50 2928.86
    57.1  2925.5    62.2 2924.22   102.7 2922.52   109.8 2923.12     123 2925.24
   141.2 2922.21   168.6 2920.77   183.9 2921.25     204 2919.62   238.1 2920.53
   259.7 2920.02   274.9 2920.66     280  2919.7  298.78 2918.27     308  2917.5
   323.6 2918.26     335 2920.03     355  2921.9   366.1 2922.33   374.9 2923.66
   379.7 2923.73   426.9 2928.69     449  2932.4     471 2939.08   497.7 2941.27
#Mann= 5, -1 ,  0
       0     0.1       0     280    0.12       0  298.78   0.045       0
   323.6    0.12       0     440     0.1       0
#XS Ineff= 2 , 0
             184 2924.89
Permanent Ineff=
       F       F
Bank Sta=298.78,323.6
XS Rating Curve= 0 ,0
Exp/Cntr(USF)=0,0
Exp/Cntr=0.3,0.1

Type RM Length L Ch R = 1 ,20122   ,172,172,172
XS GIS Cut Line= 2
2327448.77605362645579.3630979272327824.59286356645143.465565247
#Sta/Elev= 30
       0 2964.17    23.8 2949.98    35.8 2945.33    66.3 2925.11    71.5 2922.78
    77.7  2921.3   103.3 2921.34   127.7 2919.31   162.8 2919.75   176.7 2918.94
   195.1 2919.02   213.5 2920.38   225.7 2919.55   313.1 2919.56   335.6  2916.6
   344.3 2916.18   361.3 2915.16  380.51 2916.13   386.8 2918.48   391.1 2918.69
   446.3 2917.85   474.8 2916.08   480.4 2916.52   483.5 2917.56   494.6 2927.51
   499.3  2930.8     532  2946.7   545.7 2950.85   568.4 2951.53   575.5 2956.11
#Mann= 7, -1 ,  0
       0     0.1       0     250    0.12       0     260     0.1       0
   344.3   0.045       0  380.51     0.1       0     390    0.12       0
     550    0.06       0
#XS Ineff= 2 , 0
          284.91  2921.6
Permanent Ineff=
       F       F
Bank Sta=344.3,380.51
XS Rating Curve= 0 ,0
Exp/Cntr(USF)=0,0
Exp/Cntr=0.3,0.1

Type RM Length L Ch R = 1 ,19950   ,131.7,131.7,131.7
XS GIS Cut Line= 2
2327508.58529173645633.9534015312327920.15906977645348.061359141
#Sta/Elev= 30
       0 2960.31    34.7  2941.7    57.4 2930.99    64.5 2928.65    72.1 2925.13
    92.2 2921.07   121.3 2919.91     131 2920.19   174.8 2918.39   197.7 2920.54
   230.2 2918.83     243 2919.05   270.4 2917.62   286.9 2917.87   301.5 2917.24
   307.8 2916.66   314.3 2914.98   316.9 2914.42   330.2 2914.13   340.4 2914.27
   345.3 2914.99     355 2916.56   382.5 2917.12   398.9 2918.26   403.7 2919.58
   408.6 2922.84   418.3 2927.48   428.1 2930.87     486 2939.38   501.1 2942.83
#Mann= 7, -1 ,  0
       0     0.1       0     240    0.12       0     270     0.1       0
   314.3   0.045       0   345.3     0.1       0     360    0.12       0
     480    0.06       0
Bank Sta=314.3,345.3
XS Rating Curve= 0 ,0
Exp/Cntr=0.3,0.1

Type RM Length L Ch R = 1 ,19818   ,227.8,227.8,227.8
XS GIS Cut Line= 2
2327700.04434305645729.0092193412328010.35547792645351.577494162
#Sta/Elev= 30
       0 2933.15    15.3 2927.38    25.7 2924.16      36  2921.6      54 2918.99
    63.2 2918.46    87.8 2918.86   130.7 2917.84   160.3 2915.98   191.4 2915.65
   195.5 2915.37  203.53 2913.31   207.4 2912.47   224.5 2912.35   235.8 2913.29
   253.5 2914.84   321.1 2915.55   329.6 2916.41   335.3 2918.37   349.5 2926.05
   357.1 2928.03   372.6 2934.71   377.8  2936.4   403.7 2940.05   434.8 2949.84
   463.2 2950.15   465.8 2951.24   471.7 2955.79   477.4 2958.88   488.6 2961.85
#Mann= 4, -1 ,  0
       0     0.1       0  203.53   0.045       0   235.8     0.1       0
     320    0.06       0
#XS Ineff= 2 , 0
          171.57 2921.98
Permanent Ineff=
       F       F
Bank Sta=203.53,235.8
XS Rating Curve= 0 ,0
Exp/Cntr(USF)=0,0
Exp/Cntr=0.3,0.1

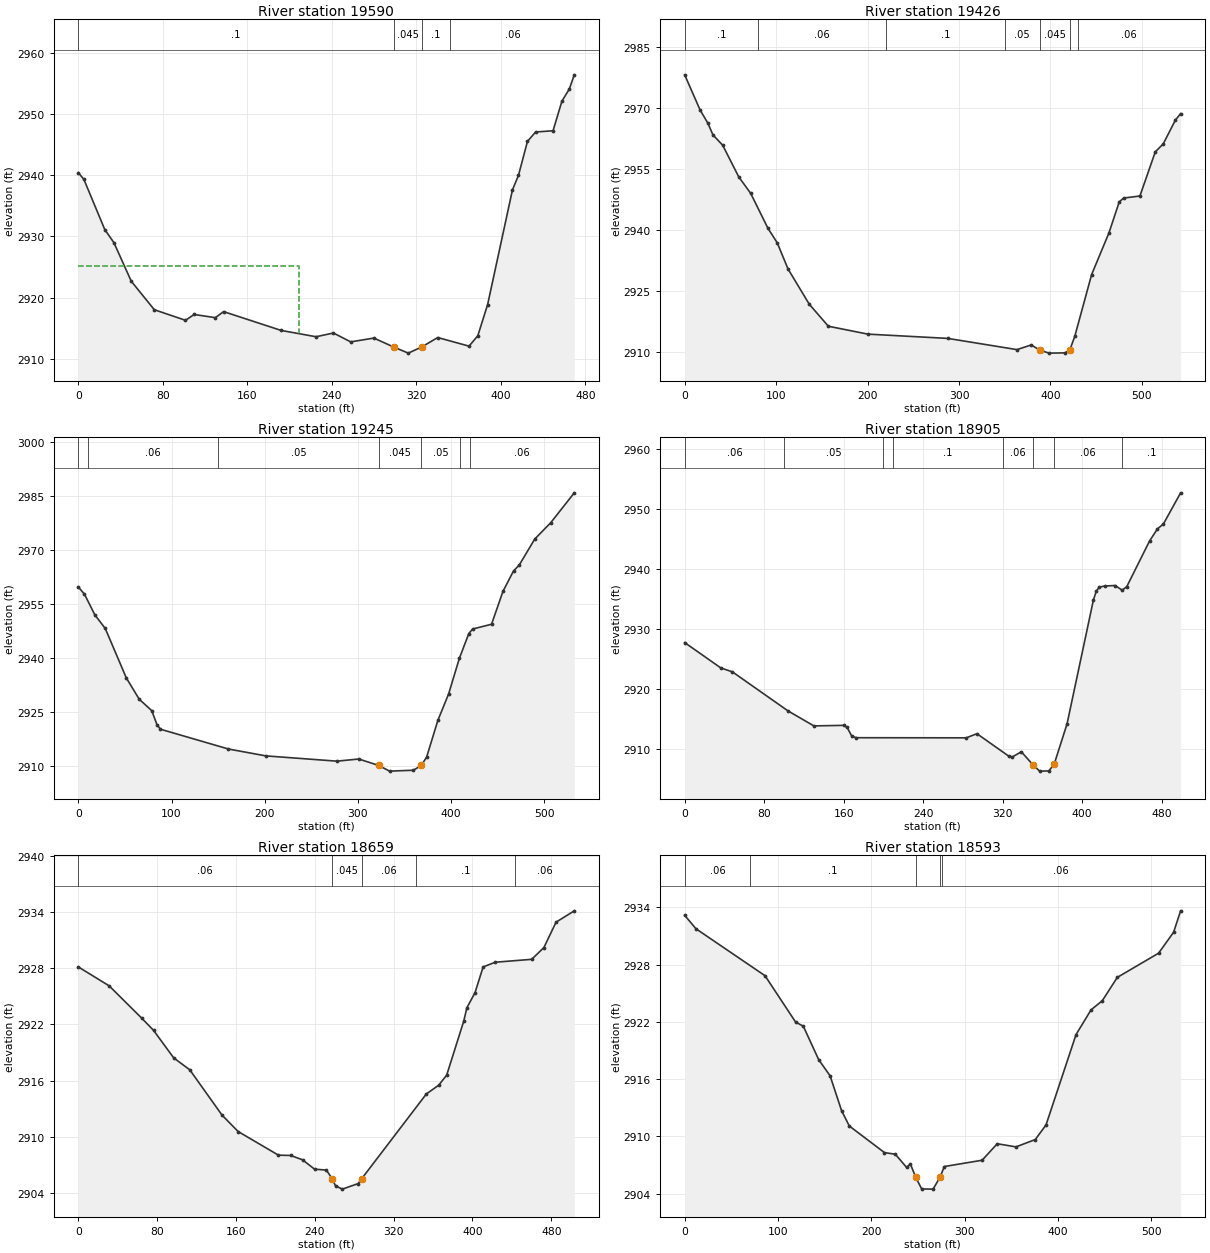
Type RM Length L Ch R = 1 ,19590   ,164.1,164.1,164.1
XS GIS Cut Line= 4
2327801.50097767645829.8059622252328001.50534736645615.100243987
2328034.46934555645594.7711226142328128.14585162645494.444639357
#Sta/Elev= 30
       0 2940.42     5.2 2939.36      25 2931.14    33.7 2928.98    50.1 2922.68
    71.9 2918.02   101.4 2916.29   109.6 2917.24   129.7 2916.72   137.5 2917.71
     192 2914.63     225  2913.6   241.4 2914.21   257.8 2912.76   279.7 2913.38
  298.35 2911.93   312.3 2910.92   324.8 2911.91   340.2 2913.47   369.8 2912.06
   378.1 2913.77   387.4 2918.87   410.9 2937.63   416.6    2940   425.1 2945.56
   432.8 2947.09   449.3 2947.29   457.7 2952.13   464.7 2954.12   469.4 2956.44
#Mann= 4, -1 ,  0
       0     0.1       0  298.35   0.045       0   324.8     0.1       0
  352.16    0.06       0
#XS Ineff= 2 , 0
          208.88  2925.2
Permanent Ineff=
       F       F
Bank Sta=298.35,324.8
XS Rating Curve= 0 ,0
Exp/Cntr(USF)=0,0
Exp/Cntr=0.3,0.1

Type RM Length L Ch R = 1 ,19426   ,180.8,180.8,180.8
XS GIS Cut Line= 2
2327845.93803274  645970.66413422328240.28826515645598.396751219
#Sta/Elev= 30
       0 2978.09    16.8 2969.48    25.3 2966.23    30.9 2963.34    41.6 2960.77
    59.2 2952.98    72.1 2948.99    91.1 2940.35   101.2 2936.81     113 2930.38
   136.2 2921.72   157.1  2916.3   200.3 2914.36   287.7 2913.31   363.4 2910.55
     379 2911.71   388.1 2910.45   398.4 2909.69   415.8 2909.75   421.1 2910.43
   426.6 2913.84     445 2929.01   463.9 2939.22   475.2 2946.87     480  2947.8
   497.8 2948.31   514.6 2959.16   523.3 2961.12   536.6 2966.97   542.3 2968.56
#Mann= 7, -1 ,  0
       0     0.1       0      80    0.06       0     220     0.1       0
     350    0.05       0   388.1   0.045       0   421.1    0.05       0
     430    0.06       0
Bank Sta=388.1,421.1
XS Rating Curve= 0 ,0
Exp/Cntr=0.3,0.1

Type RM Length L Ch R = 1 ,19245   ,340.5,340.5,340.5
XS GIS Cut Line= 2
2327995.39428261646064.9312034822328378.68701465645695.627257281
#Sta/Elev= 30
       0 2959.65     6.6 2957.65    17.7 2951.91    28.9 2948.11    51.5 2934.36
    65.4 2928.42    78.8 2925.26    84.4 2921.37    88.1  2920.1   161.1 2914.59
   201.2 2912.68   277.6 2911.21     301 2911.81   322.5 2910.01     334 2908.44
   359.6 2908.69   368.1 2910.01   373.8 2912.32   385.9 2922.57   397.4 2929.89
     409 2939.83   419.1  2946.7   423.2 2947.96   443.5 2949.29   455.8 2958.46
   467.1 2964.12   473.2 2965.75   489.9 2972.99     507 2977.52   532.3 2985.84
#Mann= 7, -1 ,  0
       0     0.1       0      10    0.06       0     150    0.05       0
   322.5   0.045       0   368.1    0.05       0     410     0.1       0
     420    0.06       0
Bank Sta=322.5,368.1
XS Rating Curve= 0 ,0
Exp/Cntr(USF)=0,0
Exp/Cntr=0.3,0.1

Type RM Length L Ch R = 1 ,18905   ,246.2,246.2,246.2
XS GIS Cut Line= 2
2328118.44049606646272.9919706412328551.15110592646024.362567453
#Sta/Elev= 30
       0 2927.79    36.3 2923.57    48.1  2922.9     104  2916.4     130  2913.9
   160.2 2913.99   163.5 2913.64   168.2 2912.18   172.7 2911.93   283.4 2911.91
   294.1  2912.6   326.3 2908.84   329.5  2908.7   338.8 2909.59  350.25 2907.46
   357.2 2906.36   366.4 2906.39371.80512907.489   384.8 2914.23   411.3 2934.86
   414.2 2936.35   417.3 2937.04     423 2937.22   433.2  2937.3   440.3 2936.52
   444.9 2937.11   467.9 2944.74   475.8 2946.74   481.8 2947.56   499.1 2952.75
#Mann= 8, -1 ,  0
       0    0.06       0     100    0.05       0     200    0.07       0
     210     0.1       0     320    0.06       0  350.25   0.045       0
371.8051    0.06       0     440     0.1       0
Bank Sta=350.25,371.8051
XS Rating Curve= 0 ,0
Exp/Cntr=0.3,0.1

Type RM Length L Ch R = 1 ,18659   ,65.3,65.3,65.3
XS GIS Cut Line= 4
  2328165.517239646362.6425415562328376.22904173646317.768731715
 2328482.5604607646332.4014957942328658.15362964646374.348752819
#Sta/Elev= 30
       0 2928.13    31.3 2926.11    64.2 2922.68    76.3 2921.37    96.8 2918.43
   113.1 2917.16   145.9 2912.32   162.2 2910.58   203.1 2908.06   215.4 2908.03
   227.5 2907.57   239.7 2906.57   251.7 2906.47   257.5 2905.57     261 2904.79
   267.9 2904.44     284 2905.03  287.63 2905.56   353.2 2914.59   365.6 2915.51
   373.8 2916.59   391.1 2922.34   394.3 2923.77   402.6 2925.39   410.8 2928.13
   423.1 2928.63   460.1 2928.94   472.5  2930.2   484.8  2932.9   503.3 2934.11
#Mann= 5, -1 ,  0
       0    0.06       0   257.5   0.045       0  287.63    0.06       0
  342.77     0.1       0  442.77    0.06       0
Bank Sta=257.5,287.63
XS Rating Curve= 0 ,0
Exp/Cntr(USF)=0,0
Exp/Cntr=0.3,0.1

Type RM Length L Ch R = 1 ,18593   ,155.7,155.7,155.7
XS GIS Cut Line= 4
 2328132.3746887646426.779194788 2328351.8411016646375.324270424
2328448.41734452646390.932552107 2328655.6649743646413.343792533
#Sta/Elev= 30
       0 2933.17    12.1 2931.76    86.1 2926.84   118.9 2921.98   127.2 2921.54
   143.6 2918.05   155.9 2916.34   168.2 2912.69   176.5 2911.08   214.2 2908.29
   225.8 2908.12   237.9 2906.74     242 2907.09   247.7  2905.7   254.1 2904.48
   266.3 2904.46  273.64 2905.69   278.4 2906.83   318.9 2907.49   335.1 2909.22
   355.2 2908.89   375.9 2909.66   387.4 2911.19   419.6 2920.67   435.7 2923.26
   447.7 2924.21   463.8 2926.66   508.1  2929.2   524.2  2931.4   531.7 2933.64
#Mann= 5, -1 ,  0
       0    0.06       0      70     0.1       0   247.7   0.045       0
  273.64     0.1       0  275.42    0.06       0
Bank Sta=247.7,273.64
XS Rating Curve= 0 ,0
Exp/Cntr(USF)=0,0
Exp/Cntr=0.3,0.1

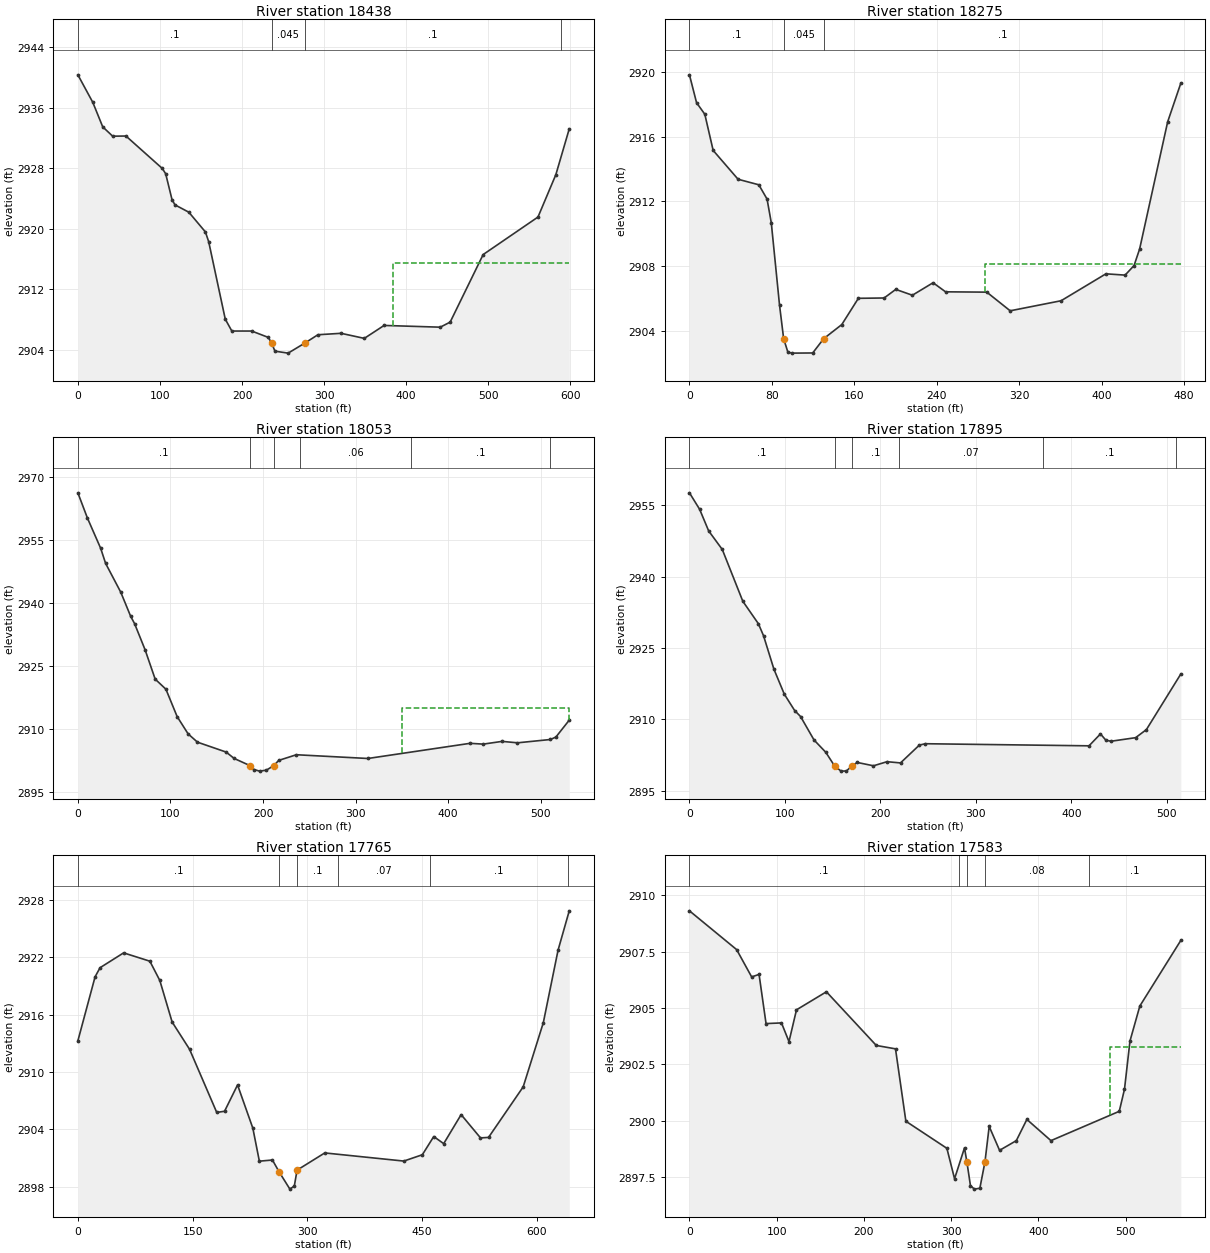
Type RM Length L Ch R = 1 ,18438   ,162.3,162.3,162.3
XS GIS Cut Line= 3
2328106.09753466646498.8167217712328462.30916531646544.850944354
2328700.49503872646519.530222583
#Sta/Elev= 30
       0 2940.36    18.2 2936.72    30.3 2933.48    42.4 2932.25    58.6 2932.27
   102.9 2927.98     107 2927.28   114.7 2923.87   118.3 2923.17   135.2  2922.2
   155.4 2919.59   159.4  2918.3   179.6 2908.06   187.6 2906.49   211.8 2906.49
     232 2905.65   236.1  2904.9   240.1 2903.83   256.2 2903.57   276.4 2904.89
   292.5    2906   320.7 2906.19     349 2905.52   373.1 2907.23   441.5    2907
   453.6 2907.67   493.8  2916.6   560.6 2921.56   582.4 2927.17   598.7 2933.22
#Mann= 4, -1 ,  0
       0     0.1       0   236.1   0.045       0   276.4     0.1       0
  589.17    0.06       0
#XS Ineff= 2 , 0
                          383.61         2915.55
Permanent Ineff=
       F       F
Bank Sta=236.1,276.4
XS Rating Curve= 0 ,0
Exp/Cntr=0.3,0.1

Type RM Length L Ch R = 1 ,18275   ,222.1,222.1,222.1
XS GIS Cut Line= 3
2328225.33591933646703.7169219962328493.81828054646672.588532291
2328645.56918035646532.510778616
#Sta/Elev= 30
       0 2919.81     6.9 2918.09    14.9 2917.38      23 2915.15    47.2 2913.37
    67.3 2913.03    75.3 2912.15    79.4 2910.69    87.4 2905.61    91.4 2903.54
    95.5 2902.71    99.5 2902.65   119.6 2902.66  130.24 2903.54   147.8 2904.41
   163.9 2906.03   188.9 2906.05   200.2 2906.58   216.3 2906.22   236.4 2906.99
   248.5 2906.43   288.5 2906.41   311.2 2905.26   360.6 2905.88   404.1 2907.54
   422.7 2907.46   431.4 2908.05   436.8 2909.07     464 2916.91   476.8  2919.3
#Mann= 3, -1 ,  0
       0     0.1       0    91.4   0.045       0  130.24     0.1       0
#XS Ineff= 2 , 0
                          287.17         2908.15
Permanent Ineff=
       F       F
Bank Sta=91.4,130.24
XS Rating Curve= 0 ,0
Exp/Cntr(USF)=0,0
Exp/Cntr=0.3,0.1

Type RM Length L Ch R = 1 ,18053   ,158.1,158.1,158.1
XS GIS Cut Line= 2
2328318.00724972647001.5271642942328709.69369054646643.486509707
#Sta/Elev= 30
       0 2966.13    10.3 2960.14    24.6 2952.94      30 2949.32    46.3 2942.49
    57.1  2936.7    61.2 2935.02    72.6 2928.77    83.5 2921.78    95.1 2919.38
   107.2 2912.87   119.1 2908.74   129.2 2906.77   160.1 2904.42   168.8  2902.9
   185.8  2901.2   190.2 2900.26   196.2 2899.88   203.5  2900.1   211.3 2901.15
     217 2902.44     236 2903.78   313.2 2902.89   423.6  2906.5   437.8 2906.31
   458.2 2906.96   474.8 2906.62   510.4 2907.41   516.3    2908   530.7 2912.02
#Mann= 6, -1 ,  0
       0     0.1       0   185.8   0.045       0   211.3     0.1       0
     240    0.06       0     360     0.1       0     510    0.06       0
#XS Ineff= 2 , 0
                          349.83         2914.89
Permanent Ineff=
       F       F
Bank Sta=185.8,211.3
XS Rating Curve= 0 ,0
Exp/Cntr(USF)=0,0
Exp/Cntr=0.3,0.1

Type RM Length L Ch R = 1 ,17895   ,130.6,130.6,130.6
XS GIS Cut Line= 2
2328431.01341198647108.4514887182328810.07036417646760.046352427
#Sta/Elev= 30
       0 2957.56    10.7 2954.09    20.1 2949.58    34.4 2945.67    55.9 2934.81
    72.2  2930.1    77.6 2927.58    88.5 2920.55    99.4  2915.3   110.2 2911.88
   116.4 2910.62   130.5  2905.7   142.8 2903.12     152 2900.26   158.8 2899.16
   164.5 2899.19     170 2900.24   175.8 2900.98   192.8 2900.28     207 2901.14
   221.1 2900.88   240.9 2904.63   247.2 2904.91   418.6 2904.47   430.6 2906.97
   436.2 2905.66   441.6 2905.43   467.4 2906.18   478.7 2907.87   514.8 2919.55
#Mann= 6, -1 ,  0
       0     0.1       0     152   0.045       0     170     0.1       0
     220    0.07       0     370     0.1       0     510    0.06       0
Bank Sta=152,170
XS Rating Curve= 0 ,0
Exp/Cntr=0.3,0.1

Type RM Length L Ch R = 1 ,17765   ,181.9,181.9,181.9
XS GIS Cut Line= 2
2328429.02974326647254.985235792 2328935.6576832646860.329413011
#Sta/Elev= 30
       0 2913.25    22.5 2919.94      29 2920.89    59.8 2922.44    94.1 2921.57
   107.1 2919.56   123.2 2915.22     146 2912.37   181.5 2905.78   191.7  2905.9
   208.7 2908.65   228.7 2904.13   237.2 2900.69   254.3 2900.81   262.9 2899.59
   277.1 2897.77   282.9  2898.1   286.52899.755   322.7 2901.55     426  2900.7
   450.2 2901.36   465.1 2903.26   478.1 2902.52   500.9 2905.55   526.2 2903.12
   536.7 2903.17     582 2908.45   608.3 2915.15   627.6 2922.73   642.2 2926.83
#Mann= 6, -1 ,  0
       0     0.1       0   262.9   0.045       0   286.5     0.1       0
     340    0.07       0     460     0.1       0     640    0.06       0
Bank Sta=262.9,286.5
XS Rating Curve= 0 ,0
Exp/Cntr(USF)=0,0
Exp/Cntr=0.3,0.1

Type RM Length L Ch R = 1 ,17583   ,261.1,261.1,261.1
XS GIS Cut Line= 3
 2328529.6472668647336.0682107822328714.88023755647264.916571752
2328959.51402302646994.186789475
#Sta/Elev= 30
       0 2909.31    54.1 2907.59    71.3 2906.38    79.8 2906.49    87.8 2904.31
   105.5 2904.34   114.1 2903.51   122.7 2904.92     157 2905.72   214.2 2903.34
   236.2 2903.19   248.1 2899.98   295.1 2898.78   303.9 2897.43   315.3  2898.8
   318.1 2898.16   322.1 2897.13   326.6 2896.97   332.9 2897.01  338.73 2898.17
   343.6 2899.75   355.5 2898.69   374.7 2899.12   386.8 2900.06   414.4 2899.12
   492.7 2900.42   498.7  2901.4     505 2903.54   516.3 2905.09   563.3    2908
#Mann= 5, -1 ,  0
       0     0.1       0  308.43    0.08       0   318.1   0.045       0
  338.73    0.08       0  458.43     0.1       0
#XS Ineff= 2 , 0
                          481.63         2903.26
Permanent Ineff=
       F       F
Bank Sta=318.1,338.73
XS Rating Curve= 0 ,0
Exp/Cntr=0.3,0.1