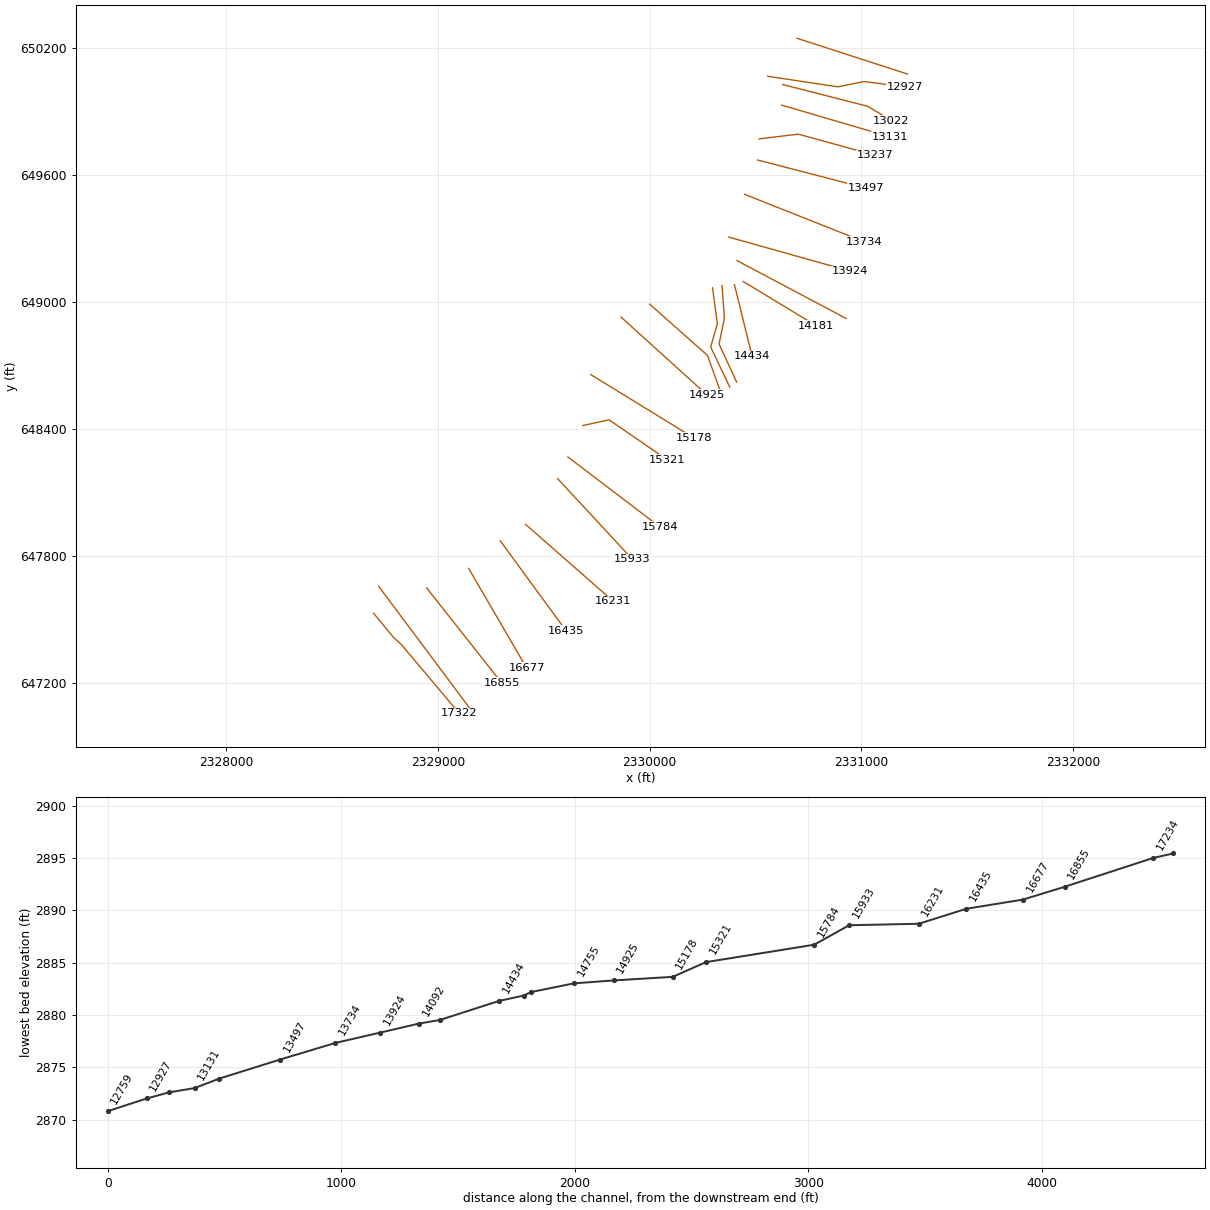
HEC-RAS study WFKGLADYFK.prj: WFKGLADYFK

--- WFKGLADYFK.g01 (geometry) --- (continued)

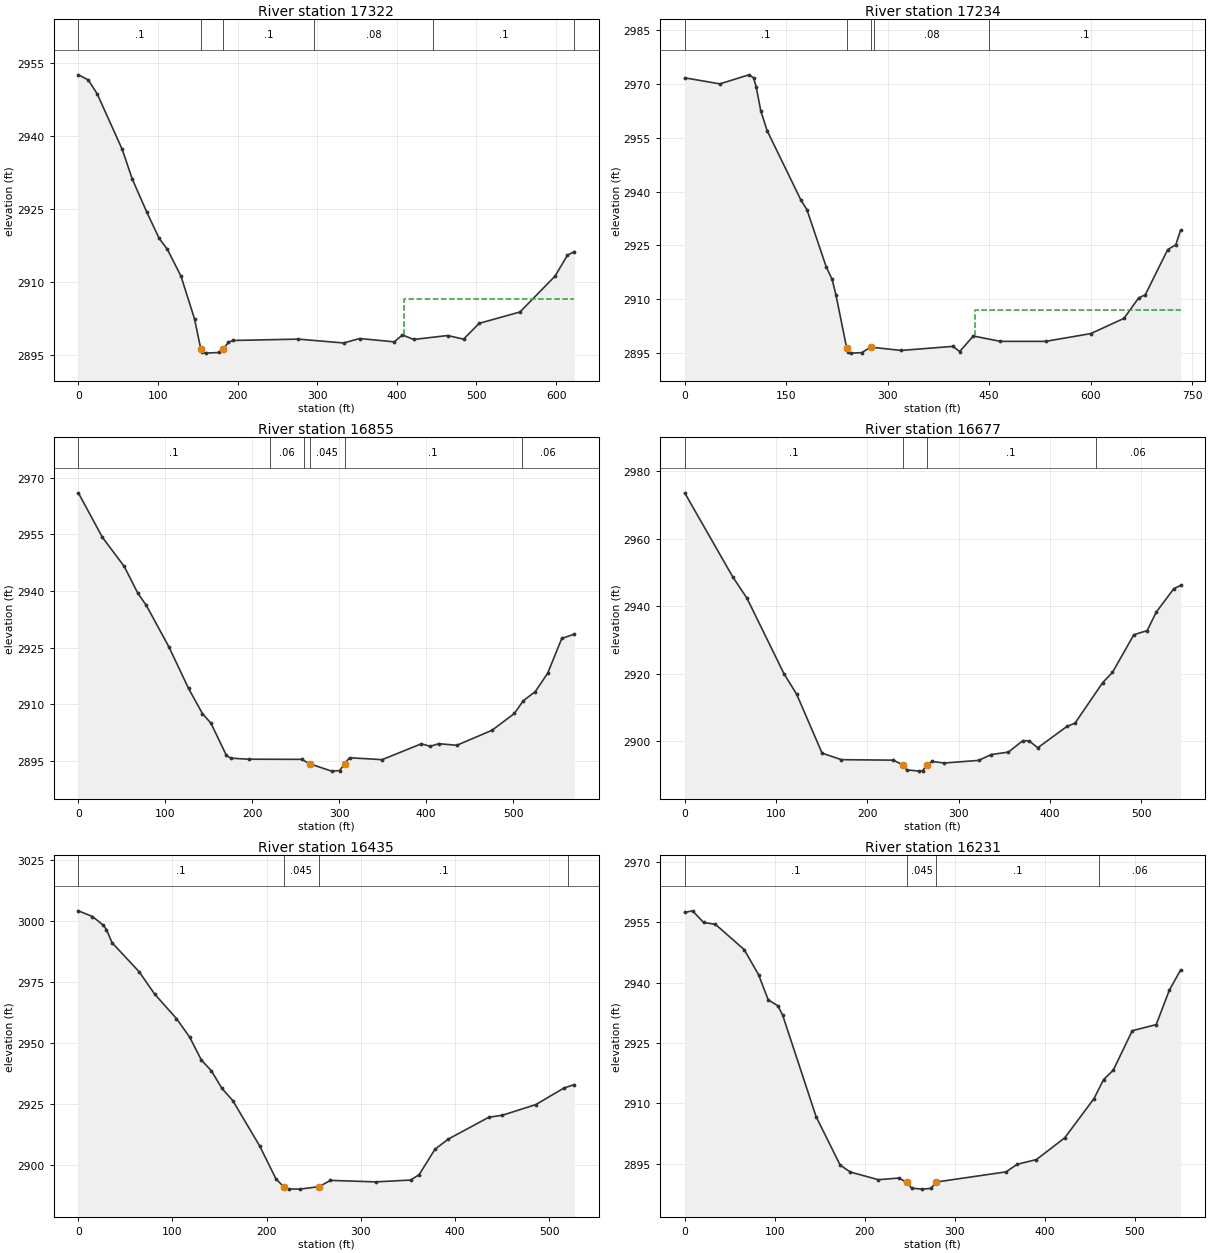
Type RM Length L Ch R = 1 ,17322   ,87.5,87.5,87.5
XS GIS Cut Line= 4
 2328697.1255758647531.5375357292328792.45626928647415.778836511
2328826.50294552647385.6232089842329101.79464197647058.775117075
#Sta/Elev= 30
       0 2952.65    12.4 2951.61    23.7 2948.73    55.1 2937.32    67.7 2931.24
      86 2924.41   101.5 2919.03   111.8 2916.78   128.9 2911.26   145.9 2902.49
   153.9  2896.2   154.9 2895.64   159.9 2895.44   176.3 2895.57   181.6 2896.21
   188.4 2897.64   194.1 2898.04   276.4 2898.32   333.2 2897.53   353.3 2898.44
   396.7 2897.76     407 2899.17   421.2 2898.25   463.8 2899.06   483.7 2898.31
   503.5 2901.57   554.6  2903.9   598.7 2911.28   614.2 2915.57   622.8 2916.31
#Mann= 6, -1 ,  0
       0     0.1       0   153.9   0.045       0   181.6     0.1       0
  295.44    0.08       0  445.44     0.1       0  622.78    0.06       0
#XS Ineff= 2 , 0
                          408.37         2906.62
Permanent Ineff=
       F       F
Bank Sta=153.9,181.6
XS Rating Curve= 0 ,0
Exp/Cntr(USF)=0,0
Exp/Cntr=0.3,0.1

Type RM Length L Ch R = 1 ,17234   ,378.6,378.6,378.6
XS GIS Cut Line= 2
2328720.89149127647658.8191009632329159.60191752647071.424387987
#Sta/Elev= 30
       0 2971.71      52 2970.02      95 2972.54   101.9  2971.7   105.8 2969.11
   112.4 2962.57   121.9 2956.98   171.8 2937.66   180.7 2934.97   209.3 2919.01
   217.9 2915.57   223.6 2911.23   239.4 2896.51   241.7 2895.29   246.4    2895
   261.7 2895.14     275 2896.67   319.7 2895.75   396.5 2896.88   406.5 2895.44
   426.6 2899.77   466.7 2898.28   533.6 2898.28   600.4 2900.45   649.4 2904.69
     671 2910.37   680.9 2911.27     714 2923.84     726  2925.2   733.1 2929.29
#Mann= 5, -1 ,  0
       0     0.1       0   239.4   0.045       0     275     0.1       0
     280    0.08       0     450     0.1       0
#XS Ineff= 2 , 0
                          429.87         2906.91
Permanent Ineff=
       F       F
Bank Sta=239.4,275
XS Rating Curve= 0 ,0
Exp/Cntr(USF)=0,0
Exp/Cntr=0.3,0.1

Type RM Length L Ch R = 1 ,16855   ,178.2,178.2,178.2
XS GIS Cut Line= 2
2328947.75396453647650.8819040072329301.08485324647203.070146764
#Sta/Elev= 30
       0 2965.99    27.6 2954.23    52.8 2946.48    68.4  2939.4    78.2 2936.16
     104 2925.25   126.8 2914.15   142.7  2907.5   152.5 2904.96   170.3 2896.41
   175.2 2895.69   195.8 2895.41   256.9 2895.37   266.4 2894.17   291.3 2892.25
   300.6  2892.4   306.3 2894.23   311.9 2895.79   349.4 2895.29   394.5 2899.49
   404.7 2898.82   414.5 2899.52   435.3  2899.1     476  2903.1   501.5 2907.53
   511.7 2910.89   525.5 2913.32   539.8 2918.18     556 2927.41   570.4 2928.54
#Mann= 6, -1 ,  0
       0     0.1       0     220    0.06       0     260     0.1       0
   266.4   0.045       0   306.3     0.1       0     510    0.06       0
Bank Sta=266.4,306.3
XS Rating Curve= 0 ,0
Exp/Cntr=0.3,0.1

Type RM Length L Ch R = 1 ,16677   ,242.7,242.7,242.7
XS GIS Cut Line= 2
2329145.79227794647743.1075283812329419.09398467 647274.00758399
#Sta/Elev= 30
       0 2973.66    52.4 2948.81    68.3 2942.31   108.7 2919.95   122.6 2913.86
   150.4 2896.37   171.6 2894.43   228.4 2894.29   238.9 2892.86   243.1  2891.4
   256.8 2891.03   260.6  2891.2   264.9 2892.79   270.7 2893.92     284 2893.44
     322 2894.22   335.5 2895.95   354.4 2896.68   370.2 2900.08   377.2    2900
   386.5 2897.96   418.5 2904.31   427.3 2905.27   457.6 2917.31   468.3 2920.36
   491.7 2931.53   506.3 2932.75   516.1 2938.19   535.5 2945.23   542.9 2946.15
#Mann= 4, -1 ,  0
       0     0.1       0   238.9   0.045       0   264.9     0.1       0
     450    0.06       0
Bank Sta=238.9,264.9
XS Rating Curve= 0 ,0
Exp/Cntr(USF)=0,0
Exp/Cntr=0.3,0.1

Type RM Length L Ch R = 1 ,16435   ,203.4,203.4,203.4
XS GIS Cut Line= 2
2329295.02492418647873.2962613062329606.00507582647448.240165312
#Sta/Elev= 30
       0 3004.19      15 3001.86    26.7 2998.26    29.9 2996.43    35.8 2991.13
    64.6 2979.21      81 2970.09   104.2 2960.05   118.3  2952.4   130.7    2943
   141.2  2938.7   152.6 2931.39   164.1 2926.39   192.7 2907.76   209.8  2894.4
   218.2 2891.06   223.2 2890.21   235.3 2890.15   255.6 2891.17   267.8 2893.74
   315.7 2893.12     353 2893.87     362  2896.1   378.7 2906.48     393 2910.67
     436 2919.62   450.3 2920.42   485.9  2924.8   515.6 2931.55   526.7 2932.97
#Mann= 4, -1 ,  0
       0     0.1       0   218.2   0.045       0   255.6     0.1       0
     520    0.06       0
Bank Sta=218.2,255.6
XS Rating Curve= 0 ,0
Exp/Cntr=0.3,0.1

Type RM Length L Ch R = 1 ,16231   ,298,298,298
XS GIS Cut Line= 2
2329414.46525087647950.9907299382329828.49694092647587.948164279
#Sta/Elev= 30
       0  2957.4     8.8  2957.8    20.9 2954.92    34.2 2954.44    66.1 2948.17
    82.1 2941.92    92.7 2935.73   103.4 2934.23   108.7 2931.97   145.9 2906.74
   172.6  2894.7   183.9 2892.96   215.1 2891.06   237.8 2891.47     247 2890.37
   251.9 2888.97   263.3 2888.72   273.6  2888.9   278.9 2890.47   356.8    2893
   369.3 2894.89   390.6 2896.06     422 2901.45   454.5 2911.19   465.1  2915.9
   475.9 2918.25     497 2928.04   523.6 2929.56   538.2 2938.12   550.7 2943.13
#Mann= 4, -1 ,  0
       0     0.1       0     247   0.045       0   278.9     0.1       0
     460    0.06       0
Bank Sta=247,278.9
XS Rating Curve= 0 ,0
Exp/Cntr(USF)=0,0
Exp/Cntr=0.3,0.1

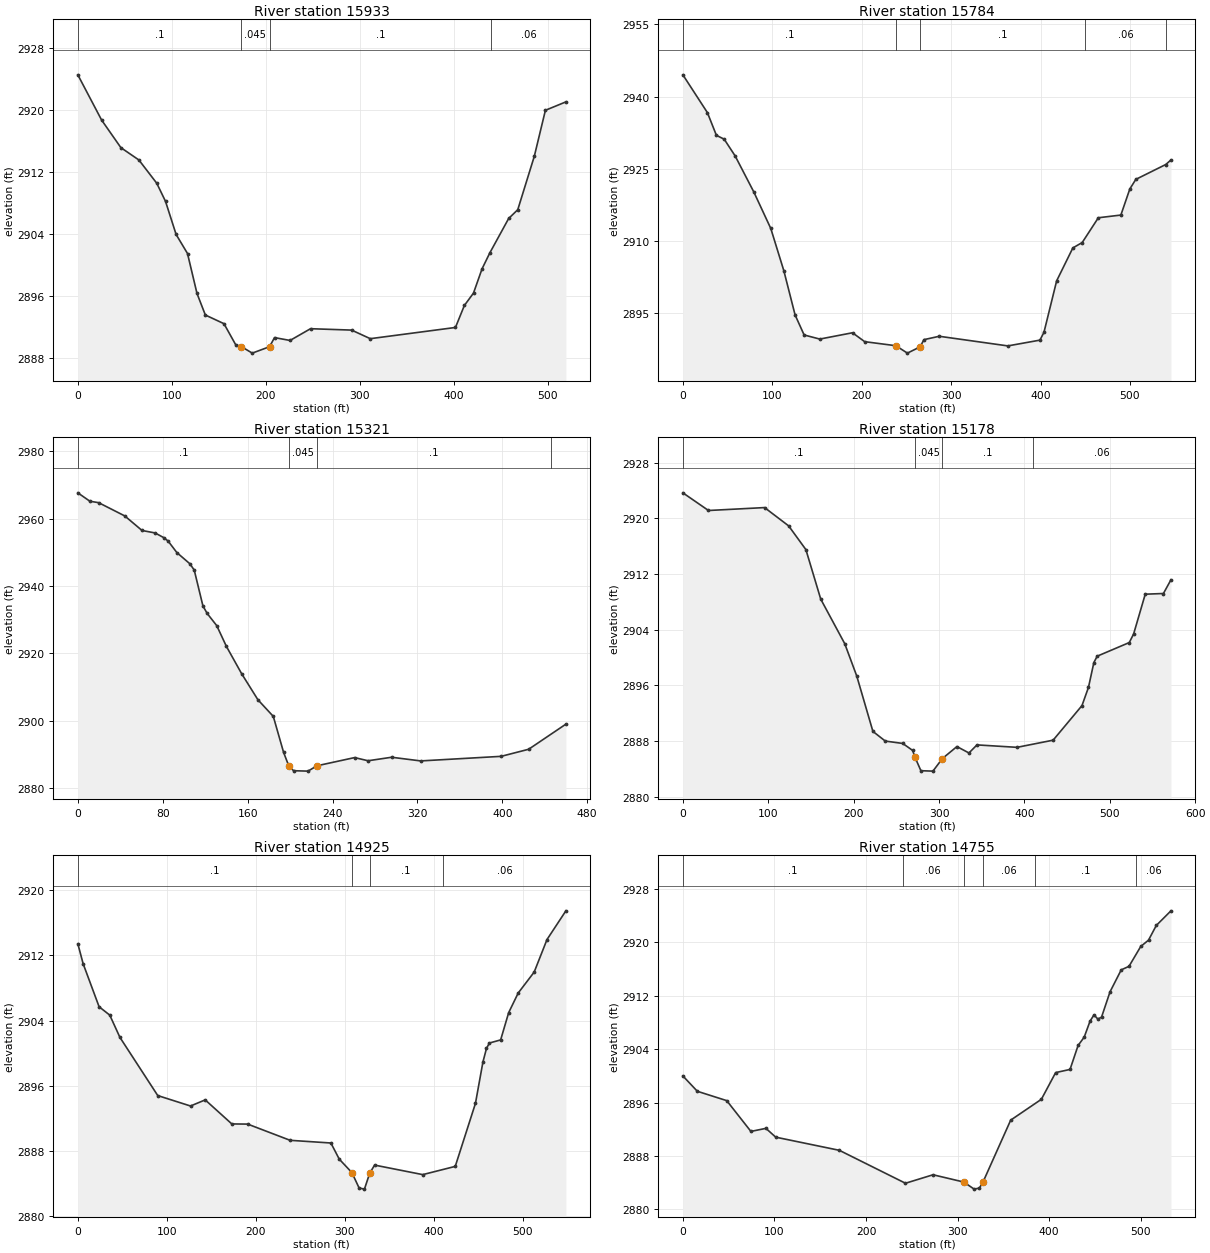
Type RM Length L Ch R = 1 ,15933   ,149.5,149.5,149.5
XS GIS Cut Line= 2
2329565.97461789648166.7986202592329918.99823638647785.943381516
#Sta/Elev= 30
       0 2924.59    25.3 2918.74    45.8 2915.17      65 2913.57      84 2910.56
    93.3 2908.22   104.6 2903.93   116.7 2901.47   126.8  2896.3   135.7 2893.51
   155.5 2892.39     168 2889.66   173.9 2889.43   185.6 2888.58     204 2889.41
   209.3 2890.59   225.8 2890.22   247.6 2891.74   291.3 2891.56   311.2 2890.45
   401.8  2891.9   411.3 2894.75     421 2896.35   430.1 2899.49   438.5 2901.58
   458.4    2906   468.1 2907.14   485.7 2914.05   497.5    2920   519.3 2921.09
#Mann= 4, -1 ,  0
       0     0.1       0   173.9   0.045       0     204     0.1       0
     440    0.06       0
Bank Sta=173.9,204
XS Rating Curve= 0 ,0
Exp/Cntr=0.3,0.1

Type RM Length L Ch R = 1 ,15784   ,462.8,462.8,462.8
XS GIS Cut Line= 2
2329614.34261848648269.1628661342330048.76995829647938.753340084
#Sta/Elev= 30
       0 2944.53    27.4 2936.69    37.5 2931.96    46.2 2931.16    58.4  2927.7
    79.3 2920.21    98.3 2912.62   112.9 2903.84   125.5 2894.65   135.6 2890.49
   153.1 2889.64   189.7 2890.95   203.3  2889.1   238.2 2888.26   251.1 2886.72
   265.32888.024   269.6 2889.52   286.7 2890.22   363.4 2888.22   399.3 2889.42
   403.8 2891.04     418 2901.74   436.1 2908.57   446.6  2909.7   464.6 2914.84
   489.8  2915.4   499.8 2920.81   506.5 2922.81     540  2925.9   545.8 2926.84
#Mann= 5, -1 ,  0
       0     0.1       0   238.2   0.045       0   265.3     0.1       0
     450    0.06       0     540     0.1       0
Bank Sta=238.2,265.3
XS Rating Curve= 0 ,0
Exp/Cntr(USF)=0,0
Exp/Cntr=0.3,0.1

Type RM Length L Ch R = 1 ,15321   ,143.1,143.1,143.1
XS GIS Cut Line= 3
2329685.03796401648417.5379252552329808.27522542648444.473710436
2330083.64766723648255.818078888
#Sta/Elev= 30
       0 2967.69    11.4 2965.19    19.6 2964.77    44.2 2960.84    60.5 2956.51
    72.8 2955.78      81 2954.38    85.1 2953.36    93.3 2949.96   105.6 2946.62
   109.7 2944.75   117.9  2934.1   121.9 2931.87   130.9 2928.26     140  2922.1
   154.3 2914.02   169.7 2906.25   184.2 2901.31   193.9 2890.62   198.8  2886.6
   203.3 2885.18   216.9 2885.06   225.4 2886.65   260.8 2889.08   273.5 2888.14
   295.7 2889.18   323.1 2888.09   398.9 2889.45   424.8 2891.55   459.9 2899.01
#Mann= 4, -1 ,  0
       0     0.1       0   198.8   0.045       0   225.4     0.1       0
  446.15    0.06       0
Bank Sta=198.8,225.4
XS Rating Curve= 0 ,0
Exp/Cntr=0.3,0.1

Type RM Length L Ch R = 1 ,15178   ,252.8,252.8,252.8
XS GIS Cut Line= 2
2329722.59820538648657.7739503382330209.82761622648358.637753915
#Sta/Elev= 30
       0 2923.65      30 2921.11    95.7 2921.53   123.9  2918.9   144.1 2915.49
   161.5 2908.37   189.6 2901.97   203.7 2897.31   222.6 2889.36   237.1 2887.97
   257.5 2887.63   269.1 2886.63     272 2885.62   278.8 2883.71   292.9 2883.65
     304 2885.46     321 2887.18   335.1 2886.26   344.5 2887.42   391.4 2887.07
   433.7  2888.1   467.5 2893.07   475.1 2895.69   481.4 2899.25   485.3 2900.17
   522.9 2902.13     528 2903.37   541.6 2909.08   562.9 2909.18   571.7 2911.15
#Mann= 4, -1 ,  0
       0     0.1       0     272   0.045       0     304     0.1       0
     410    0.06       0
Bank Sta=272,304
XS Rating Curve= 0 ,0
Exp/Cntr(USF)=0,0
Exp/Cntr=0.3,0.1

Type RM Length L Ch R = 1 ,14925   ,170.2,170.2,170.2
XS GIS Cut Line= 2
2329865.35646209 648929.236797592330271.85735405648561.333479014
#Sta/Elev= 30
       0 2913.42       6 2910.96    23.9 2905.69    35.9 2904.66    47.3 2901.93
    89.8 2894.79   126.6 2893.51   143.1 2894.26     173 2891.31   190.8 2891.29
   238.5  2889.3   284.3 2888.97   293.7 2886.99   307.9 2885.34     316 2883.45
     322 2883.31   327.9 2885.26   333.4 2886.26   387.5 2885.09     424  2886.1
   446.7 2893.83   455.1 2898.91   459.1 2900.58   462.4 2901.24     475 2901.62
     484 2904.96   494.7 2907.37   512.7 2909.95   527.1 2913.94   548.3 2917.46
#Mann= 4, -1 ,  0
       0     0.1       0   307.9   0.045       0   327.9     0.1       0
     410    0.06       0
Bank Sta=307.9,327.9
XS Rating Curve= 0 ,0
Exp/Cntr=0.3,0.1

Type RM Length L Ch R = 1 ,14755   ,185,185,185
XS GIS Cut Line= 3
2330000.33373614  648990.44947462330273.26116639648748.422868579
2330330.10181245648590.106437029
#Sta/Elev= 30
       0 2899.98    15.8 2897.68    47.9 2896.28    74.3 2891.67    90.7 2892.13
   101.4 2890.81   170.9 2888.84   243.1 2883.91   273.2 2885.18   306.8 2884.09
   318.1 2883.03   323.8 2883.19  327.79  2884.1     358 2893.36   391.5 2896.48
   407.1 2900.48   422.8 2900.95   431.6 2904.54   438.3 2905.79   444.7  2908.2
     449 2909.12   453.2 2908.49   457.2 2908.78   466.5 2912.58   478.7 2915.86
   487.2 2916.39     500 2919.36   508.5 2920.31     517 2922.51     533  2924.7
#Mann= 6, -1 ,  0
       0     0.1       0     240    0.06       0   306.8   0.045       0
  327.79    0.06       0  384.78     0.1       0  494.78    0.06       0
Bank Sta=306.8,327.79
XS Rating Curve= 0 ,0
Exp/Cntr(USF)=0,0
Exp/Cntr=0.3,0.1

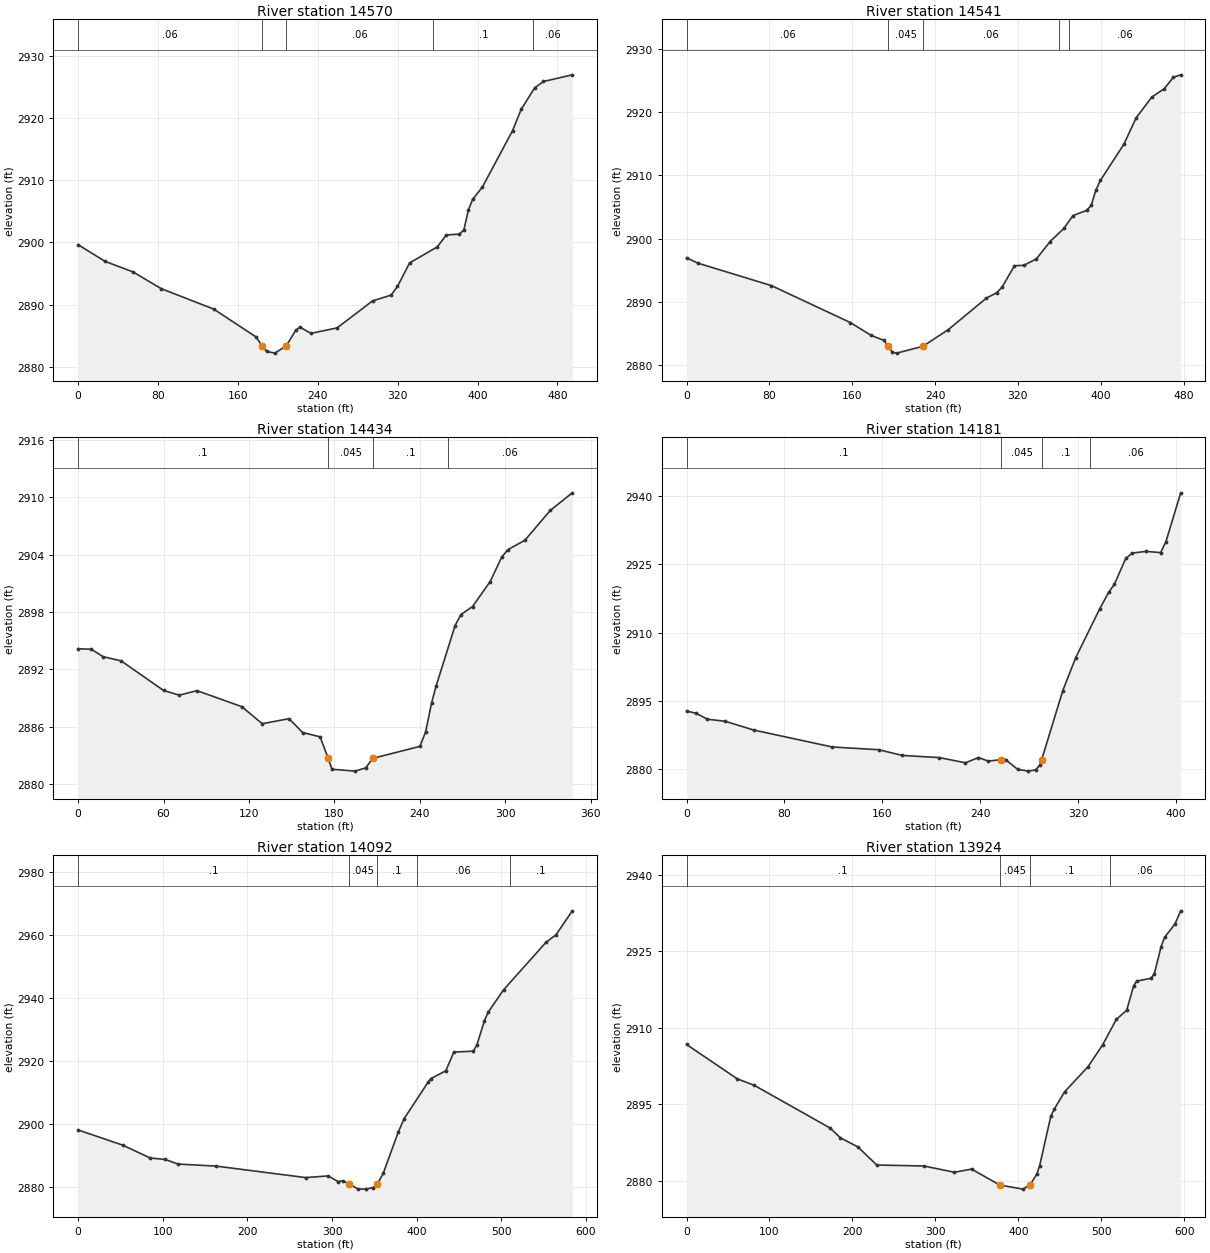
Type RM Length L Ch R = 1 ,14570   ,28.9,28.9,28.9
XS GIS Cut Line= 4
2330296.96624419649067.6512497162330319.88115274648897.764858764
2330288.27438233648787.931331591  2330378.353678648599.080878393
#Sta/Elev= 30
       0 2899.63    27.1 2896.94      55 2895.25    83.2 2892.56   135.7 2889.28
   178.1  2884.8  184.26 2883.35   188.7 2882.47     197 2882.19   208.4 2883.35
   217.8 2885.83     222 2886.38   233.1 2885.37   259.4 2886.25   294.8 2890.59
   313.4 2891.52   319.8 2892.91   331.9 2896.69   359.7 2899.28   368.7 2901.19
   381.8 2901.33   386.3 2902.01   390.7 2905.13   395.1 2906.94   404.7 2908.86
     435 2917.96   443.7  2921.4   457.2 2924.86     466 2925.88   494.9 2926.95
#Mann= 5, -1 ,  0
       0    0.06       0  184.26   0.045       0   208.4    0.06       0
  355.72     0.1       0  455.72    0.06       0
Bank Sta=184.26,208.4
XS Rating Curve= 0 ,0
Exp/Cntr(USF)=0,0
Exp/Cntr=0.3,0.1

Type RM Length L Ch R = 1 ,14541   ,107,107,107
XS GIS Cut Line= 4
2330342.00589203 649078.713619362330353.06826167648924.630613612
2330327.78284534648802.1543782752330410.75061767  648622.7859562
#Sta/Elev= 30
       0 2896.96    10.9 2896.11      82 2892.55   158.2 2886.71   178.4 2884.66
   190.7 2883.89   194.8 2882.93   198.8 2882.01   202.9 2881.87   228.3 2882.95
   252.9  2885.6   289.6 2890.58   299.5 2891.42   304.7 2892.31   316.7  2895.7
   325.8 2895.76   337.9 2896.79   351.1 2899.53   364.3 2901.59   373.2 2903.63
   386.4 2904.45   390.8 2905.25   395.2 2907.61   399.6 2909.19   422.2 2914.88
   434.2  2919.1   449.3 2922.38   461.4 2923.71   470.1 2925.52   477.2  2925.9
#Mann= 5, -1 ,  0
       0    0.06       0   194.8   0.045       0   228.3    0.06       0
  359.54     0.1       0  369.54    0.06       0
Bank Sta=194.8,228.3
XS Rating Curve= 0 ,0
Exp/Cntr(USF)=0,0
Exp/Cntr=0.3,0.1

Type RM Length L Ch R = 1 ,14434   ,253.1,253.1,253.1
XS GIS Cut Line= 2
2330400.63557109649082.2353822192330483.88876114648745.132192404
#Sta/Elev= 30
       0 2894.16     9.3  2894.1    17.6 2893.32    30.2 2892.89      60 2889.79
    71.1  2889.3    83.5 2889.77   114.9  2888.1   129.4 2886.31   148.2 2886.84
   157.7 2885.39     170 2884.94   175.6 2882.73   178.3 2881.55   194.7 2881.35
     202 2881.69   207.1 2882.69   240.1 2883.94   244.2 2885.48   248.3 2888.48
   251.6  2890.3   264.8 2896.56   268.9 2897.73   277.1 2898.57   289.5 2901.19
   297.5 2903.72   301.9 2904.52   313.9 2905.51   331.7 2908.63   347.2 2910.47
#Mann= 4, -1 ,  0
       0     0.1       0   175.6   0.045       0   207.1     0.1       0
     260    0.06       0
Bank Sta=175.6,207.1
XS Rating Curve= 0 ,0
Exp/Cntr=0.3,0.1

Type RM Length L Ch R = 1 ,14181   ,89.3,89.3,89.3
XS GIS Cut Line= 2
2330441.24821734649097.8014378362330786.57879063648888.657569502
#Sta/Elev= 30
       0 2892.78     8.1 2892.23    17.1 2890.95    31.7  2890.5    54.9 2888.57
   119.1 2884.84   156.9 2884.24   176.4 2882.98   206.5 2882.51   227.9 2881.36
   238.5 2882.52   246.6 2881.73   257.32882.073   260.6 2882.08   270.5 2879.92
   279.3 2879.53   285.1 2879.81   288.7 2880.87   290.12882.022   307.4 2897.26
   317.8 2904.42   337.5 2915.23   344.8 2918.84   349.5 2920.63   358.8 2926.33
   364.1 2927.51   375.4 2927.89   387.3 2927.61   391.6    2930   403.7 2940.77
#Mann= 4, -1 ,  0
       0     0.1       0   257.3   0.045       0   290.1     0.1       0
     330    0.06       0
Bank Sta=257.3,290.1
XS Rating Curve= 0 ,0
Exp/Cntr(USF)=0,0
Exp/Cntr=0.3,0.1

Type RM Length L Ch R = 1 ,14092   ,167.1,167.1,167.1
XS GIS Cut Line= 2
 2330412.0725995 649196.313864262330927.87858183 648922.80820103
#Sta/Elev= 30
       0 2897.99    52.7 2893.16    85.2 2889.08     103 2888.62   117.7 2887.16
   163.1 2886.51   268.7 2882.86   295.3 2883.39   307.1 2881.59   312.5 2881.85
   320.4 2880.79   330.6 2879.23   339.7 2879.19   348.6 2879.68   353.3 2880.73
   360.4 2884.18   378.1 2897.25     385 2901.54   413.7 2913.29   416.6 2914.29
   434.4  2916.8   443.8 2922.74   466.9 2923.04     471 2924.99     480 2932.71
   484.2 2935.34   502.7 2942.57   552.7 2957.62   564.5    2960   583.8 2967.63
#Mann= 5, -1 ,  0
       0     0.1       0   320.4   0.045       0   353.3     0.1       0
     400    0.06       0     510     0.1       0
Bank Sta=320.4,353.3
XS Rating Curve= 0 ,0
Exp/Cntr(USF)=0,0
Exp/Cntr=0.3,0.1

Type RM Length L Ch R = 1 ,13924   ,190.8,190.8,190.8
XS GIS Cut Line= 2
  2330373.381262649307.1121171622330946.86994024 649146.26390521
#Sta/Elev= 30
       0 2906.71    61.1 2899.97    81.8 2898.68   173.2  2890.3   185.5 2888.38
   206.5 2886.61   229.3 2883.05   286.1 2882.86   322.8 2881.63   343.6 2882.25
   377.5 2879.12   405.4 2878.32   414.2 2879.16   422.5 2881.38   425.6 2882.91
   439.1 2892.67   443.3 2894.04   455.7 2897.42     484 2902.36   501.4 2906.61
     518 2911.62   530.5 2913.42   538.8 2918.16   542.4 2919.13   559.6 2919.69
   563.7 2920.51     572 2925.92   576.2 2927.72   588.7 2930.36   595.6 2932.93
#Mann= 4, -1 ,  0
       0     0.1       0   377.5   0.045       0   414.2     0.1       0
     510    0.06       0
Bank Sta=377.5,414.2
XS Rating Curve= 0 ,0
Exp/Cntr=0.3,0.1

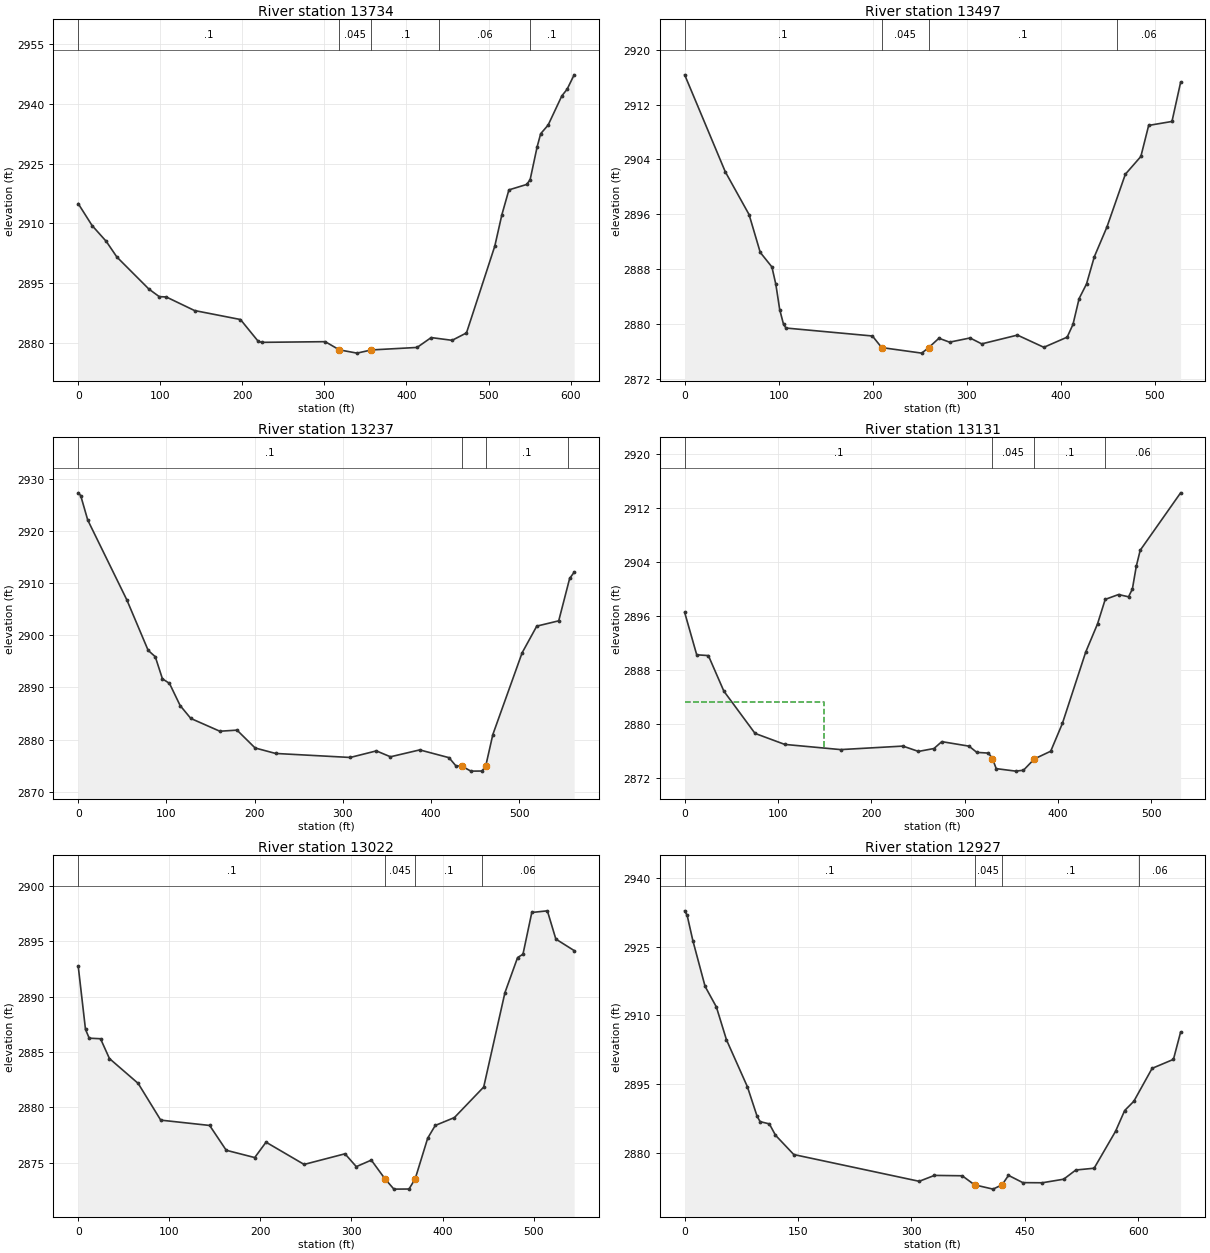
Type RM Length L Ch R = 1 ,13734   ,237,237,237
XS GIS Cut Line= 2
2330448.42730895649508.9541333672331010.12926685649285.985472704
#Sta/Elev= 30
       0 2914.93    16.9 2909.42    34.2 2905.43    47.1 2901.51    86.1 2893.45
    98.7 2891.55   107.3 2891.46   141.7 2888.05   197.7 2885.79   219.2 2880.34
   223.5 2880.05     301 2880.22   318.2 2878.16   339.7 2877.34   357.2 2878.14
   412.9 2878.77   430.1 2881.25   455.6 2880.56   473.1 2882.42   507.6 2904.24
   516.2 2912.11   524.8 2918.38   546.3 2919.74   550.6 2920.89   559.2 2929.21
   563.5  2932.5   572.6 2934.68   589.3 2942.02   595.7 2943.68   604.3 2947.31
#Mann= 5, -1 ,  0
       0     0.1       0   318.2   0.045       0   357.2     0.1       0
     440    0.06       0     550     0.1       0
Bank Sta=318.2,357.2
XS Rating Curve= 0 ,0
Exp/Cntr(USF)=0,0
Exp/Cntr=0.3,0.1

Type RM Length L Ch R = 1 ,13497   ,259.4,259.4,259.4
XS GIS Cut Line= 2
2330510.31433199649670.758360853 2331021.0144756649538.462704605
#Sta/Elev= 30
       0 2916.34    43.2  2902.2    68.5 2895.96    80.4 2890.44    92.8 2888.32
      97 2885.77   101.1 2882.09   105.2 2879.93   107.8 2879.41   199.7 2878.25
   209.6 2876.56   252.2 2875.75  259.53 2876.55   270.5 2877.92   281.8 2877.35
   303.6 2877.96     316  2877.1     354 2878.38   382.1  2876.6   406.9 2878.08
   413.1 2879.94   419.6  2883.7   427.5 2885.84   435.8 2889.81   449.2 2894.14
   468.8 2901.84   485.3 2904.43   493.6 2908.96   518.4 2909.54   527.6 2915.25
#Mann= 4, -1 ,  0
       0     0.1       0   209.6   0.045       0  259.53     0.1       0
     460    0.06       0
Bank Sta=209.6,259.53
XS Rating Curve= 0 ,0
Exp/Cntr(USF)=0,0
Exp/Cntr=0.3,0.1

Type RM Length L Ch R = 1 ,13237   ,106,106,106
XS GIS Cut Line= 3
2330517.40419117649770.6753343482330701.82697471649792.862193689
2331065.03387031649693.280233005
#Sta/Elev= 30
       0  2927.3     2.8 2926.78    10.8 2922.08    55.2 2906.75    79.3  2897.1
    87.4 2895.87    95.5 2891.64   103.5 2890.76   115.6 2886.51   127.7 2884.04
   160.6 2881.59   180.1  2881.8   200.6 2878.38   223.8 2877.33   308.5 2876.56
   338.1 2877.82   354.1 2876.69   387.3 2878.01   420.5 2876.52   428.3 2874.95
  435.03 2874.89   445.3 2873.94   457.8 2873.96  462.08 2874.89   470.2 2880.96
   503.4 2896.63     520 2901.74   544.9 2902.76   557.3 2910.89   562.4 2912.07
#Mann= 4, -1 ,  0
       0     0.1       0  435.03   0.045       0  462.08     0.1       0
  555.75    0.06       0
Bank Sta=435.03,462.08
XS Rating Curve= 0 ,0
Exp/Cntr=0.3,0.1

Type RM Length L Ch R = 1 ,13131   ,109.3,109.3,109.3
XS GIS Cut Line= 2
2330623.83575112649929.8564423722331133.72699502 649780.28834416
#Sta/Elev= 30
       0 2896.54    12.9 2890.27    25.4 2890.15      42 2884.88    75.4 2878.62
   107.2 2876.99   167.1 2876.22   233.8 2876.74   250.5 2875.95   267.1 2876.38
   275.5  2877.4   304.7 2876.73     313 2875.81   325.5  2875.7   329.8 2874.89
   333.8  2873.4   354.7 2873.03     363 2873.16   374.7 2874.84   392.2 2875.98
   404.7 2880.09   429.7 2890.67   442.4 2894.86   450.6 2898.48   464.9  2899.2
   475.6 2898.86   479.7 2900.01   483.9 2903.39   488.1 2905.76   531.4 2914.27
#Mann= 4, -1 ,  0
       0     0.1       0   329.8   0.045       0   374.7     0.1       0
     450    0.06       0
#XS Ineff= 2 , 0
          149.73 2883.32
Permanent Ineff=
       F       F
Bank Sta=329.8,374.7
XS Rating Curve= 0 ,0
Exp/Cntr(USF)=0,0
Exp/Cntr=0.3,0.1

Type RM Length L Ch R = 1 ,13022   ,95.5,95.5,95.5
XS GIS Cut Line= 3
2330628.42445686650027.1935093812331028.52154079649924.761652006
2331141.45922969 649857.34923305
#Sta/Elev= 30
       0 2892.76       8 2887.04    12.1 2886.25    24.5  2886.2    34.3 2884.41
    65.8 2882.17    90.6 2878.85   144.3 2878.37   162.5 2876.13   193.8 2875.47
   206.2 2876.86     248 2874.85   292.9 2875.81   305.3 2874.65   321.8 2875.24
   336.8 2873.55   346.6 2872.62   363.2 2872.63  369.97 2873.55   383.7 2877.22
     392 2878.37     413 2879.08   445.2 2881.84   468.5 2890.36   482.4 2893.53
   488.3 2893.83     498  2897.6   515.1 2897.75   524.4  2895.2   544.5 2894.16
#Mann= 4, -1 ,  0
       0     0.1       0   336.8   0.045       0  369.97     0.1       0
     443    0.06       0
Bank Sta=336.8,369.97
XS Rating Curve= 0 ,0
Exp/Cntr(USF)=0,0
Exp/Cntr=0.3,0.1

Type RM Length L Ch R = 1 ,12927   ,167.3,167.3,167.3
XS GIS Cut Line= 4
2330557.45806547650066.1823829812330888.45068412650016.403266775
2331012.79111823650041.3873010262331205.61895252650015.930900163
#Sta/Elev= 30
       0 2932.87     3.3 2931.86    10.8 2926.37      27 2916.35    41.9 2911.87
    55.3 2904.67      83  2894.4    95.8 2887.96    99.8 2886.79     112  2886.3
   120.1 2883.83   144.3  2879.6   310.2 2873.75   330.4 2875.04   367.1 2874.96
   383.4 2872.98   407.9 2872.04   419.9 2872.99   428.3 2875.05   447.3 2873.46
     473 2873.43   501.3 2874.21   517.4 2876.22   541.6 2876.61   569.9 2884.67
     582 2889.22   594.1 2891.24   618.3 2898.44   646.5  2900.4     656 2906.36
#Mann= 4, -1 ,  0
       0     0.1       0   383.4   0.045       0   419.9     0.1       0
  601.54    0.06       0
Bank Sta=383.4,419.9
XS Rating Curve= 0 ,0
Exp/Cntr=0.3,0.1

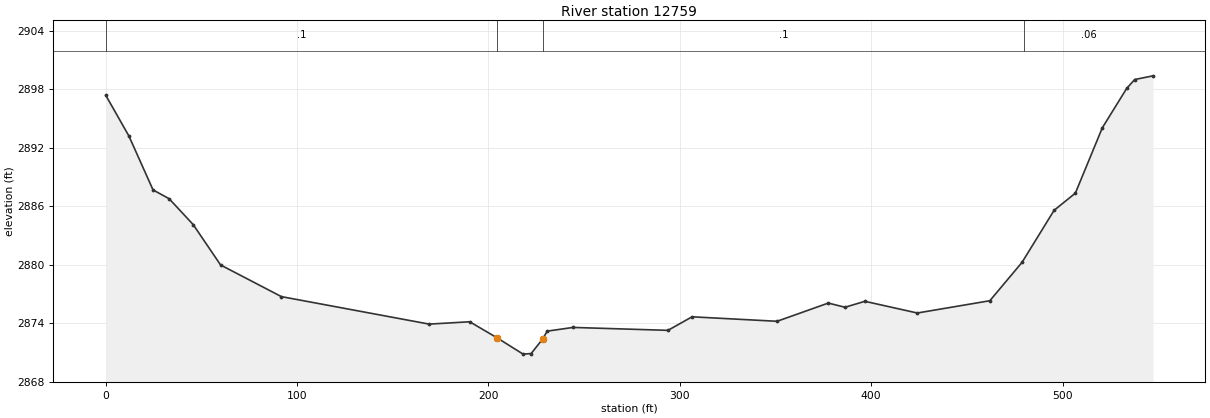
Type RM Length L Ch R = 1 ,12759   ,439.7,439.7,439.7
XS GIS Cut Line= 2
2330696.65699272 650245.240988712331217.38281813650076.652382419
#Sta/Elev= 30
       0 2897.38    12.1  2893.2    24.7 2887.67    33.1 2886.77    45.7 2884.11
      60 2879.97    91.8 2876.72     169  2873.9   190.2 2874.14204.66842872.471
   218.1 2870.82   222.3 2870.88228.28012872.363   230.7 2873.18   244.2 2873.56
   293.8 2873.26   306.4 2874.65   350.8 2874.19   377.6 2876.06   386.3 2875.63
   396.7 2876.24   424.1 2875.04     462  2876.3   478.8 2880.23   495.6 2885.58
   506.7 2887.34   520.8 2894.05   533.5 2898.08   537.7    2899   547.3 2899.38
#Mann= 4, -1 ,  0
       0     0.1       0204.6684   0.045       0228.2801     0.1       0
     480    0.06       0
Bank Sta=204.6684,228.2801
XS Rating Curve= 0 ,0
Exp/Cntr(USF)=0,0
Exp/Cntr=0.3,0.1