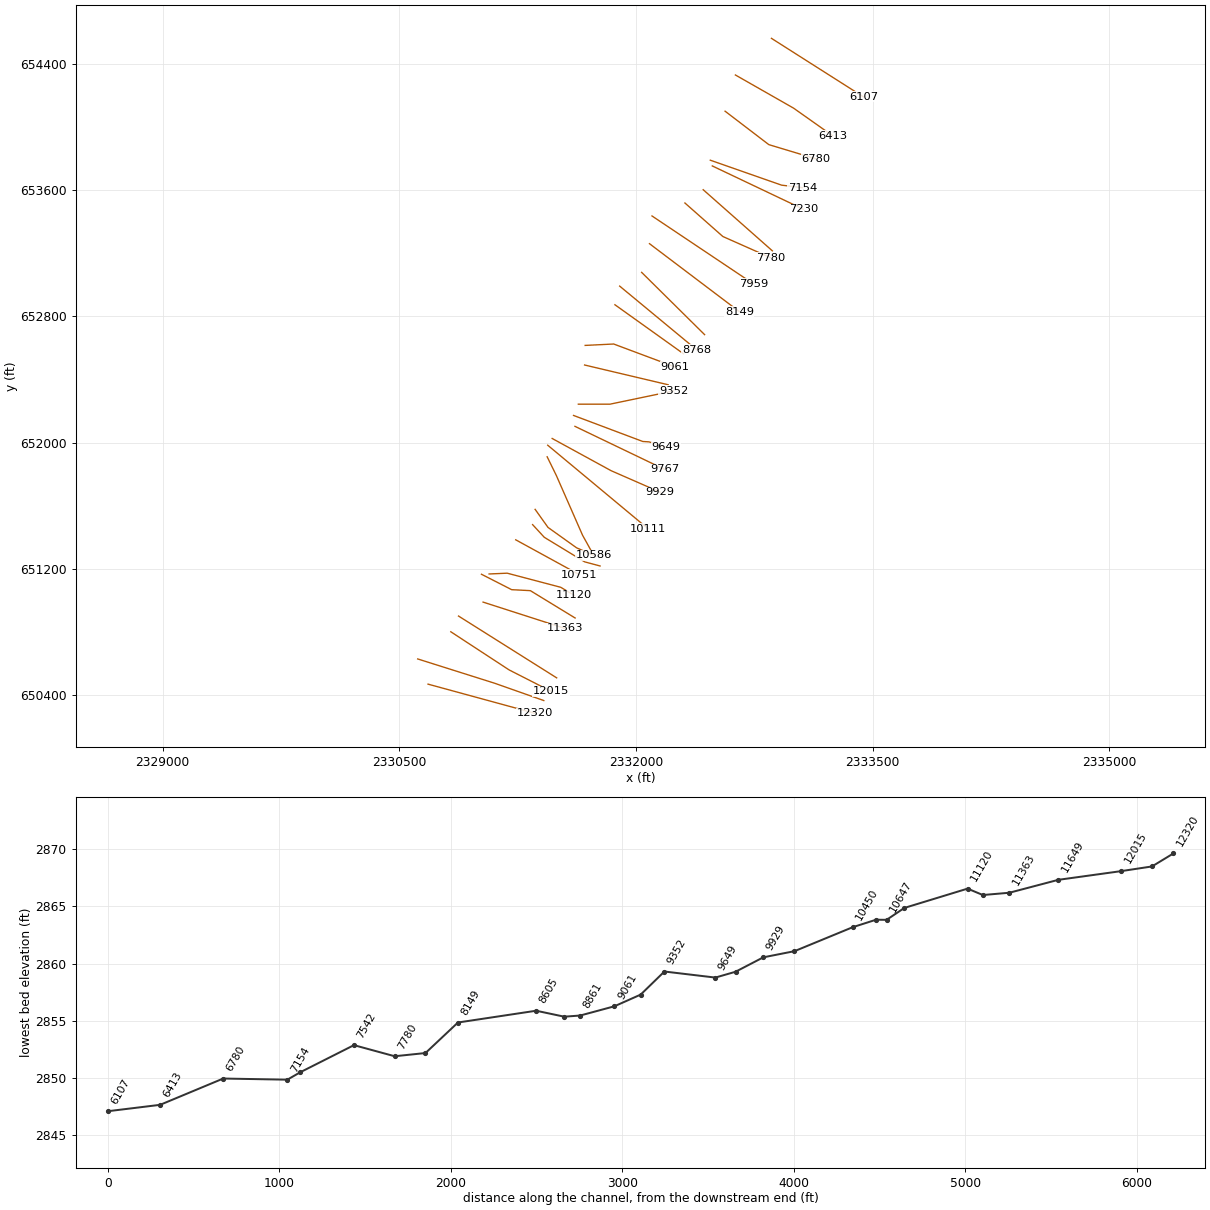
HEC-RAS study WFKGLADYFK.prj: WFKGLADYFK

--- WFKGLADYFK.g01 (geometry) --- (continued)

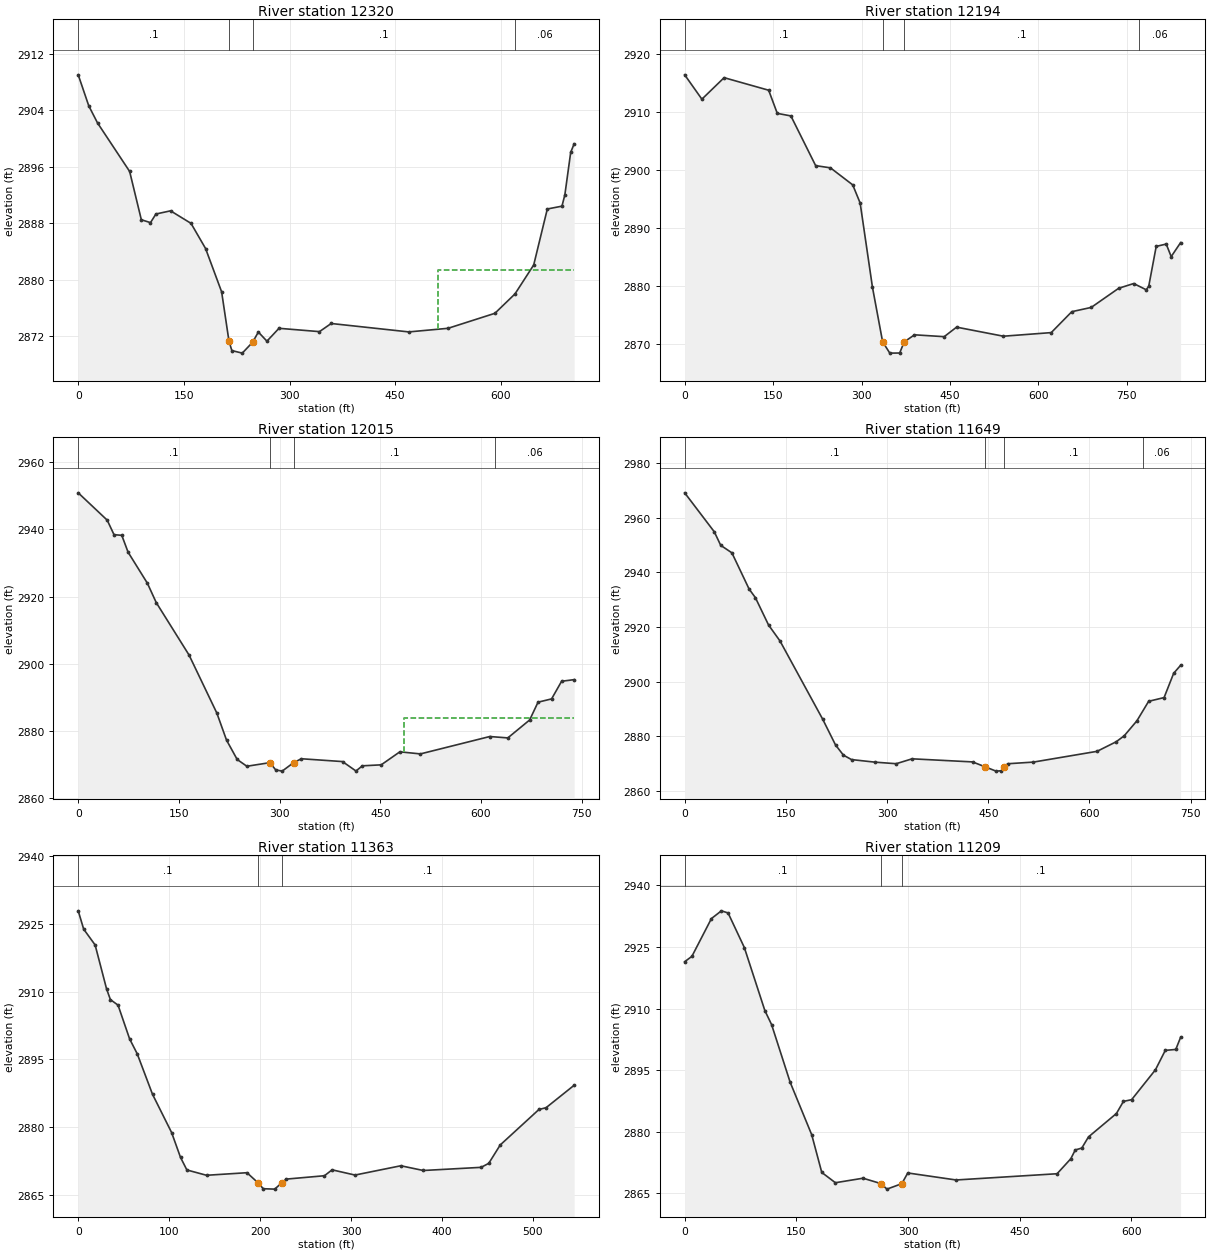
Type RM Length L Ch R = 1 ,12320   ,125.1,125.1,125.1
XS GIS Cut Line= 2
2330681.74514936650468.7507616752331360.92028624650283.354305392
#Sta/Elev= 30
       0 2908.99      15  2904.6    27.4 2902.19      73 2895.33    89.6  2888.5
   102.6 2888.09   110.3 2889.31   131.1 2889.76   160.1 2887.99   180.8 2884.43
   203.6  2878.3     214 2871.34   218.1    2870   232.9 2869.64   247.62871.183
   255.7 2872.62   267.9 2871.33     285 2873.15   342.5 2872.68   359.1 2873.83
   469.3 2872.64     525 2873.15   591.5 2875.27     620 2878.01   646.6 2882.11
   665.9 2890.02   686.7 2890.42   690.8 2892.02   699.1 2898.03     704 2899.24
#Mann= 4, -1 ,  0
       0     0.1       0     214   0.045       0   247.6     0.1       0
     620    0.06       0
#XS Ineff= 2 , 0
                          510.02         2881.37
Permanent Ineff=
       F       F
Bank Sta=214,247.6
XS Rating Curve= 0 ,0
Exp/Cntr(USF)=0,0
Exp/Cntr=0.3,0.1

Type RM Length L Ch R = 1 ,12194   ,179.8,179.8,179.8
XS GIS Cut Line= 3
2330616.34281222650628.5091635472331102.70858773650474.843502906
2331415.21762543650364.765168002
#Sta/Elev= 30
       0 2916.37    29.2 2912.18    66.9 2915.88   142.5 2913.72   157.1 2909.74
   180.2  2909.3   222.2 2900.75   247.3 2900.37   285.1 2897.44   297.7 2894.32
   318.6 2879.82   335.82870.457     348  2868.5   364.8 2868.52   372.3 2870.42
   389.9 2871.65   440.3 2871.33   461.3 2872.97   540.7 2871.41   621.9 2872.03
   656.8 2875.63   689.7 2876.36   736.4 2879.66   761.8 2880.47     783  2879.4
   787.3    2880     800 2886.86     817 2887.26   825.4  2885.1   841.4 2887.51
#Mann= 4, -1 ,  0
       0     0.1       0   335.8   0.045       0   372.3     0.1       0
  770.06    0.06       0
Bank Sta=335.8,372.3
XS Rating Curve= 0 ,0
Exp/Cntr(USF)=0,0
Exp/Cntr=0.3,0.1

Type RM Length L Ch R = 1 ,12015   ,366,366,366
XS GIS Cut Line= 3
2330826.03445919650800.8508292382331195.39800041650559.033897578
2331460.13139257650423.920770228
#Sta/Elev= 30
       0 2950.85    43.2 2942.72    53.3 2938.41    64.9 2938.21    74.3 2933.19
     103 2923.98   116.2 2918.22   165.1 2902.61   206.5 2885.35   220.9 2877.32
   236.8 2871.55   251.2 2869.54   285.5 2870.61   294.2 2868.45   303.8 2868.09
   320.7  2870.6   332.4 2871.77   393.7 2870.93   413.7 2868.13   423.3 2869.67
   451.3 2869.96   479.1 2873.83   509.7 2873.21     613 2878.38   639.9 2877.97
   672.4  2883.3   684.9 2888.59   705.1 2889.57     720 2894.81   738.7  2895.3
#Mann= 4, -1 ,  0
       0     0.1       0   285.5   0.045       0   320.7     0.1       0
  621.48    0.06       0
#XS Ineff= 2 , 0
                          485.25         2884.01
Permanent Ineff=
       F       F
Bank Sta=285.5,320.7
XS Rating Curve= 0 ,0
Exp/Cntr(USF)=0,0
Exp/Cntr=0.3,0.1

Type RM Length L Ch R = 1 ,11649   ,285.7,285.7,285.7
XS GIS Cut Line= 2
 2330874.9765044650900.483146453 2331496.9033816650508.581268716
#Sta/Elev= 30
       0 2969.07    43.9 2954.82    53.4 2949.88      70 2947.13    95.5 2933.89
   104.8 2930.76   124.3 2920.76   141.3 2914.91   204.7 2886.25   223.6 2876.89
   235.3 2873.17   247.3 2871.55   281.7 2870.62   313.5 2870.04   337.1 2871.83
   426.7  2870.7   445.8 2868.86   461.5 2867.33   469.5 2867.47   473.72868.963
   478.9 2870.03   516.8 2870.63   611.3 2874.57   639.7 2878.08   651.5 2880.25
   670.3 2885.72   687.7 2892.85   710.6 2894.22   724.8  2903.1   735.1 2906.02
#Mann= 4, -1 ,  0
       0     0.1       0   445.8   0.045       0   473.7     0.1       0
     680    0.06       0
Bank Sta=445.8,473.7
XS Rating Curve= 0 ,0
Exp/Cntr(USF)=0,0
Exp/Cntr=0.3,0.1

Type RM Length L Ch R = 1 ,11363   ,154.4,154.4,154.4
XS GIS Cut Line= 2
 2331030.4407013650988.9855280632331549.58417814650821.855189356
#Sta/Elev= 30
       0  2927.9       6 2923.84    18.6 2920.33    31.2 2910.58    35.4 2908.22
    43.8 2906.99    56.5 2899.52    64.9  2896.2    81.7 2887.23   102.7 2878.75
   112.5 2873.24   119.5 2870.45   141.1 2869.27   185.6 2869.84  197.86 2867.58
   203.5 2866.29   216.1  2866.2   223.7 2867.57   228.7 2868.42   270.8 2869.17
   279.2 2870.48   304.4 2869.32   354.8 2871.38   379.5 2870.33   443.1 2871.03
   451.5 2871.92   464.1 2875.99   506.7 2883.86   514.5 2884.25   545.4 2889.23
#Mann= 3, -1 ,  0
       0     0.1       0  197.86   0.045       0   223.7     0.1       0
Bank Sta=197.86,223.7
XS Rating Curve= 0 ,0
Exp/Cntr=0.3,0.1

Type RM Length L Ch R = 1 ,11209   ,89,89,89
XS GIS Cut Line= 4
2331020.22598724651165.5900358152331211.94509495651067.690916986
2331330.23986353651061.5722220592331613.73939514650888.209199132
#Sta/Elev= 30
       0 2921.42     9.7 2922.73    35.9 2931.93    49.3 2933.82    58.3  2933.3
    80.1 2924.88   107.7  2909.5   116.7  2906.1   141.6 2892.07   170.6 2879.25
   184.1 2870.07   202.4 2867.56   239.5 2868.66   263.9 2867.33   271.6    2866
   291.6 2867.33   299.6 2869.94   364.5 2868.23   500.1 2869.75   518.5  2873.4
   524.5 2875.54   533.3 2876.01   542.3 2878.73   579.8 2884.43   589.2 2887.38
   600.2  2887.8   632.2 2895.08   645.4 2899.81   659.5 2900.04     666    2903
#Mann= 3, -1 ,  0
       0     0.1       0   263.9   0.045       0   291.6     0.1       0
Bank Sta=263.9,291.6
XS Rating Curve= 0 ,0
Exp/Cntr(USF)=0,0
Exp/Cntr=0.3,0.1

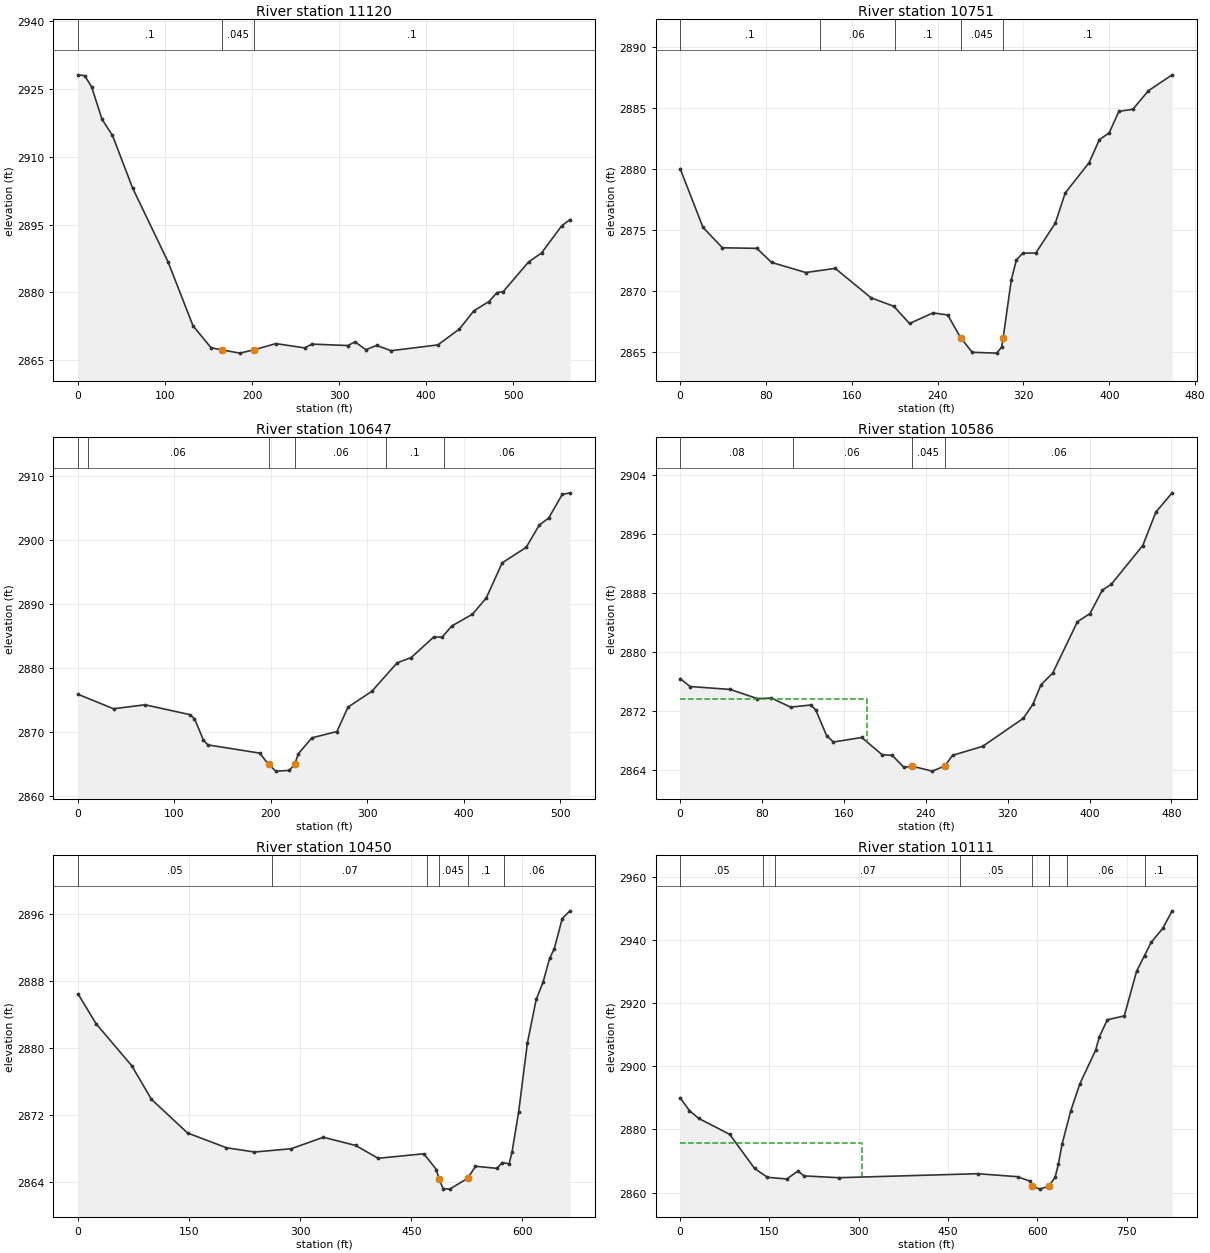
Type RM Length L Ch R = 1 ,11120   ,368.8,368.8,368.8
XS GIS Cut Line= 4
2331068.62755264651167.3301208392331183.50882038651172.294126235
2331522.47947455651082.9420291092331608.28585353651031.883687895
#Sta/Elev= 30
       0 2928.19     7.6 2928.01    15.6 2925.54    27.6 2918.34    39.6 2914.77
    62.7 2903.14   103.6 2886.72   132.2 2872.59   152.9 2867.76   165.3 2867.28
     186 2866.56   202.5 2867.31   227.4 2868.67   260.5 2867.72   268.7 2868.56
   310.1 2868.24   318.4 2869.05   330.8 2867.32   343.2 2868.27   359.7  2867.1
   413.5 2868.38   438.3  2871.9   454.9 2875.93   472.2 2877.98   481.5 2879.97
   488.5 2880.16   517.7 2886.73   532.7 2888.75   555.9 2894.77   565.4 2896.14
#Mann= 3, -1 ,  0
       0     0.1       0   165.3   0.045       0   202.5     0.1       0
Bank Sta=165.3,202.5
XS Rating Curve= 0 ,0
Exp/Cntr(USF)=0,0
Exp/Cntr=0.3,0.1

Type RM Length L Ch R = 1 ,10751   ,103.3,103.3,103.3
XS GIS Cut Line= 2
2331237.46264139651383.9395016152331639.61029029651163.567884603
#Sta/Elev= 30
       0    2880    21.3 2875.18    39.4 2873.51    71.5 2873.46    85.2 2872.31
   117.1 2871.48   144.5 2871.82   177.9 2869.41   199.2 2868.71   213.8  2867.3
   235.7 2868.17   249.4    2868  261.35 2866.15   272.2 2864.94     295 2864.87
   299.6 2865.35  301.13 2866.15   308.7 2870.89   313.4 2872.51   319.3 2873.07
   331.5 2873.08   349.7 2875.53   358.9    2878   381.2 2880.49   390.8 2882.38
   399.9 2882.93     409  2884.7   421.9 2884.86   436.4 2886.38   458.6 2887.69
#Mann= 5, -1 ,  0
       0     0.1       0     130    0.06       0     200     0.1       0
  261.35   0.045       0  301.13     0.1       0
Bank Sta=261.35,301.13
XS Rating Curve= 0 ,0
Exp/Cntr=0.3,0.1

Type RM Length L Ch R = 1 ,10647   ,61.5,61.5,61.5
XS GIS Cut Line= 4
2331344.41350956651480.2752038662331418.44810433651399.858316453
2331674.37803966651244.1303757492331772.02711724651217.962975877
#Sta/Elev= 30
       0 2875.84    36.8 2873.58    69.5  2874.2     116 2872.66   120.7 2872.04
     130 2868.69   134.7 2867.93   188.2 2866.65   197.52864.895     205 2863.83
     219 2863.94  224.55 2864.89   228.4 2866.55   242.4 2869.03   268.4 2870.02
   279.9 2873.84   304.6 2876.31   330.8 2880.76   345.4 2881.59   368.7 2884.79
   377.4 2884.77   387.6 2886.53   408.9 2888.36   423.2  2890.9   439.7 2896.39
   464.6 2898.81   478.1 2902.29   487.9 2903.39   501.9 2907.07     510 2907.33
#Mann= 6, -1 ,  0
       0     0.1       0      10    0.06       0   197.5   0.045       0
  224.55    0.06       0  319.31     0.1       0  379.31    0.06       0
Bank Sta=197.5,224.55
XS Rating Curve= 0 ,0
Exp/Cntr(USF)=0,0
Exp/Cntr=0.3,0.1

Type RM Length L Ch R = 1 ,10586   ,135.5,135.5,135.5
XS GIS Cut Line= 4
2331360.40359444651577.0503093082331442.03449325651462.526273454
2331623.27449725651333.0737158712331730.64977622651285.880152333
#Sta/Elev= 30
       0 2876.38     9.7 2875.31      49 2874.91    75.4 2873.67    89.2 2873.74
   107.9 2872.52   127.6  2872.8   132.5 2872.13   143.1 2868.66   149.8 2867.79
   177.4  2868.4   197.3 2866.07   207.2 2865.97   218.7 2864.35   226.3 2864.52
   246.4 2863.84  258.56 2864.54   266.2 2865.98   295.7 2867.21   335.3    2871
   344.8 2872.93   352.5 2875.53     364 2877.13   388.2  2884.1   400.4 2885.19
   412.5 2888.38   421.1 2889.14     452 2894.42   464.8 2898.95   480.7 2901.56
#Mann= 4, -1 ,  0
       0    0.08       0     110    0.06       0   226.3   0.045       0
  258.56    0.06       0
#XS Ineff= 2 , 0
          182.51 2873.67
Permanent Ineff=
       F       F
Bank Sta=226.3,258.56
XS Rating Curve= 0 ,0
Exp/Cntr(USF)=0,0
Exp/Cntr=0.3,0.1

Type RM Length L Ch R = 1 ,10450   ,339.9,339.9,339.9
XS GIS Cut Line= 4
2331436.71922258651910.2517403192331494.69728978651792.069648574
     2331660.938651413.0586187232331718.47657663651309.258922555
#Sta/Elev= 30
       0 2886.49    24.3 2882.94    72.5 2877.92    99.2  2873.9   147.9 2869.89
   200.3 2868.13   238.2 2867.62   287.7 2868.01   331.3 2869.38   374.8  2868.4
   405.2 2866.87   466.8 2867.41   483.9 2865.52   487.42864.342     493 2863.25
   501.7 2863.19     5262864.479   536.6 2865.92   565.5 2865.67   572.8 2866.36
     582 2866.21     586 2867.65   594.9 2872.44   606.6 2880.59   618.5 2885.82
   627.7 2887.86   636.8 2890.76   642.9 2891.86   653.7 2895.48   664.2  2896.4
#Mann= 6, -1 ,  0
       0    0.05       0  261.64    0.07       0  471.64     0.1       0
   487.4   0.045       0     526     0.1       0   575.5    0.06       0
Bank Sta=487.4,526
XS Rating Curve= 0 ,0
Exp/Cntr=0.3,0.1

Type RM Length L Ch R = 1 ,10111   ,182,182,182
XS GIS Cut Line= 2
2331440.18578506 651983.759425032332075.27666224651454.983320241
#Sta/Elev= 30
       0 2890.05    15.6 2885.97    31.2  2883.5    83.3 2878.44   124.9 2867.67
   146.7 2864.83   179.1 2864.31   197.8 2866.81   208.2 2865.28   266.6 2864.71
   499.7 2865.98   566.7 2865.03   586.9 2863.67   591.7 2862.09   603.8 2861.09
   619.4 2862.02   629.8 2864.84   635.2 2868.91   641.7 2875.49   655.8 2885.72
   671.4 2894.49   697.7 2905.05   704.2 2909.41   717.6 2914.77     746 2915.99
   766.7 2930.16     780 2935.13   791.1 2939.31   810.5  2943.7   826.4 2949.29
#Mann= 9, -1 ,  0
       0    0.05       0     140    0.08       0     160    0.07       0
     470    0.05       0   591.7   0.045       0   619.4    0.05       0
     620     0.1       0     650    0.06       0     780     0.1       0
#XS Ineff= 2 , 0
          305.82 2875.83
Permanent Ineff=
       F       F
Bank Sta=591.7,619.4
XS Rating Curve= 0 ,0
Exp/Cntr(USF)=0,0
Exp/Cntr=0.3,0.1

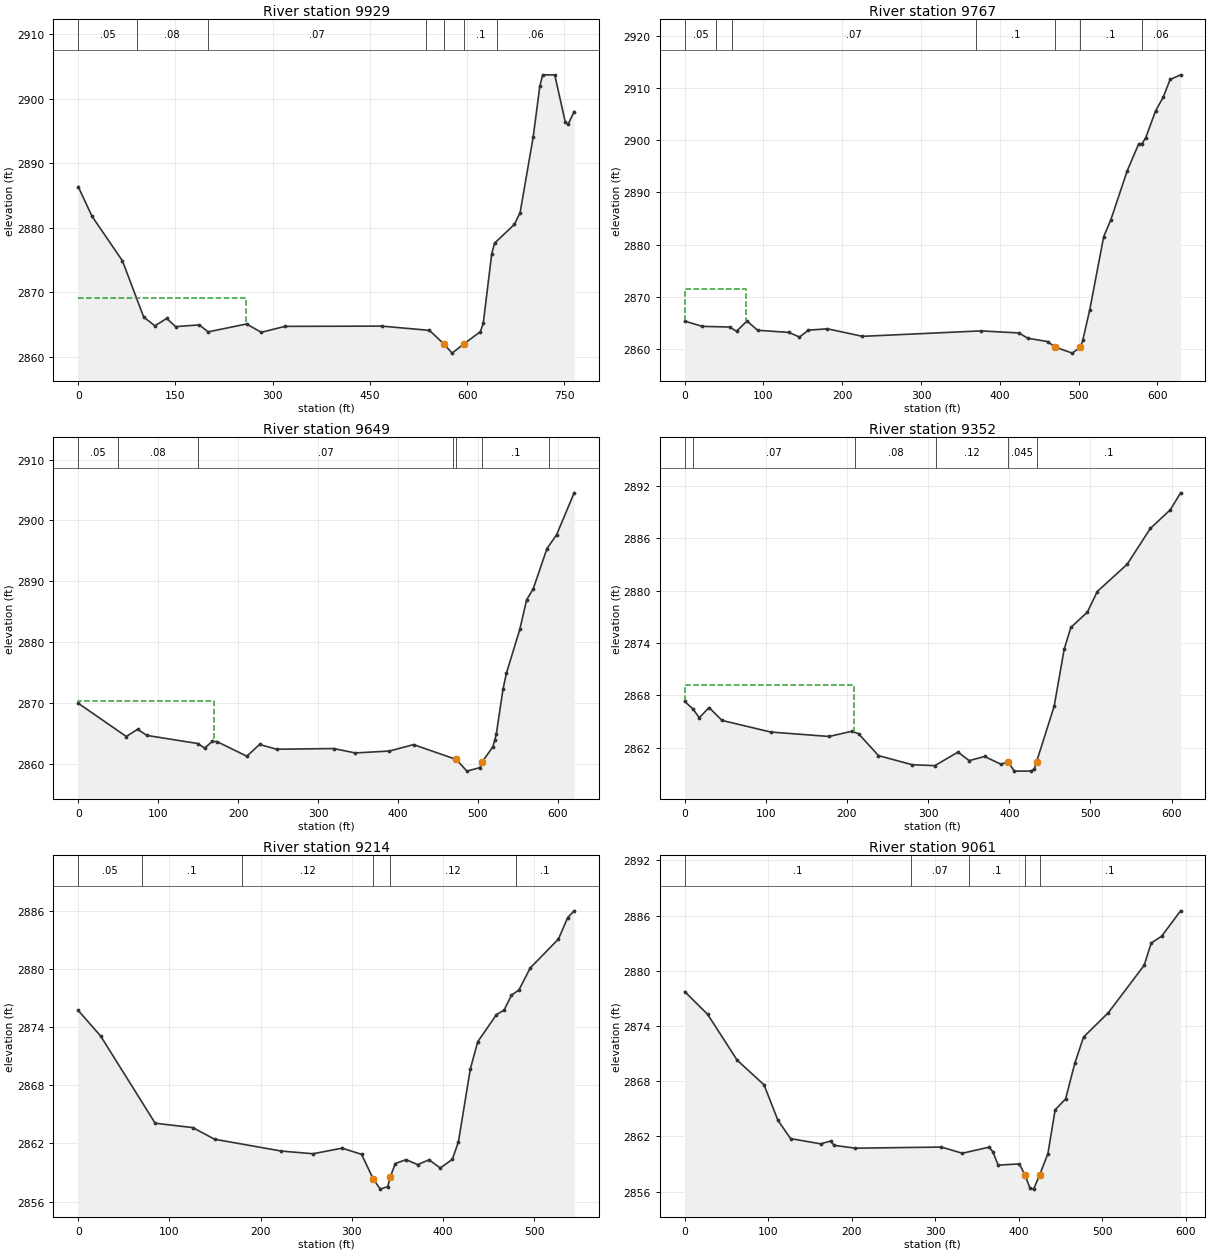
Type RM Length L Ch R = 1 ,9929    ,161.6,161.6,161.6
XS GIS Cut Line= 3
2331468.37970605652026.4936893662331842.22471161651822.069949269
2332152.58220293651686.195683805
#Sta/Elev= 30
       0 2886.37    21.4 2881.76    68.2 2874.87     101 2866.14   118.3 2864.79
   136.5 2865.93   150.2 2864.66   186.7 2864.93   200.4 2863.85   259.6 2865.07
   282.4 2863.78   318.9  2864.7   468.2 2864.74   541.7 2864.08   563.52862.009
   576.7 2860.55   595.3 2862.01   620.3 2863.88   624.7 2865.16   637.8 2875.98
   642.2 2877.61   672.7 2880.51   681.5 2882.32   701.6    2894     712 2901.98
   716.4 2903.72     735 2903.71   751.3 2896.36   755.7 2896.07   764.9 2898.02
#Mann= 7, -1 ,  0
       0    0.05       0      90    0.08       0     200    0.07       0
  536.09     0.1       0   563.5   0.045       0   595.3     0.1       0
  646.09    0.06       0
#XS Ineff= 2 , 0
          259.13 2869.17
Permanent Ineff=
       F       F
Bank Sta=563.5,595.3
XS Rating Curve= 0 ,0
Exp/Cntr=0.3,0.1

Type RM Length L Ch R = 1 ,9767    ,117.7,117.7,117.7
XS GIS Cut Line= 2
2331612.82549154652103.4467981892332180.14039392  651830.8204701
#Sta/Elev= 30
       0 2865.42    22.2 2864.41      57 2864.28    65.8 2863.47    79.1 2865.44
    92.5 2863.66   132.4 2863.25   145.7 2862.36   157.1 2863.68   181.2 2863.94
   225.6  2862.5   375.9 2863.54   423.9 2863.15   435.8 2862.13   460.8 2861.49
   469.7 2860.47   491.9 2859.29  502.26 2860.45   505.2 2861.72   514.1  2867.6
   531.8 2881.57   540.8 2884.76   561.7 2894.18   576.2 2899.29   580.6 2899.36
   585.1 2900.47   597.7 2905.62   607.3 2908.21   616.1  2911.6   629.4 2912.49
#Mann= 7, -1 ,  0
       0    0.05       0      40    0.08       0      60    0.07       0
     370     0.1       0   469.7   0.045       0  502.26     0.1       0
     580    0.06       0
#XS Ineff= 2 , 0
           78.35 2871.46
Permanent Ineff=
       F       F
Bank Sta=469.7,502.26
XS Rating Curve= 0 ,0
Exp/Cntr(USF)=0,0
Exp/Cntr=0.3,0.1

Type RM Length L Ch R = 1 ,9649    ,297,297,297
XS GIS Cut Line= 4
2331603.81642443652172.5698789172332042.64373758652007.445394669
2332082.24542868652004.9900156312332189.05022566651971.507972462
#Sta/Elev= 30
       0 2869.94    60.2 2864.47    74.3 2865.66    85.9 2864.65     150 2863.31
   158.2 2862.56   167.5 2863.66   173.7 2863.63     211 2861.23   226.9 2863.16
   248.3 2862.38   319.7 2862.49   346.6 2861.77   389.3 2862.08   419.6 2863.14
472.83352860.704   486.4 2858.78   502.5 2859.36505.50012860.301   518.9 2862.81
   521.3 2863.93   523.1 2864.87   531.5 2872.25   535.7 2874.86   552.5 2882.08
     561 2886.93   569.3 2888.76   586.5 2895.37   598.6 2897.65   620.5 2904.53
#Mann= 7, -1 ,  0
       0    0.05       0      50    0.08       0     150    0.07       0
  468.87     0.1       0472.8335   0.045       0505.5001     0.1       0
  588.54    0.06       0
#XS Ineff= 2 , 0
          169.76 2870.28
Permanent Ineff=
       F       F
Bank Sta=472.8335,505.5001
XS Rating Curve= 0 ,0
Exp/Cntr(USF)=0,0
Exp/Cntr=0.3,0.1

Type RM Length L Ch R = 1 ,9352    ,138.5,138.5,138.5
XS GIS Cut Line= 3
2331634.21025164652243.9565149312331834.25056195652243.940043083
2332236.69090776652327.773358873
#Sta/Elev= 30
       0 2867.29      10 2866.46      18 2865.42      30  2866.6      46 2865.12
     106 2863.79     178 2863.28   206.1 2863.88   214.3 2863.59   238.8 2861.09
   280.5 2860.04   308.2 2859.94   336.8 2861.49   350.6 2860.51   369.5 2860.99
     390 2860.09   398.1  2860.4   406.3 2859.31   426.7 2859.32   430.8 2859.56
   433.7 2860.41   455.3 2866.75   467.6 2873.27   475.8 2875.77   496.2 2877.53
   508.4 2879.89   545.2 2883.01   573.8 2887.12   598.4 2889.26   611.1  2891.2
#Mann= 6, -1 ,  0
       0    0.05       0      10    0.07       0  210.04    0.08       0
  310.04    0.12       0   398.1   0.045       0   433.7     0.1       0
#XS Ineff= 2 , 0
          209.11 2869.22
Permanent Ineff=
       F       F
Bank Sta=398.1,433.7
XS Rating Curve= 0 ,0
Exp/Cntr=0.3,0.1

Type RM Length L Ch R = 1 ,9214    ,152.8,152.8,152.8
XS GIS Cut Line= 2
2331673.83765201652492.416189054 2332203.0893195652367.313146904
#Sta/Elev= 30
       0 2875.73    24.6 2873.09    84.4 2864.09   125.7 2863.64   149.5 2862.44
   222.7 2861.22   257.5 2860.94   289.4 2861.52   310.7 2860.88323.50522858.335
   331.2 2857.29   339.4 2857.55342.17142858.538   347.7 2859.93   359.4 2860.33
   372.3 2859.82   384.7 2860.32     397 2859.47   410.2 2860.36   416.9 2862.17
   429.9 2869.67   438.1  2872.5   458.6  2875.3   466.9 2875.76   475.1  2877.3
   483.3 2877.85   495.6 2880.11   526.6  2883.1   536.7 2885.31   543.8 2886.01
#Mann= 6, -1 ,  0
       0    0.05       0      70     0.1       0     180    0.12       0
323.5052   0.045       0342.1714    0.12       0     480     0.1       0
Bank Sta=323.5052,342.1714
XS Rating Curve= 0 ,0
Exp/Cntr(USF)=0,0
Exp/Cntr=0.3,0.1

Type RM Length L Ch R = 1 ,9061    ,199.9,199.9,199.9
XS GIS Cut Line= 3
2331677.45362757652616.643420605 2331858.1889582652625.526106224
2332245.16301134652480.721779358
#Sta/Elev= 30
       0 2877.74    27.6 2875.25    62.8 2870.29      95 2867.61   111.8 2863.73
   126.9 2861.76   162.9 2861.19   174.9  2861.5   178.9 2861.03   204.4 2860.72
   307.5 2860.84   332.6 2860.17   364.6 2860.83   369.2 2860.33   375.5 2858.88
   400.9 2859.01  407.54 2857.82   413.7 2856.37     418 2856.27   425.2 2857.81
   435.1 2860.12   443.8 2864.89   456.3 2866.07   467.3 2869.93   477.8 2872.79
   507.7 2875.46   550.4 2880.59   558.9 2883.01   571.3 2883.75   594.1 2886.51
#Mann= 5, -1 ,  0
       0     0.1       0  270.95    0.07       0  340.95     0.1       0
  407.54   0.045       0   425.2     0.1       0
#XS Ineff= 2 , 0
                          532.97         2865.77
Permanent Ineff=
       F       F
Bank Sta=407.54,425.2
XS Rating Curve= 0 ,0
Exp/Cntr=0.3,0.1

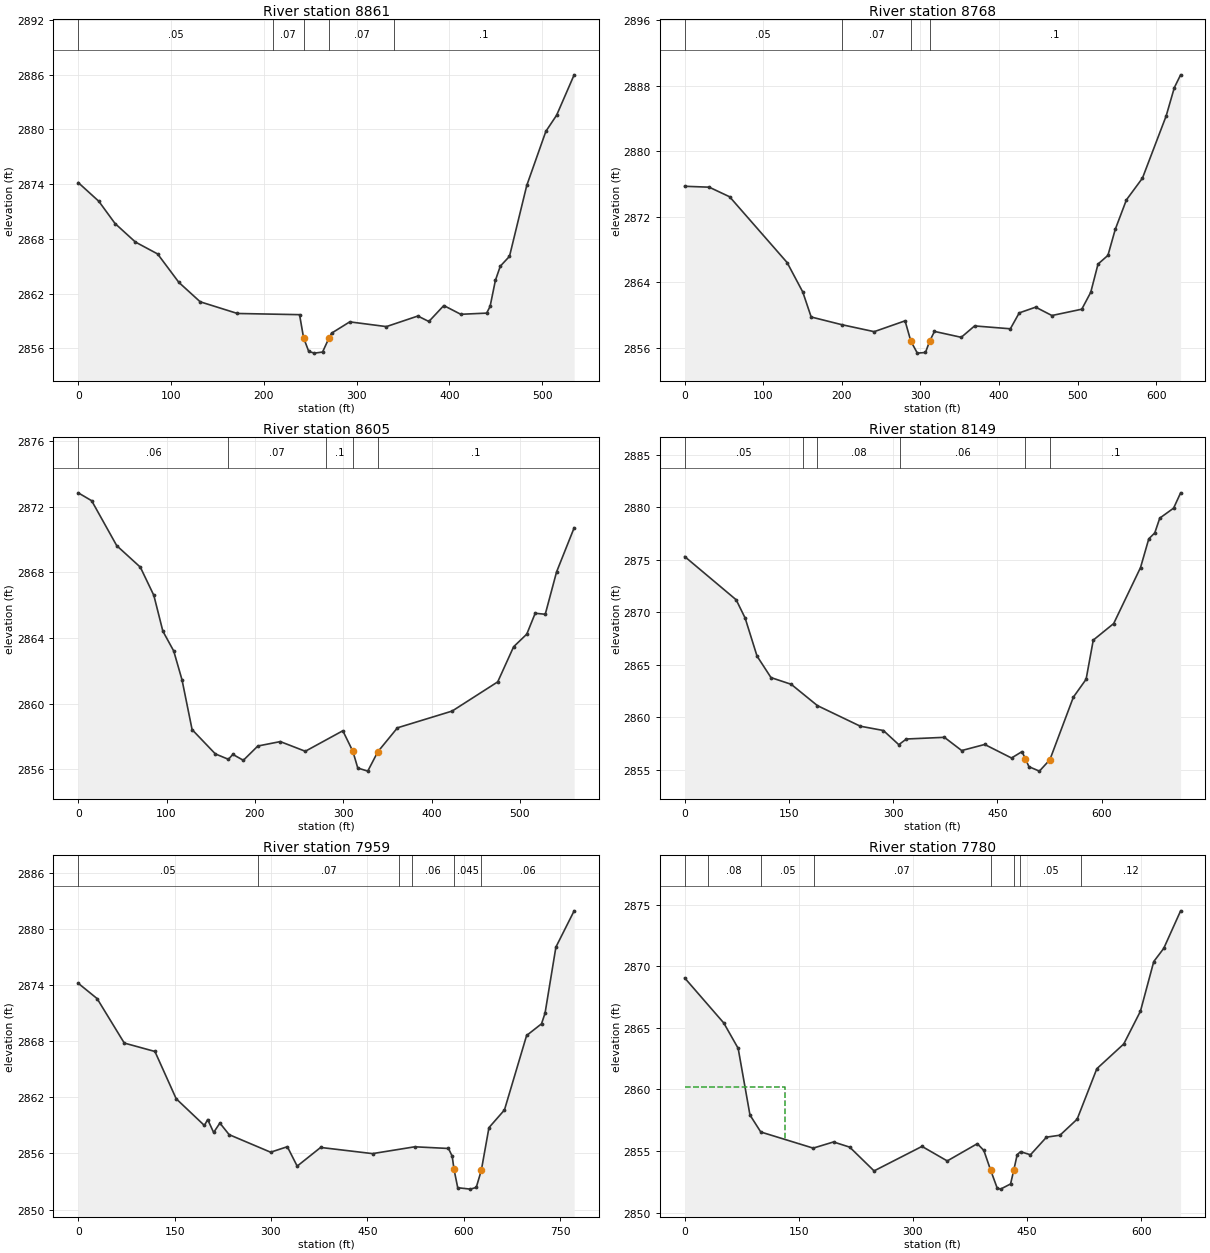
Type RM Length L Ch R = 1 ,8861    ,92.8,92.8,92.8
XS GIS Cut Line= 2
2331866.10541633652874.5247684092332300.84604417652563.481059546
#Sta/Elev= 30
       0 2874.17    22.2 2872.12    39.7 2869.68    61.6 2867.65    85.6 2866.34
   108.5 2863.22   131.5 2861.09   171.6 2859.81   238.6 2859.68   242.9 2857.16
   248.5 2855.64   254.7 2855.46   263.4 2855.58   270.4 2857.13   273.1 2857.65
   292.7 2858.89   332.2 2858.37   366.1 2859.53     378 2858.93   394.1 2860.68
   412.4 2859.72   440.3 2859.85     444 2860.59   449.7 2863.44     455    2865
   464.9 2866.08   483.5 2873.85   504.1 2879.79   515.7 2881.56   534.6 2885.99
#Mann= 5, -1 ,  0
       0    0.05       0     210    0.07       0   242.9   0.045       0
   270.4    0.07       0     340     0.1       0
Bank Sta=242.9,270.4
XS Rating Curve= 0 ,0
Exp/Cntr(USF)=0,0
Exp/Cntr=0.3,0.1

Type RM Length L Ch R = 1 ,8768    ,163.7,163.7,163.7
XS GIS Cut Line= 2
2331896.12954377652992.716193559 2332382.3022747652590.182345119
#Sta/Elev= 30
       0 2875.72    31.2 2875.61    57.2 2874.44   130.4 2866.41   150.3 2862.82
     161 2859.77     200 2858.83   241.2 2857.98   280.5  2859.3   287.8 2856.83
   296.1 2855.36   306.5 2855.44   311.6 2856.78   317.9 2858.01     352 2857.29
     369 2858.68   414.5 2858.33   425.8 2860.27   446.7 2860.97   467.4 2859.95
   505.4 2860.72   516.8 2862.78   526.1 2866.23   538.7 2867.29     548 2870.46
   562.2 2874.06   582.6 2876.71   612.8  2884.3   623.2 2887.76   631.2 2889.32
#Mann= 4, -1 ,  0
       0    0.05       0     200    0.07       0   287.8   0.045       0
   311.6     0.1       0
Bank Sta=287.8,311.6
XS Rating Curve= 0 ,0
Exp/Cntr(USF)=0,0
Exp/Cntr=0.3,0.1

Type RM Length L Ch R = 1 ,8605    ,455.9,455.9,455.9
XS GIS Cut Line= 2
 2332035.3507395653079.8427390242332434.31858972 652684.99785609
#Sta/Elev= 30
       0 2872.84    15.2 2872.36    43.6 2869.62    70.3 2868.31    85.6 2866.59
    95.8 2864.41   108.1  2863.2   117.5 2861.44   128.9 2858.41   155.2 2856.93
     170  2856.6     175  2856.9   186.9 2856.54   203.3 2857.41   228.7 2857.68
     257 2857.09   299.5 2858.34   310.9 2857.08   316.4 2856.07   327.7 2855.88
   339.1 2857.06   361.3 2858.52   423.2 2859.54   474.8 2861.32   492.8 2863.46
   507.7 2864.23   517.2  2865.5   528.6 2865.44   541.4 2868.02   561.3 2870.71
#Mann= 5, -1 ,  0
       0    0.06       0     170    0.07       0     280     0.1       0
   310.9   0.045       0   339.1     0.1       0
Bank Sta=310.9,339.1
XS Rating Curve= 0 ,0
Exp/Cntr(USF)=0,0
Exp/Cntr=0.3,0.1

Type RM Length L Ch R = 1 ,8149    ,189.2,189.2,189.2
XS GIS Cut Line= 2
2332085.12334369 653261.67095397 2332654.1871517652831.096125784
#Sta/Elev= 30
       0 2875.29    74.1 2871.17      87 2869.43   104.1 2865.81   124.2 2863.76
   153.3 2863.12     191 2861.09   252.7 2859.13   285.9 2858.72   308.1 2857.37
     319 2857.91   373.7 2858.07   398.6 2856.81   431.7 2857.39   470.3  2856.1
   485.4 2856.71   490.4 2855.99   495.4 2855.27   510.4 2854.85   525.5 2855.94
   559.3  2861.9   577.6  2863.6   587.9 2867.33   617.3 2868.91   655.9 2874.24
   667.8 2876.98   676.4 2877.54   683.6 2878.95   703.5  2879.9   713.6 2881.36
#Mann= 6, -1 ,  0
       0    0.05       0     170    0.06       0     190    0.08       0
     310    0.06       0   490.4   0.045       0   525.5     0.1       0
Bank Sta=490.4,525.5
XS Rating Curve= 0 ,0
Exp/Cntr(USF)=0,0
Exp/Cntr=0.3,0.1

Type RM Length L Ch R = 1 ,7959    ,179.7,179.7,179.7
XS GIS Cut Line= 2
     2332101.005       653437.522332742.37458691653007.957984777
#Sta/Elev= 30
       0 2874.21    29.4 2872.57    71.7 2867.81   119.4 2866.91   152.5 2861.85
   196.4 2858.99   201.5 2859.63   210.8 2858.24   220.5 2859.25   234.9 2858.01
   299.5 2856.13   325.5 2856.72   340.8 2854.64   377.3 2856.64   458.1 2855.98
   523.8 2856.71   576.3 2856.53   582.1  2855.7   584.9  2854.3   590.7 2852.33
   610.4 2852.18   619.5 2852.36   627.42854.188   639.3 2858.76   663.4 2860.65
   697.9 2868.62   721.1 2869.87   726.6 2871.01   743.5 2878.08   771.9 2881.96
#Mann= 6, -1 ,  0
       0    0.05       0     280    0.07       0     500    0.08       0
     520    0.06       0   584.9   0.045       0   627.4    0.06       0
Bank Sta=584.9,627.4
XS Rating Curve= 0 ,0
Exp/Cntr=0.3,0.1

Type RM Length L Ch R = 1 ,7780    ,237.3,237.3,237.3
XS GIS Cut Line= 3
2332309.64292546653519.7299198792332550.25004192653307.100375097
2332852.40781609653172.808031023
#Sta/Elev= 30
       0 2869.05    51.4 2865.39    70.3 2863.33    85.8 2857.92     100 2856.54
   168.9 2855.23   195.6 2855.73   216.9 2855.31   248.9 2853.38   311.9 2855.37
   345.1 2854.19   384.6 2855.59   393.2 2855.04     402 2853.46   410.7 2851.99
   415.1  2851.9   428.3 2852.32   432.6 2853.46     437  2854.7   441.4 2854.94
   454.5 2854.69   475.5 2856.12   493.3 2856.28   515.8 2857.58   541.7 2861.68
   577.1 2863.69     599 2866.35   616.5 2870.38   629.6 2871.45   651.8  2874.5
#Mann= 8, -1 ,  0
       0    0.05       0      30    0.08       0     100    0.05       0
     170    0.07       0     402   0.045       0   432.6    0.12       0
   441.1    0.05       0   521.1    0.12       0
#XS Ineff= 2 , 0
          131.33 2860.16
Permanent Ineff=
       F       F
Bank Sta=402,432.6
XS Rating Curve= 0 ,0
Exp/Cntr(USF)=0,0
Exp/Cntr=0.3,0.1

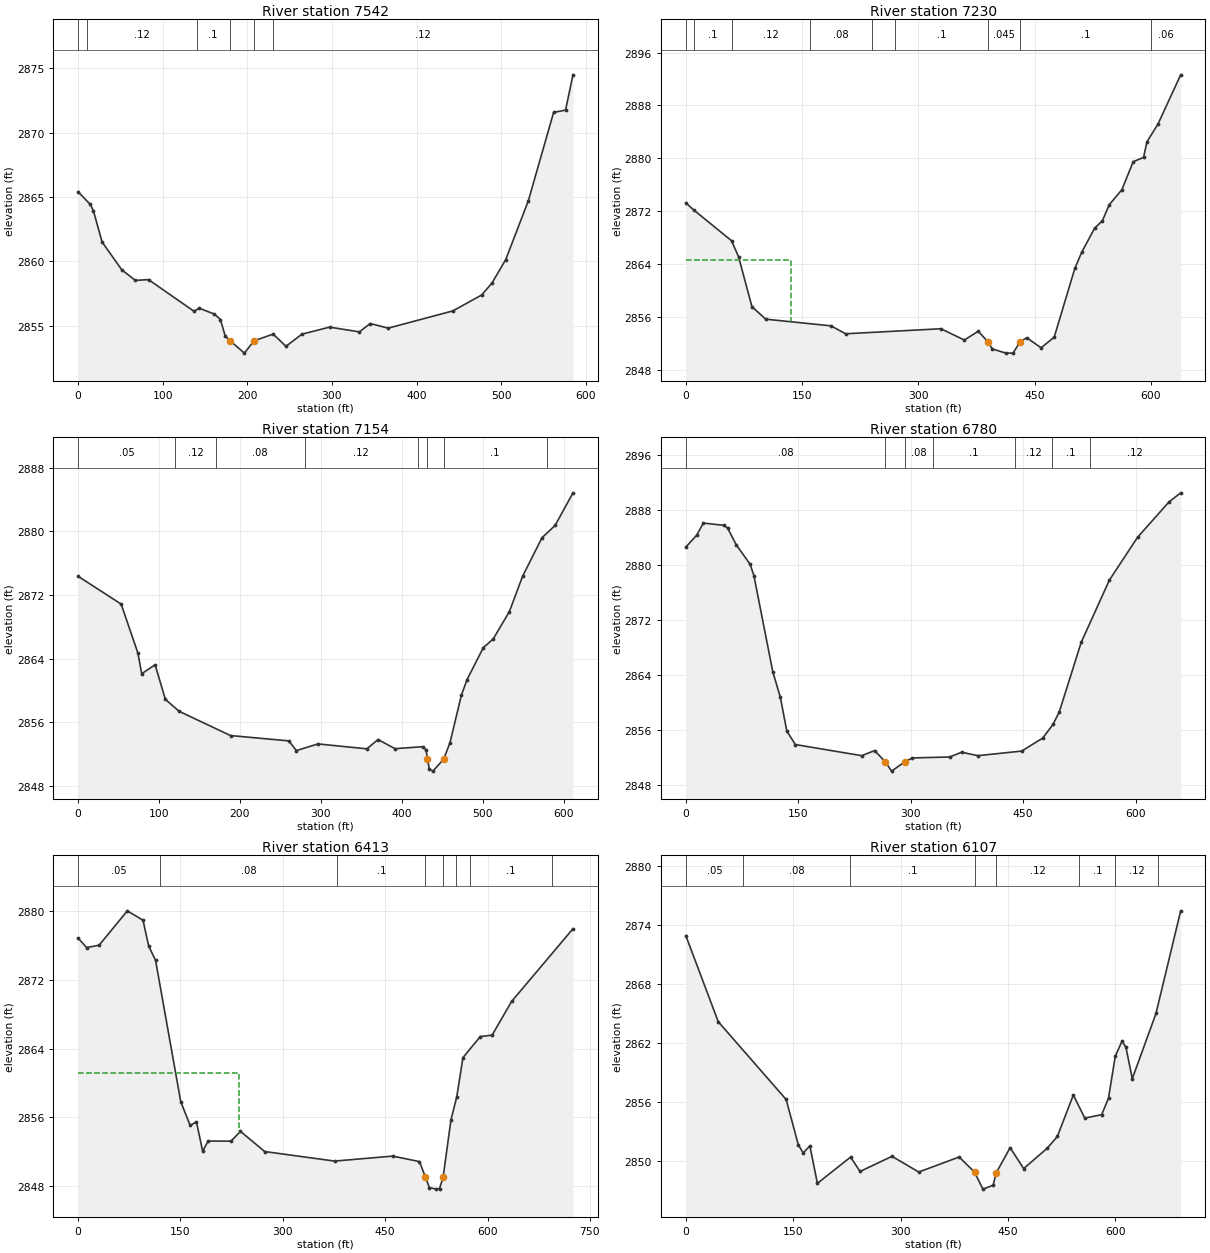
Type RM Length L Ch R = 1 ,7542    ,312.9,312.9,312.9
XS GIS Cut Line= 2
2332425.54189446653603.9298624572332863.72776619653216.418370537
#Sta/Elev= 30
       0  2865.4    14.2 2864.43      18 2863.94    28.3  2861.5    51.6 2859.34
    67.6 2858.52    83.2 2858.58     137 2856.12     143 2856.36   161.1  2855.9
   168.2 2855.48   173.8 2854.21   179.3 2853.85   196.5 2852.87   207.8 2853.82
   230.5 2854.35   245.7  2853.4   264.5 2854.34   297.2 2854.89   332.5 2854.52
   345.3 2855.17   366.5 2854.81     443 2856.15   477.1 2857.39   489.4 2858.33
   505.5 2860.14   532.2  2864.7   562.1 2871.57   576.2 2871.75     585 2874.49
#Mann= 6, -1 ,  0
       0     0.1       0      10    0.12       0     140     0.1       0
   179.3   0.045       0   207.8     0.1       0     230    0.12       0
Bank Sta=179.3,207.8
XS Rating Curve= 0 ,0
Exp/Cntr=0.3,0.1

Type RM Length L Ch R = 1 ,7230    ,75.4,75.4,75.4
XS GIS Cut Line= 2
2332483.10386989653754.7415220082333059.44184653653480.561319525
#Sta/Elev= 30
       0 2873.25      10 2872.19      59 2867.51      68 2865.08    85.3 2857.52
   103.1 2855.64   187.2 2854.63   206.1 2853.43     329 2854.19   359.2 2852.48
   377.2 2853.82   389.2 2852.26   395.4 2851.12     413  2850.5     422 2850.51
   431.2 2852.22   439.7 2852.83   458.2 2851.31   475.1 2852.92   501.7 2863.32
   510.6 2865.78   527.3 2869.42   537.2 2870.53     546 2872.95   562.3 2875.23
     577 2879.48   590.3 2880.12   594.7 2882.49   608.9 2885.17   638.2 2892.63
#Mann= 9, -1 ,  0
       0    0.05       0      10     0.1       0      60    0.12       0
     160    0.08       0     240    0.12       0     270     0.1       0
   389.2   0.045       0   431.2     0.1       0     600    0.06       0
#XS Ineff= 2 , 0
          136.12 2864.57
Permanent Ineff=
       F       F
Bank Sta=389.2,431.2
XS Rating Curve= 0 ,0
Exp/Cntr(USF)=0,0
Exp/Cntr=0.3,0.1

Type RM Length L Ch R = 1 ,7154    ,373.7,373.7,373.7
XS GIS Cut Line= 3
 2332470.4328164653791.1112812912332922.62255808653632.793939318
 2333054.1224153653616.833185293
#Sta/Elev= 30
       0 2874.33    53.1 2870.84    73.9 2864.67    78.5 2862.09    95.1 2863.21
   107.8 2858.87   124.7 2857.37   188.3 2854.32   260.4 2853.65   269.7 2852.43
   296.4 2853.27   356.9 2852.65   370.6 2853.82   391.7 2852.67   425.7 2852.92
   429.9 2852.54  431.75 2851.37   434.1 2850.08   438.4 2849.85   451.8 2851.36
   459.6 2853.43   473.7 2859.41   480.7 2861.36   500.8 2865.37   512.9 2866.44
     533  2869.9   549.2 2874.31   573.3 2879.18   589.5 2880.72   611.6 2884.82
#Mann= 8, -1 ,  0
       0    0.05       0     120    0.12       0     170    0.08       0
     280    0.12       0     420     0.1       0  431.75   0.045       0
   451.8     0.1       0   579.1    0.06       0
Bank Sta=431.75,451.8
XS Rating Curve= 0 ,0
Exp/Cntr=0.3,0.1

Type RM Length L Ch R = 1 ,6780    ,367.9,367.9,367.9
XS GIS Cut Line= 3
2332564.03974694654101.9099154022332841.42058362653889.795157938
2333139.19707006653800.054299011
#Sta/Elev= 30
       0 2882.57    14.4 2884.28    23.4 2886.06    50.5 2885.73    55.6 2885.36
    67.1 2882.92    85.8 2880.06    90.8 2878.41     116 2864.42   126.1 2860.69
   134.7 2855.79   146.1 2853.82   234.6  2852.2   251.9 2852.94     266 2851.32
   274.5 2849.95   292.2 2851.31   302.3 2851.87   352.1 2852.01   367.9  2852.7
   389.7  2852.2   448.2 2852.87   476.1 2854.76   489.9 2856.75   498.3 2858.59
   527.5  2868.7   565.1 2877.76   602.7 2883.99   644.5 2889.12   660.2 2890.46
#Mann= 7, -1 ,  0
       0    0.08       0     266   0.045       0   292.2    0.08       0
     330     0.1       0  439.19    0.12       0  489.19     0.1       0
  539.19    0.12       0
Bank Sta=266,292.2
XS Rating Curve= 0 ,0
Exp/Cntr(USF)=0,0
Exp/Cntr=0.3,0.1

Type RM Length L Ch R = 1 ,6413    ,305.2,305.2,305.2
XS GIS Cut Line= 3
2332629.55075033654331.5377212432332998.23461872654121.175238622
2333243.92228484653947.551001412
#Sta/Elev= 30
       0 2876.83    12.4 2875.74    30.7 2876.01    72.1 2880.01    95.1 2878.91
   103.3 2875.92   113.5 2874.24   150.4 2857.81   164.2 2855.05   173.4 2855.47
   182.5 2852.05   190.4 2853.24   224.1 2853.23   237.9 2854.37   273.4 2852.02
     376 2850.91   461.1 2851.49   500.3 2850.85   509.1 2849.03   514.8 2847.83
   524.8 2847.65   529.7 2847.72   534.9 2849.02   546.4 2855.68     555 2858.41
     564 2862.94   589.4 2865.39   606.7 2865.55   635.4 2869.48   725.3 2877.93
#Mann= 8, -1 ,  0
       0    0.05       0     120    0.08       0     380     0.1       0
   509.1   0.045       0   534.9     0.1       0  554.48    0.12       0
  574.48     0.1       0  694.48    0.06       0
#XS Ineff= 2 , 0
          236.07 2861.15
Permanent Ineff=
       F       F
Bank Sta=509.1,534.9
XS Rating Curve= 0 ,0
Exp/Cntr=0.3,0.1

Type RM Length L Ch R = 1 ,6107    ,478.8,478.8,478.8
XS GIS Cut Line= 2
2332857.94009625654563.8637662622333441.25567928  654192.6629407
#Sta/Elev= 30
       0 2872.89    45.3 2864.13   140.1 2856.22   157.1 2851.62   163.9 2850.77
   173.3 2851.49   183.8 2847.68   230.2 2850.35   243.4 2848.89   288.1 2850.43
   325.4 2848.83   381.9 2850.36   403.4 2848.82   415.1 2847.09   429.4 2847.49
   433.52848.722   453.1 2851.31     472 2849.18   505.2 2851.27   519.1 2852.45
   541.4 2856.67   557.4 2854.32   581.1 2854.67   590.6 2856.37     600 2860.61
   609.5 2862.17   614.9 2861.53   623.8 2858.33   656.9 2864.97   691.4 2875.42
#Mann= 8, -1 ,  0
       0    0.05       0      80    0.08       0     230     0.1       0
   403.4   0.045       0   433.5    0.12       0     550     0.1       0
     600    0.12       0     660    0.06       0
Bank Sta=403.4,433.5
XS Rating Curve= 0 ,0
Exp/Cntr(USF)=0,0
Exp/Cntr=0.3,0.1