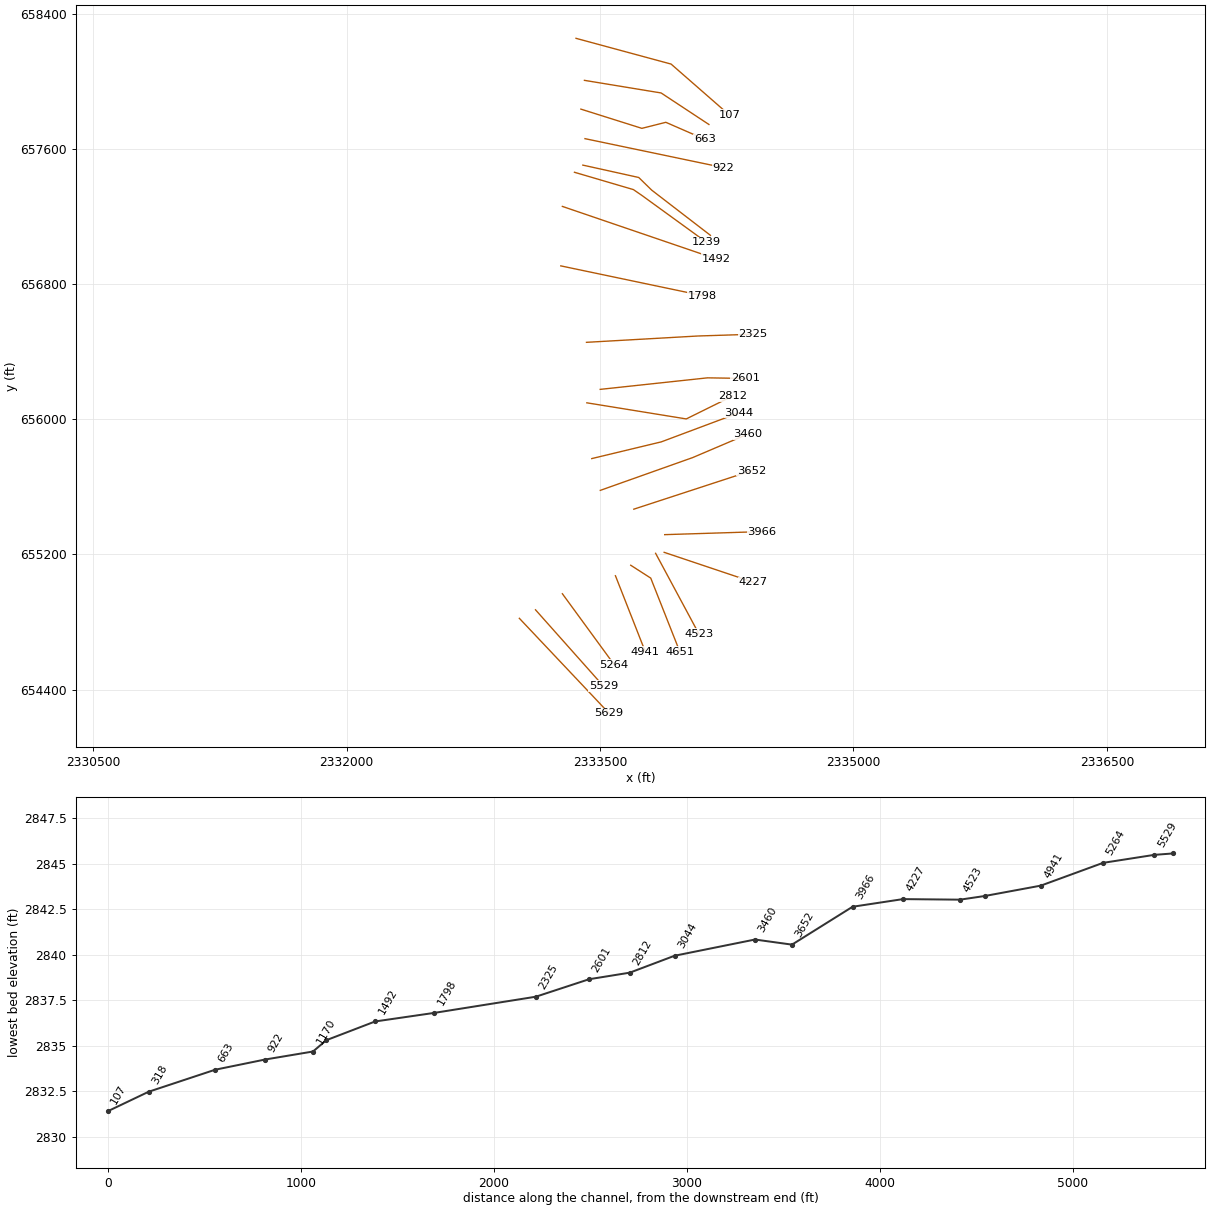
HEC-RAS study WFKGLADYFK.prj: WFKGLADYFK

--- WFKGLADYFK.g01 (geometry) --- (continued)

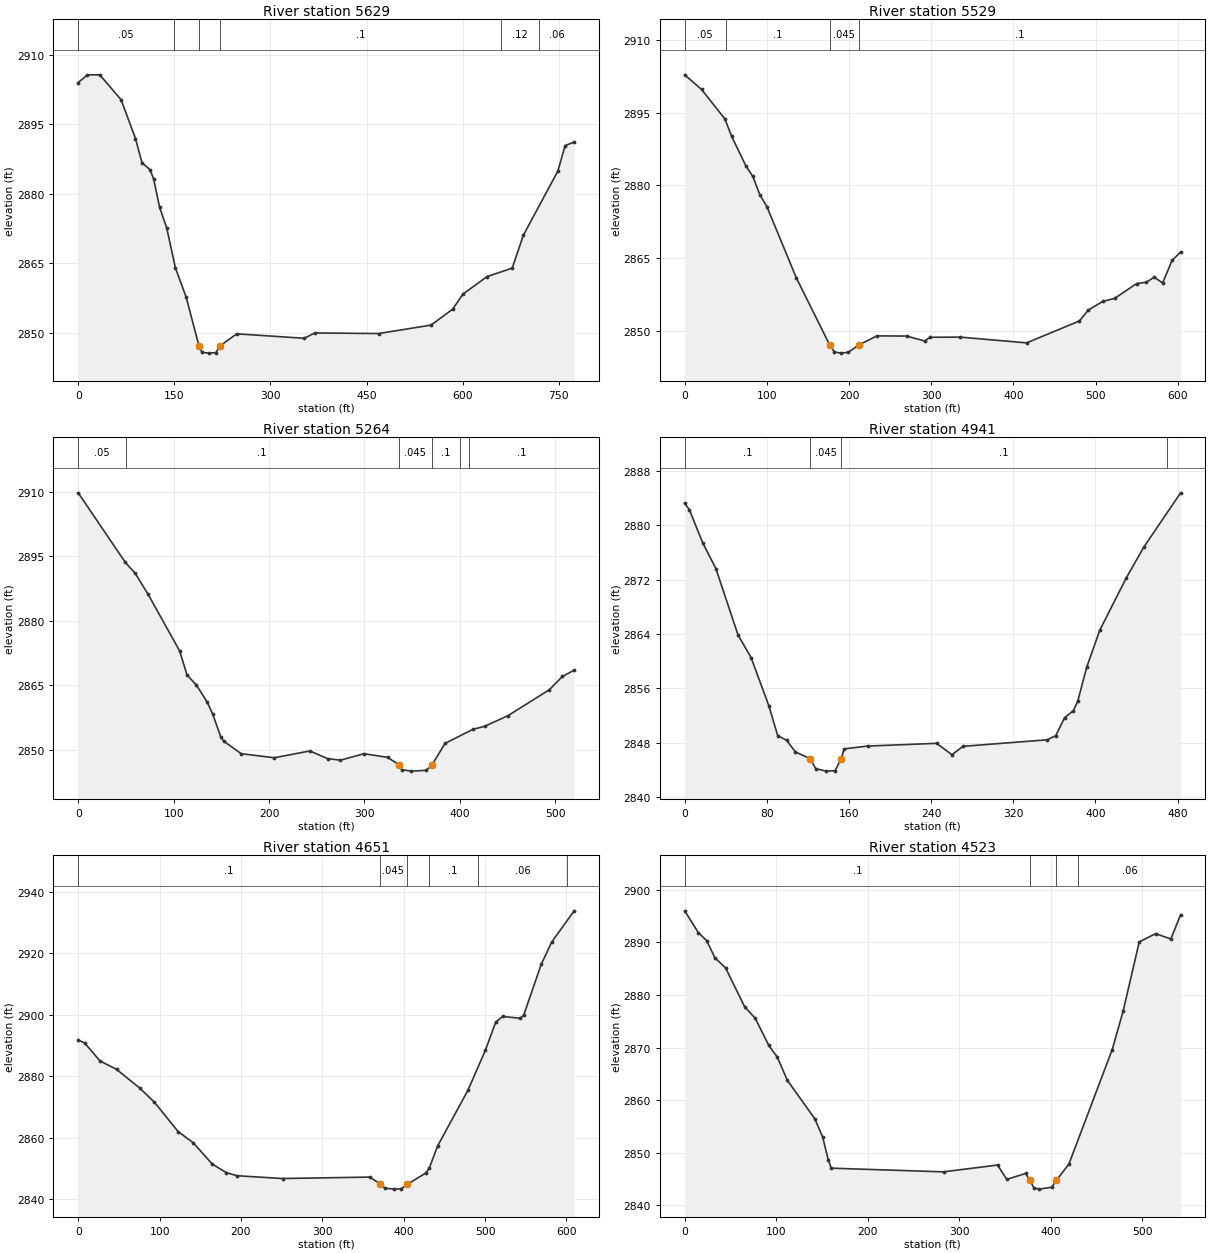
Type RM Length L Ch R = 1 ,5629    ,99.3,99.3,99.3
XS GIS Cut Line= 2
2333022.25797025654821.6043476252333553.83183221 654258.94429491
#Sta/Elev= 30
       0 2904.04    14.4 2905.69    33.6  2905.7    66.9 2900.33    89.4 2891.94
    99.6 2886.69     112 2885.22   117.7 2883.24   127.1 2877.04   138.2  2872.6
   151.6 2864.04   168.6 2857.63   188.4 2847.16   193.2 2845.73   204.2 2845.57
   215.2  2845.7   220.7 2847.07   247.4 2849.74   352.8 2848.78   369.3 2849.93
   468.8  2849.8   550.6 2851.62   584.5 2855.07   600.4 2858.31   638.3 2862.12
   677.4 2863.93   694.9 2871.07   748.7 2884.91     760 2890.41   774.1 2891.17
#Mann= 6, -1 ,  0
       0    0.05       0     150     0.1       0   188.4   0.045       0
   220.7     0.1       0     660    0.12       0     720    0.06       0
Bank Sta=188.4,220.7
XS Rating Curve= 0 ,0
Exp/Cntr(USF)=0,0
Exp/Cntr=0.3,0.1

Type RM Length L Ch R = 1 ,5529    ,265.8,265.8,265.8
XS GIS Cut Line= 2
2333117.89350761 654871.92941888 2333519.0929659654421.168475503
#Sta/Elev= 30
       0 2902.78    20.6 2899.77    48.9  2893.7    57.2 2890.09    74.4 2884.06
    82.9 2881.86    91.4 2878.11   100.1 2875.62   135.8    2861   176.4 2847.18
   182.1 2845.75   189.9 2845.49   199.1 2845.67  211.69 2847.15   233.9 2849.04
   269.9    2849   292.2 2847.98   298.2 2848.75     335 2848.79     416  2847.6
   480.3 2852.11   490.9 2854.34   508.8 2856.15   523.1 2856.75   549.9 2859.81
   561.7 2860.08   571.3 2861.13   581.5 2859.93     593 2864.57   603.4 2866.31
#Mann= 4, -1 ,  0
       0    0.05       0      50     0.1       0   176.4   0.045       0
  211.69     0.1       0
Bank Sta=176.4,211.69
XS Rating Curve= 0 ,0
Exp/Cntr=0.3,0.1

Type RM Length L Ch R = 1 ,5264    ,322.3,322.3,322.3
XS GIS Cut Line= 2
2333276.92396262654967.0229827452333583.52449437654547.384323168
#Sta/Elev= 30
       0 2909.75    49.4 2893.57    59.8 2891.01    73.3 2886.14   106.3 2872.99
     114 2867.41   123.9 2865.06   135.3 2861.05     141 2858.27   149.6 2852.88
   152.5 2852.01   170.7 2849.11   205.4 2848.16   242.8 2849.74   261.3 2847.96
   274.7 2847.59   299.5  2849.1   324.2 2848.25   335.7 2846.58   339.1  2845.4
   349.1 2845.05   364.9 2845.24  370.97 2846.58   384.4 2851.49   413.5 2854.76
   425.9 2855.47   450.2 2857.92   493.7 2863.97   507.4 2867.07   519.7 2868.51
#Mann= 6, -1 ,  0
       0    0.05       0      50     0.1       0   335.7   0.045       0
  370.97     0.1       0     400    0.06       0     410     0.1       0
Bank Sta=335.7,370.97
XS Rating Curve= 0 ,0
Exp/Cntr(USF)=0,0
Exp/Cntr=0.3,0.1

Type RM Length L Ch R = 1 ,4941    ,290.7,290.7,290.7
XS GIS Cut Line= 2
2333591.04127823655073.5030354722333767.72637097654623.938219333
#Sta/Elev= 30
       0 2883.24     4.6 2882.27    17.5 2877.42    30.4 2873.61    51.9 2863.87
    64.8 2860.46      82  2853.4    90.6 2849.03    99.2 2848.34   107.8 2846.63
   122.22845.637   127.6 2844.17   137.9  2843.8   146.5 2843.86   152.3 2845.62
   155.4 2847.08   178.1 2847.49   245.3 2847.89   260.3 2846.22   271.1 2847.45
     353 2848.41   361.4 2849.01     370 2851.66   378.6 2852.71   382.9 2854.14
   391.5 2859.07   404.3 2864.55   430.1 2872.25   447.3 2876.81     483 2884.76
#Mann= 4, -1 ,  0
       0     0.1       0   122.2   0.045       0   152.3     0.1       0
     470    0.06       0
Bank Sta=122.2,152.3
XS Rating Curve= 0 ,0
Exp/Cntr=0.3,0.1

Type RM Length L Ch R = 1 ,4651    ,128,128,128
XS GIS Cut Line= 3
2333681.57869148 655135.651554072333799.99698359655059.496899664
2333972.15225598654623.568785739
#Sta/Elev= 30
       0 2891.71     7.8  2890.8    26.9 2884.89    47.1  2882.2      76 2876.01
    93.7 2871.49   122.9 2861.91   141.3 2858.34   164.8 2851.36     182 2848.61
   195.1 2847.59   251.2 2846.68   358.3 2847.15370.57042845.015     377 2843.53
   388.4 2843.23     397 2843.34404.16962844.748   427.1 2848.45   431.4 2850.04
   441.8 2857.32   478.9 2875.36   500.4 2888.38   513.1 2897.56   521.7  2899.4
   543.2  2898.8   547.5 2899.82     569 2916.31   581.9 2923.59   609.5 2933.75
#Mann= 6, -1 ,  0
       0     0.1       0370.5704   0.045       0404.1696    0.06       0
  430.79     0.1       0  490.79    0.06       0  600.79     0.1       0
Bank Sta=370.5704,404.1696
XS Rating Curve= 0 ,0
Exp/Cntr(USF)=0,0
Exp/Cntr=0.3,0.1

Type RM Length L Ch R = 1 ,4523    ,295.4,295.4,295.4
XS GIS Cut Line= 2
2333828.79425099655206.306933916 2334085.2365154654729.047476566
#Sta/Elev= 30
       0 2896.03    14.9 2891.89      24 2890.35    33.1 2887.07    44.7 2885.16
    65.4  2877.8    77.2 2875.53    91.9 2870.39   101.2 2868.17   112.2 2863.74
   142.2 2856.42   150.8 2852.91   156.9 2848.57   160.2 2847.02   282.8 2846.32
   341.8 2847.62   351.9 2844.88   372.5 2846.02   377.2 2844.68   381.4  2843.3
   387.3 2843.03   400.9 2843.39  406.04  2844.7   419.8 2847.82   467.1 2869.62
   478.9 2876.86   496.6 2890.11   514.6 2891.69   531.1 2890.66   541.8 2895.29
#Mann= 4, -1 ,  0
       0     0.1       0   377.2   0.045       0  406.04     0.1       0
     430    0.06       0
Bank Sta=377.2,406.04
XS Rating Curve= 0 ,0
Exp/Cntr=0.3,0.1

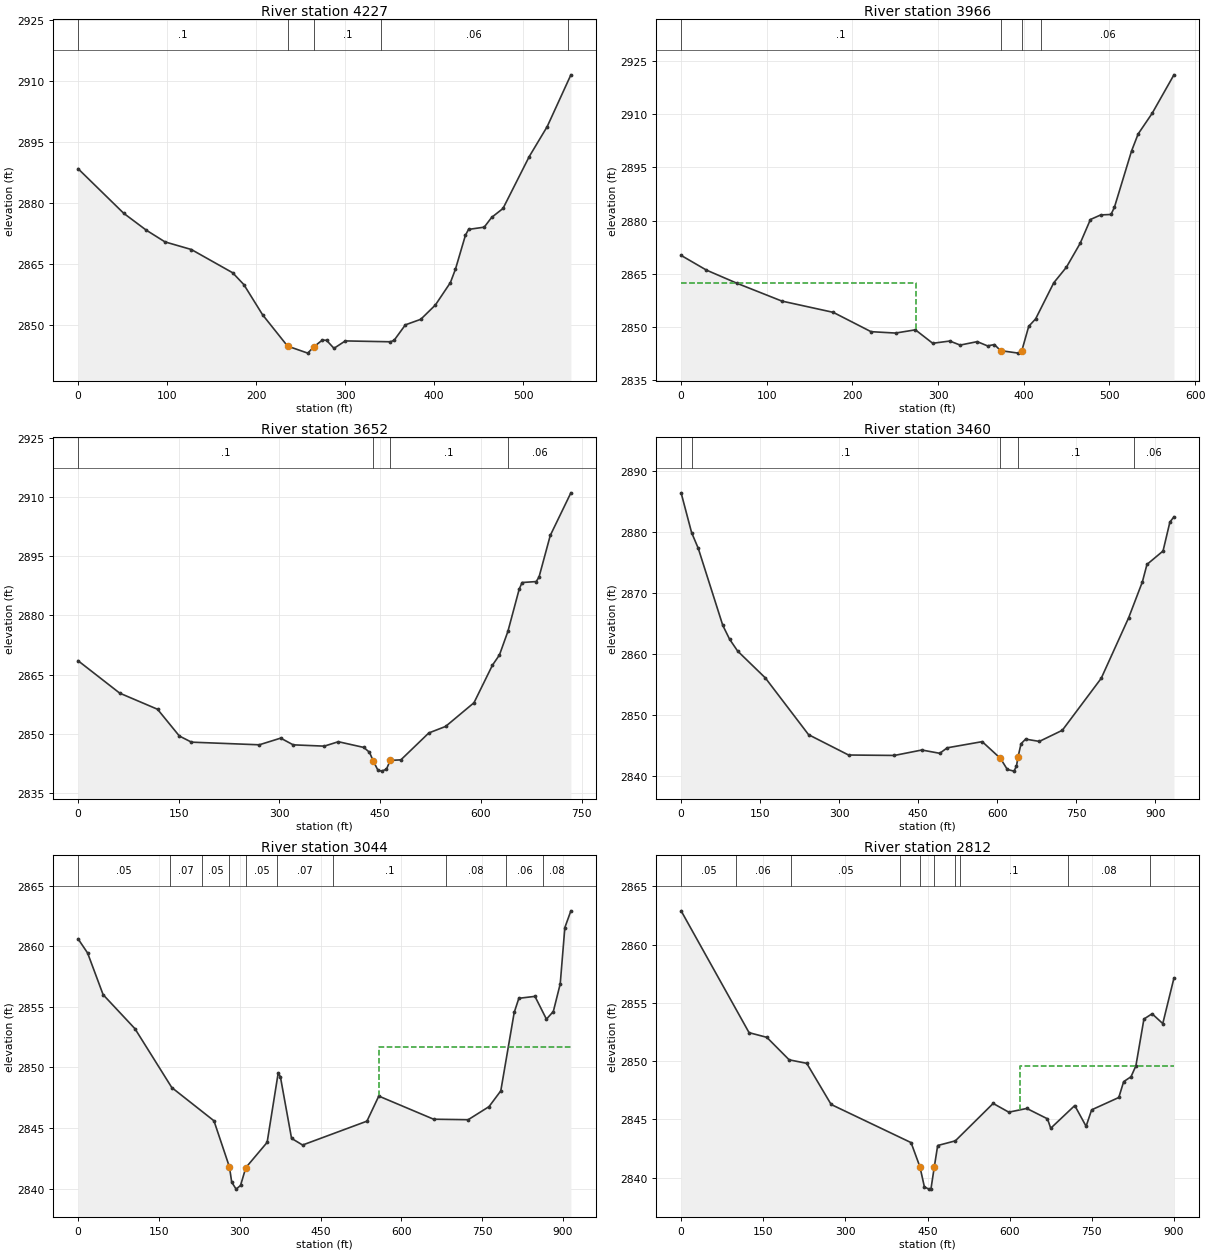
Type RM Length L Ch R = 1 ,4227    ,261.3,261.3,261.3
XS GIS Cut Line= 2
2333879.51886155655212.0718250382334404.53008323655035.916744077
#Sta/Elev= 30
       0 2888.38    51.3 2877.42    76.6 2873.28    97.7 2870.39   127.3 2868.52
   173.7 2862.81   186.3  2859.9   207.4 2852.47   235.4 2844.79   258.1 2843.06
     265 2844.62   274.5 2846.27   279.2 2846.21   287.6 2844.24   300.3 2846.06
   350.9 2845.85   355.1 2846.19   367.8 2850.01   385.1 2851.37   401.5 2854.88
   418.4 2860.39   424.1  2863.7   435.3 2872.03   438.8 2873.46   456.4 2874.01
   464.8 2876.42   477.5  2878.6     507 2891.36   527.2 2898.73   553.8 2911.44
#Mann= 5, -1 ,  0
       0     0.1       0   235.4   0.045       0     265     0.1       0
     340    0.06       0     550     0.1       0
Bank Sta=235.4,265
XS Rating Curve= 0 ,0
Exp/Cntr(USF)=0,0
Exp/Cntr=0.3,0.1

Type RM Length L Ch R = 1 ,3966    ,313.8,313.8,313.8
XS GIS Cut Line= 2
2333882.62133708655316.7495704992334457.66670414655334.775457749
#Sta/Elev= 30
       0  2870.2    29.6 2866.05    65.6  2862.3   117.6 2857.32   177.6 2854.14
   221.7 2848.69   250.3  2848.3   273.5 2849.21   293.7 2845.42   313.7 2846.05
   325.7 2844.91   345.7 2845.88   357.7 2844.68   365.7 2845.05     373 2843.34
   393.7 2842.64   397.8 2843.38   405.8 2850.21   413.8 2852.28     435 2862.47
   449.8 2866.88   465.8 2873.59   477.8 2880.32   489.8 2881.61   501.8 2881.74
   505.8 2883.76   525.8 2899.63   533.5 2904.44   549.8 2910.24   575.3 2921.12
#Mann= 4, -1 ,  0
       0     0.1       0     373   0.045       0   397.8     0.1       0
     420    0.06       0
#XS Ineff= 2 , 0
          273.71 2862.36
Permanent Ineff=
       F       F
Bank Sta=373,397.8
XS Rating Curve= 0 ,0
Exp/Cntr=0.3,0.1

Type RM Length L Ch R = 1 ,3652    ,191.8,191.8,191.8
XS GIS Cut Line= 2
2333699.61962161655467.4448821132334397.33190306655695.410281003
#Sta/Elev= 30
       0 2868.53    62.1 2860.31   118.4 2856.23   150.9 2849.45   168.9  2847.9
   269.9 2847.23   301.8 2848.92   320.4 2847.22   366.7 2846.89   387.7 2848.01
   425.6 2846.56     434 2845.33   439.5 2843.21   446.6 2840.79   452.2 2840.56
   459.3 2841.05   464.9 2843.27   480.8 2843.42   522.4 2850.23   547.4 2851.88
   589.7 2857.89   617.1 2867.38   627.6 2869.99   640.2 2875.97     657 2886.65
   661.3 2888.34   682.3 2888.58   686.5  2889.7   703.3 2900.27     734 2911.06
#Mann= 4, -1 ,  0
       0     0.1       0   439.5   0.045       0   464.9     0.1       0
     640    0.06       0
Bank Sta=439.5,464.9
XS Rating Curve= 0 ,0
Exp/Cntr(USF)=0,0
Exp/Cntr=0.3,0.1

Type RM Length L Ch R = 1 ,3460    ,416.5,416.5,416.5
XS GIS Cut Line= 3
2333501.44885758655578.8862860172334047.79966635655772.726237916
2334375.21638057655912.093522992
#Sta/Elev= 30
       0 2886.43    19.9 2879.92    32.6 2877.33    79.1 2864.72      92 2862.46
   107.3 2860.51   159.9 2856.11     242 2846.81   317.9 2843.48   404.9 2843.41
     457  2844.3     491 2843.76   505.2 2844.66   571.6 2845.67   606.2 2842.93
   619.3 2841.11   631.9 2840.84   636.6 2841.63   639.7 2843.19   645.3 2845.32
     654 2846.08   680.1 2845.71   723.7 2847.53   797.5 2856.04   849.7 2865.98
   875.7 2871.85   884.4  2874.7   914.9  2876.9   927.9 2881.64   935.6 2882.49
#Mann= 5, -1 ,  0
       0    0.05       0      20     0.1       0   606.2   0.045       0
   639.7     0.1       0  859.72    0.06       0
Bank Sta=606.2,639.7
XS Rating Curve= 0 ,0
Exp/Cntr=0.3,0.1

Type RM Length L Ch R = 1 ,3044    ,232.4,232.4,232.4
XS GIS Cut Line= 3
2333451.00127737  655766.9339041 2333862.6263714655865.933458881
2334322.66158256656038.163390156
#Sta/Elev= 30
       0 2860.61    17.7 2859.44    46.5    2856   105.6 2853.19     174 2848.33
   252.2 2845.59     281 2841.77   285.1 2840.53   293.3 2839.95   301.5 2840.25
   311.3 2841.72   350.9 2843.81   371.5 2849.56   375.6  2849.2   396.2 2844.14
   416.7 2843.59   536.1 2845.56   558.1 2847.63   659.9 2845.72     724 2845.68
   762.7 2846.76   784.5 2848.06   809.4 2854.53     818  2855.7   847.9 2855.86
   869.2 2853.98     882 2854.61   894.8 2856.89   903.4 2861.54   914.6 2862.92
#Mann= 10, -1 ,  0
       0    0.05       0     170    0.07       0     230    0.05       0
     281   0.045       0   311.3    0.05       0     370    0.07       0
  473.36     0.1       0  683.36    0.08       0  793.36    0.06       0
  863.36    0.08       0
#XS Ineff= 2 , 0
                           559.2          2851.7
Permanent Ineff=
       F       F
Bank Sta=281,311.3
XS Rating Curve= 0 ,0
Exp/Cntr(USF)=0,0
Exp/Cntr=0.3,0.1

Type RM Length L Ch R = 1 ,2812    ,210.7,210.7,210.7
XS GIS Cut Line= 3
2333421.72528786656097.0347601782334010.23253103656001.644206301
2334282.46001076656136.265933307
#Sta/Elev= 30
       0 2862.89   124.1 2852.44   156.5 2852.04   197.3 2850.11   229.4 2849.81
     274 2846.28   419.9 2843.01   436.1 2840.93   444.2 2839.22   452.3 2839.02
   456.3 2839.06   462.3 2840.92   468.5 2842.76   500.7 2843.16   569.8 2846.37
   598.4 2845.62   631.2 2845.94     669 2845.05   674.9 2844.24   718.8 2846.19
   739.5 2844.41   749.6 2845.82   799.2 2846.88   808.1 2848.24   821.5 2848.66
   830.4 2849.59   845.1 2853.61     860 2854.06   879.5 2853.22   899.9 2857.12
#Mann= 10, -1 ,  0
       0    0.05       0     100    0.06       0     200    0.05       0
     400    0.08       0   436.1   0.045       0   462.3    0.08       0
     500    0.05       0     510     0.1       0  706.19    0.08       0
  856.19    0.07       0
#XS Ineff= 2 , 0
                          618.43         2849.62
Permanent Ineff=
       F       F
Bank Sta=436.1,462.3
XS Rating Curve= 0 ,0
Exp/Cntr=0.3,0.1

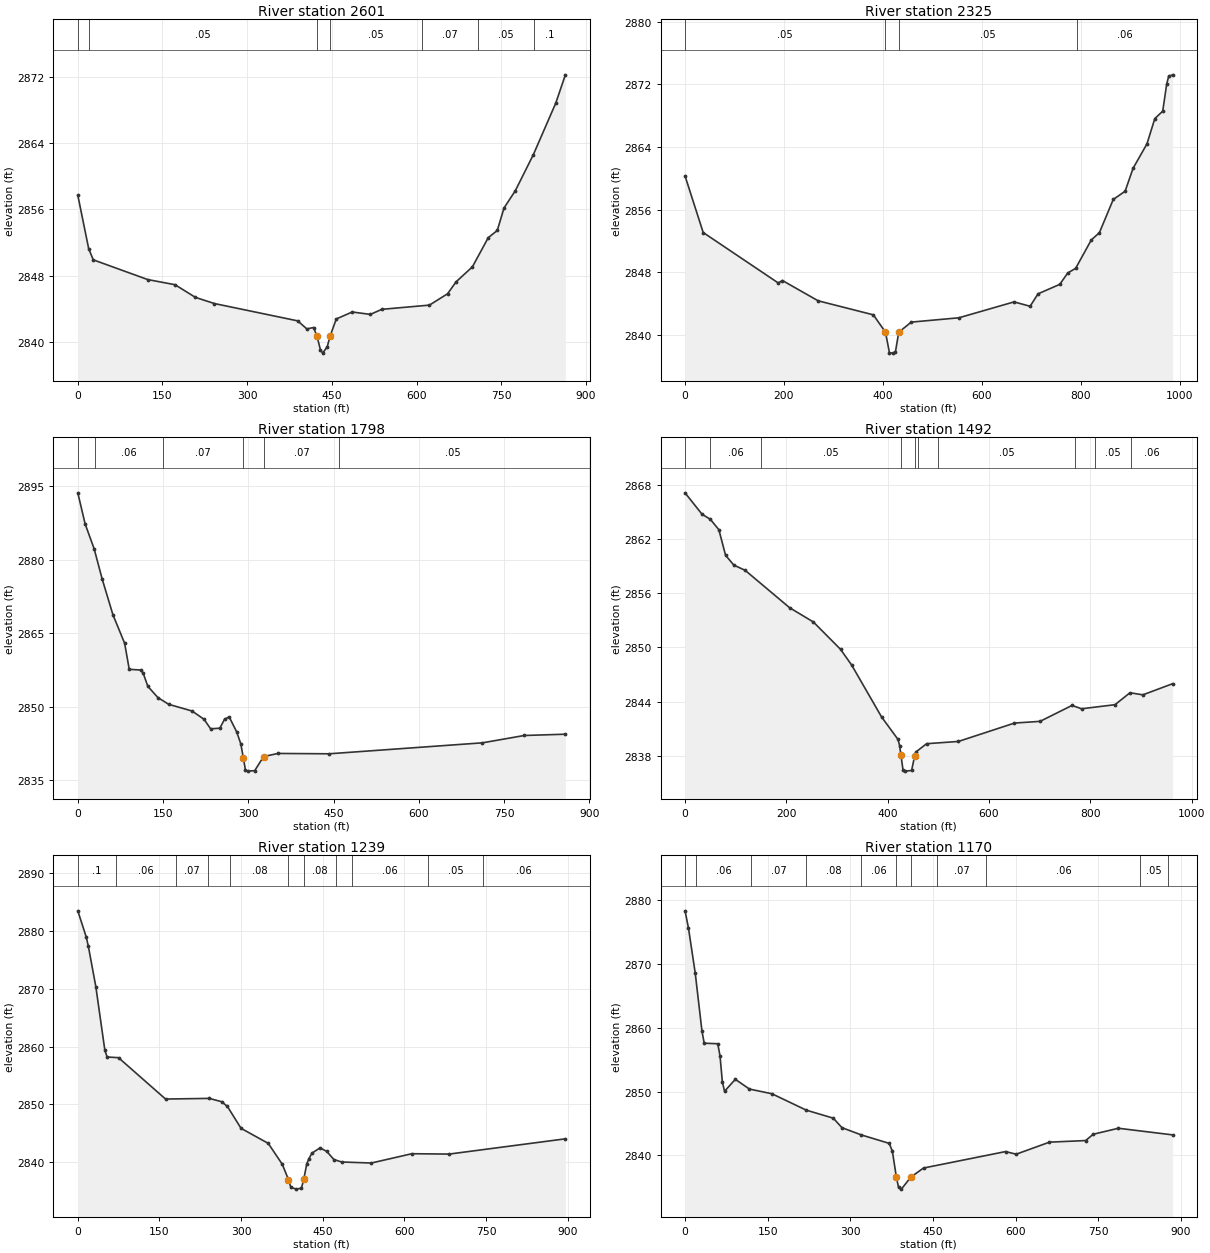
Type RM Length L Ch R = 1 ,2601    ,275.8,275.8,275.8
XS GIS Cut Line= 3
2333500.94099013656176.6430184122334135.80487052656244.801152033
2334360.72784496656241.362719441
#Sta/Elev= 30
       0 2857.71    19.3 2851.25    27.4 2849.91   123.9 2847.53   172.2 2846.91
   208.4 2845.38   241.9 2844.64   389.5 2842.55   405.6 2841.58   417.6 2841.75
  423.78 2840.67   429.7 2839.06   433.7 2838.66   441.8 2839.43   446.6 2840.67
   457.8 2842.78     486 2843.62   518.2 2843.33   538.3 2843.94   622.8 2844.45
   654.9 2845.82     670 2847.26   698.9 2849.07   726.9 2852.58   742.9 2853.45
   754.9 2856.17   774.9 2858.25   806.9 2862.61   846.5 2868.81   863.5 2872.22
#Mann= 7, -1 ,  0
       0    0.07       0      20    0.05       0  423.78   0.045       0
   446.6    0.05       0     610    0.07       0  708.51    0.05       0
  808.51     0.1       0
Bank Sta=423.78,446.6
XS Rating Curve= 0 ,0
Exp/Cntr(USF)=0,0
Exp/Cntr=0.3,0.1

Type RM Length L Ch R = 1 ,2325    ,527.2,527.2,527.2
XS GIS Cut Line= 3
2333419.55355324656455.0374101962334081.07858655 656492.57005486
 2334404.1320802656502.861273017
#Sta/Elev= 30
       0 2860.32    36.7  2853.1   188.4 2846.66   196.9 2846.97   269.1 2844.38
   380.7 2842.59   405.3 2840.37   413.3 2837.74   419.7  2837.7   425.3 2837.83
   432.12840.367   457.4 2841.66   553.5 2842.21   665.2 2844.24   697.7 2843.68
   713.7 2845.27   757.7 2846.48   773.7 2847.93   789.7 2848.52   821.3 2852.14
   837.8 2853.08   865.8 2857.32   889.8 2858.37   905.8 2861.29   933.9 2864.41
   949.8 2867.64   965.8 2868.59   973.8 2872.03   977.8 2873.04   985.8 2873.23
#Mann= 4, -1 ,  0
       0    0.05       0   405.3   0.045       0   432.1    0.05       0
  792.59    0.06       0
Bank Sta=405.3,432.1
XS Rating Curve= 0 ,0
Exp/Cntr(USF)=0,0
Exp/Cntr=0.3,0.1

Type RM Length L Ch R = 1 ,1798    ,305.8,305.8,305.8
XS GIS Cut Line= 2
2333267.57662065656907.5141867812334106.90377111 656731.35910582
#Sta/Elev= 30
       0 2893.65    12.9  2887.3    28.8  2882.2      43    2876    61.9 2868.71
    82.4 2862.92    90.5  2857.6     111 2857.46   115.1 2856.78   123.2 2854.13
     141 2851.82     160 2850.45   200.9 2849.09   222.1  2847.4   233.6 2845.45
   249.9 2845.58   258.1 2847.41   266.3 2847.88   279.5 2844.82   286.7 2842.39
   291.32839.466   294.9    2837     299 2836.81   311.2 2836.91   326.8 2839.79
   352.1 2840.42     442 2840.35   711.8 2842.59   785.3 2844.09   857.6 2844.35
#Mann= 6, -1 ,  0
       0     0.1       0      30    0.06       0     150    0.07       0
   291.3   0.045       0   326.8    0.07       0     460    0.05       0
Bank Sta=291.3,326.8
XS Rating Curve= 0 ,0
Exp/Cntr(USF)=0,0
Exp/Cntr=0.3,0.1

Type RM Length L Ch R = 1 ,1492    ,253.1,253.1,253.1
XS GIS Cut Line= 2
2333276.95156032657259.4862291052334187.77694952656948.624321527
#Sta/Elev= 30
       0 2867.09    33.6 2864.72    49.9 2864.17    66.8 2863.01      80 2860.19
    96.4  2859.1   118.6 2858.53   206.3  2854.4   253.3 2852.82   306.9  2849.8
   328.9 2848.06     388 2842.32   420.3 2839.85   423.5 2839.17   426.1 2838.12
   430.3 2836.47   434.5 2836.34   447.2 2836.41   453.1 2837.99   455.6 2838.45
   476.8 2839.37   539.6 2839.62   650.3 2841.65   700.8 2841.84   763.8  2843.6
   782.7 2843.23   848.7 2843.68   878.3    2845   903.7 2844.77   962.4    2846
#Mann= 10, -1 ,  0
       0     0.1       0      50    0.06       0     150    0.05       0
   426.1   0.045       0   453.1    0.05       0     460    0.07       0
     500    0.05       0     770    0.06       0     810    0.05       0
     880    0.06       0
Bank Sta=426.1,453.1
XS Rating Curve= 0 ,0
Exp/Cntr(USF)=0,0
Exp/Cntr=0.3,0.1

Type RM Length L Ch R = 1 ,1239    ,68.7,68.7,68.7
XS GIS Cut Line= 4
2333348.44979906 657461.546469032333697.30798413657359.004739318
2333747.15038436657324.7762326832334128.91996168657047.877587728
#Sta/Elev= 30
       0  2883.5    15.5 2878.97    19.4 2877.35    33.1 2870.39    49.7 2859.36
    53.9 2858.19    74.8 2858.07   161.2 2850.91   241.5 2851.02   264.3 2850.45
   274.9 2849.62   299.9 2845.84   349.9 2843.23   375.6 2839.62     3872836.965
   391.4 2835.61   401.5 2835.31   410.8 2835.48   415.22837.024   420.5 2839.63
   424.5 2840.59   430.3 2841.55   445.1 2842.46   457.5 2841.83   470.4 2840.44
   484.6 2840.01   539.2 2839.83   613.6 2841.44   682.3 2841.38   895.7 2844.02
#Mann= 11, -1 ,  0
       0     0.1       0      70    0.06       0     180    0.07       0
     240    0.05       0     280    0.08       0     387   0.045       0
   415.2    0.08       0  474.08    0.07       0  504.08    0.06       0
  644.08    0.05       0  744.08    0.06       0
Bank Sta=387,415.2
XS Rating Curve= 0 ,0
Exp/Cntr(USF)=0,0
Exp/Cntr=0.3,0.1

Type RM Length L Ch R = 1 ,1170    ,248.4,248.4,248.4
XS GIS Cut Line= 4
2333398.15294288657503.8922261242333728.85341106657430.728405732
2333805.91930187657355.6135501292334153.20356933657088.321726296
#Sta/Elev= 30
       0 2878.35     6.2 2875.67    18.5 2868.58    30.7 2859.49    34.8 2857.58
    59.4  2857.5    63.5 2855.57    67.7 2851.52    71.7 2850.04    91.2 2851.92
   116.8 2850.39   157.7 2849.65     220 2847.08     269 2845.82   284.7 2844.33
     320 2843.19   370.4 2841.87   376.1 2840.67  383.54 2836.52   387.4 2834.96
   392.5 2834.69   409.7 2836.58   432.7    2838   581.5 2840.58   600.8 2840.17
   661.2 2842.06   726.8 2842.31   740.6  2843.3   786.2 2844.24   884.6  2843.2
#Mann= 11, -1 ,  0
       0     0.1       0      20    0.06       0     120    0.07       0
     220    0.08       0     320    0.06       0  383.54   0.045       0
   409.7    0.08       0  456.31    0.07       0  546.31    0.06       0
  826.31    0.05       0  876.31    0.06       0
Bank Sta=383.54,409.7
XS Rating Curve= 0 ,0
Exp/Cntr(USF)=0,0
Exp/Cntr=0.3,0.1

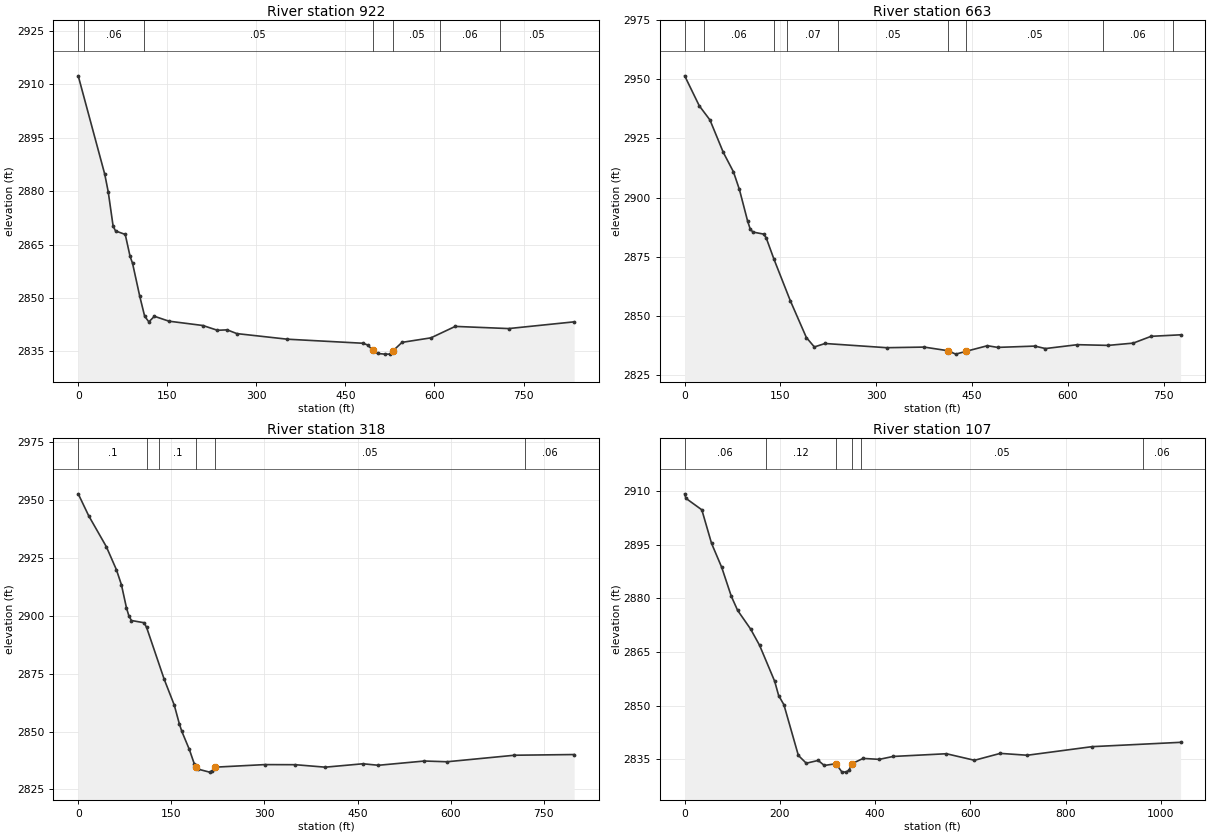
Type RM Length L Ch R = 1 ,922     ,258.6,258.6,258.6
XS GIS Cut Line= 2
2333410.62218058 657660.49808988 2334228.1889975657489.524040712
#Sta/Elev= 30
       0 2912.34    44.7 2884.73    50.6 2879.75    58.8 2870.15    62.9 2868.81
    79.2 2867.84    87.4 2861.65    91.5 2859.75   103.7 2850.45   111.9 2844.89
     119  2843.3   128.3 2844.87   152.7  2843.5     210 2842.28   234.5 2840.94
   250.9 2841.06   267.2 2840.01   352.2 2838.44   479.7  2837.3   487.9 2836.79
   496.1 2835.28   504.3 2834.43   516.5 2834.25   524.7 2834.25   530.42835.213
   545.4 2837.55   594.1 2838.82     635 2842.03   724.9 2841.42   835.3 2843.31
#Mann= 7, -1 ,  0
       0     0.1       0      10    0.06       0     110    0.05       0
   496.1   0.045       0   530.4    0.05       0     610    0.06       0
     710    0.05       0
Bank Sta=496.1,530.4
XS Rating Curve= 0 ,0
Exp/Cntr(USF)=0,0
Exp/Cntr=0.3,0.1

Type RM Length L Ch R = 1 ,663     ,344.8,344.8,344.8
XS GIS Cut Line= 4
2333386.43624484657835.2942287912333747.37775877657721.483841516
2333889.36976575657757.2528203742334120.24226565657656.449334501
#Sta/Elev= 30
       0 2951.52    22.8 2938.86    39.6 2932.82    60.5  2919.1    76.4 2910.87
    85.7 2903.42    98.7  2889.9   102.5  2886.8   106.7 2885.39   123.5 2884.51
   127.6 2882.98     140 2873.78   165.4 2856.34   190.6 2840.72   203.1 2836.73
   219.9 2838.19   316.4 2836.41   375.1 2836.67   411.8 2835.16   424.7 2833.69
   440.52834.866   474.2 2837.25   490.3 2836.54   548.3 2837.09   565.1 2836.05
   615.2 2837.69   663.3 2837.39   702.5 2838.35   730.6 2841.23   776.8 2841.87
#Mann= 9, -1 ,  0
       0     0.1       0      30    0.06       0     140     0.1       0
     160    0.07       0     240    0.05       0   411.8   0.045       0
   440.5    0.05       0  654.89    0.06       0  764.89    0.05       0
Bank Sta=411.8,440.5
XS Rating Curve= 0 ,0
Exp/Cntr(USF)=0,0
Exp/Cntr=0.3,0.1

Type RM Length L Ch R = 1 ,318     ,211.7,211.7,211.7
XS GIS Cut Line= 3
 2333407.5135615658005.5548072912333861.37194656657930.947949472
2334144.25628246657744.430804926
#Sta/Elev= 30
       0 2952.73    16.9 2943.24    45.3 2929.89    61.5 2919.96    69.6 2913.45
    77.7 2903.49    81.7  2899.9    85.8 2897.99   106.1 2897.03   110.1 2895.04
   138.5 2872.59   154.7 2861.46   162.8 2853.43   166.9 2850.06     179 2842.27
   187.1 2835.93   189.5 2834.78   192.4 2833.82   211.5 2832.48   215.5 2832.99
   220.2 2834.62   300.3 2835.73   349.6 2835.69   397.9 2834.62   458.7 2836.09
   483.5 2835.44   557.6 2837.28     594 2836.96   702.7 2839.78   798.8 2840.08
#Mann= 6, -1 ,  0
       0     0.1       0     110    0.06       0     130     0.1       0
   189.5   0.045       0   220.2    0.05       0  719.95    0.06       0
Bank Sta=189.5,220.2
XS Rating Curve= 0 ,0
Exp/Cntr(USF)=0,0
Exp/Cntr=0.3,0.1

Type RM Length L Ch R = 1 ,107     ,,,
XS GIS Cut Line= 3
2333357.77565629658254.244333353  2333920.435709 658101.92199864
2334265.49242641 657800.38594829
#Sta/Elev= 30
       0  2909.2     2.5 2907.95      36 2904.73    56.4 2895.36    77.8 2888.63
    97.8  2880.6   111.2 2876.61   138.3 2871.43   157.2 2866.87     189 2856.79
   197.3  2852.8   208.3 2850.26   238.7 2836.07   255.3  2833.9   280.3 2834.68
   293.1 2833.27   317.4 2833.76   329.9 2831.49   338.7 2831.41   345.2 2831.98
   350.6 2833.73   374.6 2835.24   408.6 2834.98   437.6 2835.79   549.5 2836.55
   608.4 2834.72   662.6 2836.65   719.3 2836.13   855.4 2838.53  1041.2 2839.74
#Mann= 6, -1 ,  0
       0    0.06       0     170    0.12       0   317.4   0.045       0
   350.6    0.12       0     370    0.05       0  962.91    0.06       0
Bank Sta=317.4,350.6
XS Rating Curve= 0 ,0
Exp/Cntr(USF)=0,0
Exp/Cntr=0.3,0.1
LCMann Table=0

Chan Stop Cuts=-1
Use User Specified Reach Order=0
Composite Channel Slope=5